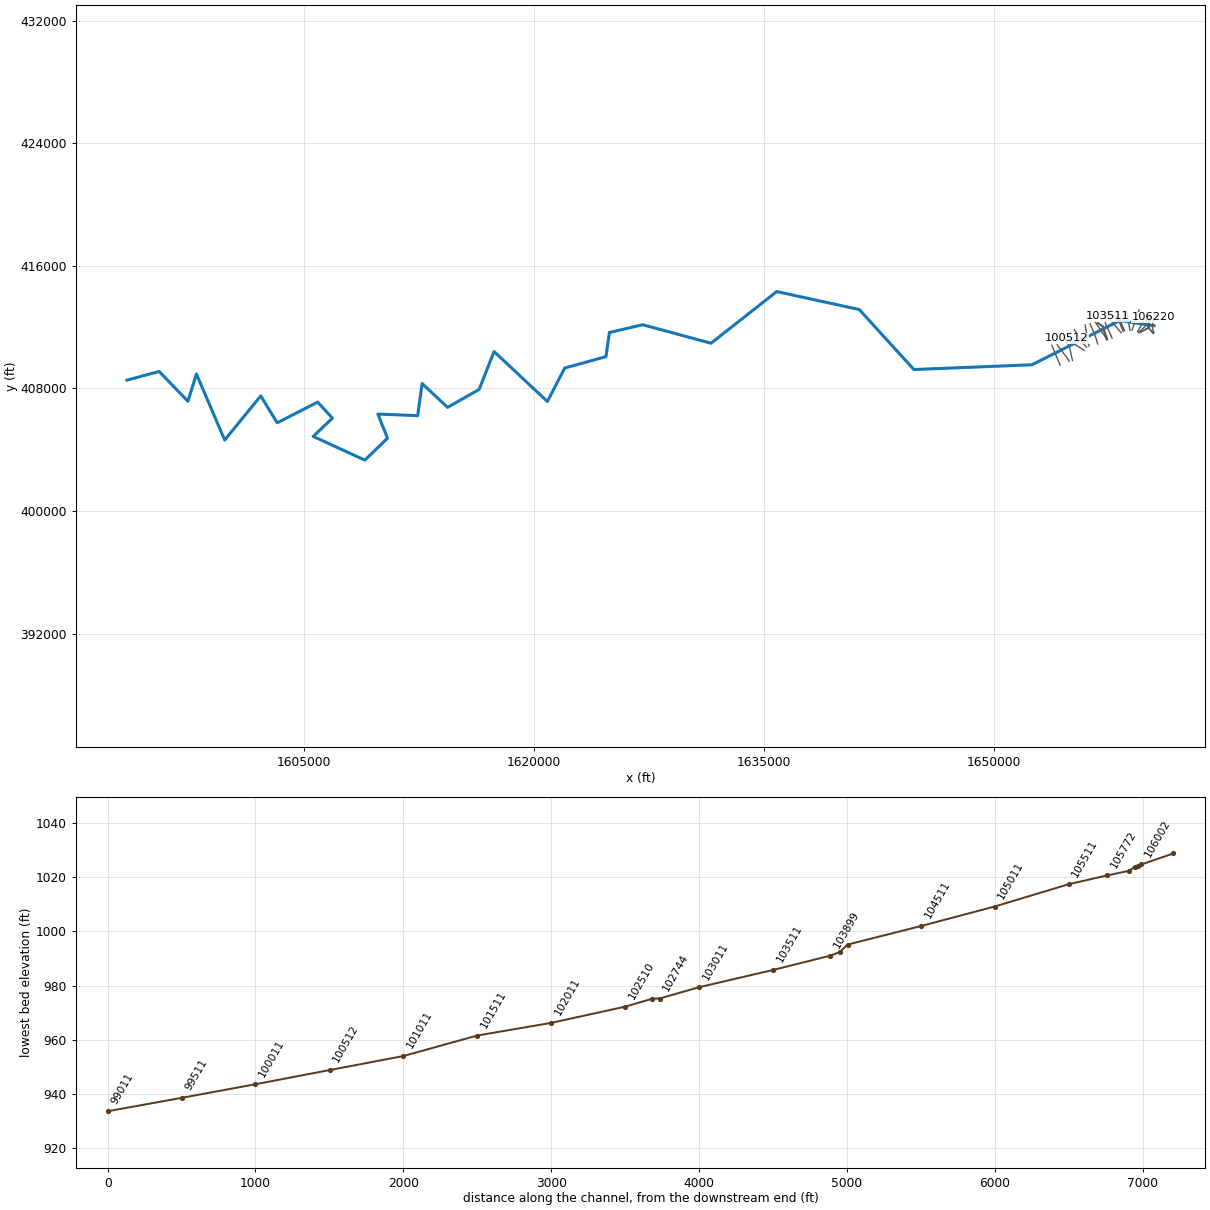
--- LTLFSHNGCK.prj (project) ---

Proj Title=LTLFSHNGCK
Current Plan=p01
Default Exp/Contr=0,0
English Units
Geom File=g01
Flow File=f01
Plan File=p01
BEGIN DESCRIPTION:
---------- MODELED AS PART OF WVEMD CTP PROGRAM, 2023----------
Stream Name:Little Fishing Creek
Flood Zone:  AFH
Wetzel County, WV
HEC-RAS Version: RAS 6.3
Vertical Datum: NAVD88
Projection: NAD 1983 StatePlane West Virginia S FIPS 4702 (US Feet)
Terrain: 1-meter West Virginia FEMA R3 South Central (collected 2018-2020)
Land Use: 2019 NLCD
Hydrologic Method:
WV SIR2010-5033 regression equations
Additional Model Notes:
Leveraged XS
END DESCRIPTION:
DSS Export Rating Curves= 0
DSS Export Rating Curve Sorted= 0
DSS Export Volume Flow Curves= 0
DXF OffsetX= 0
DXF OffsetY= 0
DXF ScaleX= 0
DXF ScaleY= 0

--- LTLFSHNGCK.p01 (plan) ---

Plan Title=Floodplain
Program Version=6.30
Short Identifier=Floodplain
Geom File=g01
Flow File=f01
Subcritical Flow
K Sum by GR= 0
Std Step Tol= 0.01
Critical Tol= 0.01
Num of Std Step Trials= 20
Max Error Tol= 0.3
Flow Tol Ratio= 0.001
Split Flow NTrial= 30
Split Flow Tol= 0.02
Split Flow Ratio= 0.02
Log Output Level= 0
Friction Slope Method= 1
Unsteady Friction Slope Method= 2
Unsteady Bridges Friction Slope Method= 1
Parabolic Critical Depth
Global Vel Dist= 0 , 0 , 0
Global Log Level= 0
CheckData=True
Encroach Param=-1 ,0,0, 0
Mapping Interval=1HOUR
Computation Time Step Use Courant=        0
Computation Time Step Use Time Series=    0
Computation Time Step Count To Double=0
Computation Time Step Max Doubling=0
Computation Time Step Max Halving=0
Computation Time Step Residence Courant=0
Run HTab= 0
Run UNet= 0
Run Sediment= 0
Run PostProcess= 0
Run WQNet= 0
Run RASMapper= 0
UNET Theta= 0
UNET Theta Warmup= 0
UNET ZTol= 0
UNET ZSATol= 0
UNET MxIter= 0
UNET Max Iter WO Improvement= 0
UNET MaxInSteps= 0
UNET DtIC= 0
UNET DtMin= 0
UNET MaxCRTS= 0
UNET WFStab= 0
UNET SFStab= 0
UNET WFX= 1
UNET SFX= 1
UNET Gravity=32.17405
UNET 1D Methodology=Finite Difference
UNET DSS MLevel= 1
UNET Pardiso=0
UNET DZMax Abort= 0
UNET Use Existing IB Tables= 0
UNET Froude Reduction=False
UNET Froude Limit= 0
UNET Froude Power= 0
UNET D1 Cores= 0
UNET WindReference=Eulerian
UNET WindDragFormulation=Hsu (1988)
UNET D2 Coriolis=0
UNET D2 Cores= 0
UNET D2 Theta= 1
UNET D2 Theta Warmup= 1
UNET D2 Z Tol= 0.01
UNET D2 Volume Tol= 0.01
UNET D2 Max Iterations= 20
UNET D2 Equation= 0
UNET D2 RampUpFraction=0.1
UNET D2 TimeSlices= 1
UNET D2 Turbulence Formulation=Non-Conservative (original)
UNET D2 Eddy Viscosity=0.3
UNET D2 Transverse Eddy Viscosity=0.1
UNET D2 Smagorinsky Mixing=0
UNET D2 BCVolumeCheck=0
UNET D2 Cores=0
UNET D2 SolverType=PARDISO (Direct)
UNET D2 Minimum Iterations= 3
UNET D2 Maximum Iterations= 30
UNET D2 Restart Number= 10
UNET D2 Relaxation Coeff=1.3
UNET D2 SOR Precondition Iterations= 10
UNET D2 ILUT Maximum Fill= 8
UNET D2 ILUT Tolerance=1E-08
UNET D2 Convergence Tolerance=0.00001
UNET D1D2 MaxIter= 0
UNET D1D2 ZTol=0.01
UNET D1D2 QTol=0.1
UNET D1D2 MinQTol=1
Write IC File= 0
Write IC File at Fixed DateTime=0
Write IC File at Sim End=0
Echo Input=False
Echo Parameters=False
Echo Output=False
Write Detailed= 0
HDF Write Warmup=0
HDF Write Time Slices=0
HDF Flush=0
HDF Compression= 1
HDF Chunk Size= 1
HDF Spatial Parts= 1
HDF Use Max Rows=0
HDF Fixed Rows= 1
Calibration Method= 0
Calibration Iterations= 20
Calibration Max Change=0.05
Calibration Tolerance=0.2
Calibration Maximum=1.5
Calibration Minimum=0.5
Calibration Optimization Method= 1
WQ AD Non Conservative
WQ ULTIMATE=-1
WQ Max Comp Step=1HOUR
WQ Output Interval=15MIN
WQ Output Selected Increments= 0
WQ Output face flow=0
WQ Output face velocity=0
WQ Output face area=0
WQ Output face dispersion=0
WQ Output cell volume=0
WQ Output cell surface area=0
WQ Output cell continuity=0
WQ Output cumulative cell continuity=0
WQ Output face conc=0
WQ Output face dconc_dx=0
WQ Output face courant=0
WQ Output face peclet=0
WQ Output face adv mass=0
WQ Output face disp mass=0
WQ Output cell mass=0
WQ Output cell source sink temp=0
WQ Output nsm pathways=0
WQ Output nsm derived pathways=0
WQ Create Restart=0
WQ Fixed Restart=0
WQ System Summary=0
WQ Write To DSS=0
Sorting and Armoring Iterations= 10
XS Update Threshold= 0.02
Bed Roughness Predictor= 0
Hydraulics Update Threshold= 0.02
Energy Slope Method= 1
Volume Change Method= 1
Sediment Retention Method= 0
Sediment TS Multiplier= 1
Warm Up Method= 0
XS Weighting Method= 0
Number of US Weighted Cross Sections= 1
Number of DS Weighted Cross Sections= 1
Upstream XS Weight=0
Main XS Weight=1
Downstream XS Weight=0
Number of DS XS's Weighted with US Boundary= 1
Upstream Boundary Weight= 1
Weight of XSs Associated with US Boundary= 0
Number of US XS's Weighted with DS Boundary= 1
Downstream Boundary Weight= 0.5
Weight of XSs Associated with DS Boundary= 0.5
Percentile Method= 0
Sediment Output Level= 3
Mass or Volume Output= 0
Output Increment Type= 1
Profile and TS Output Increment= 1
Transport Output Increment 1
XS Output Flag= 0
XS Output Increment= 10
Read HDF5 Sediment Hotstart= 0
Sediment Hotstart Type= 0
Write Gradation File= 0
Read Gradation Hotstart= 0
Write HDF5 File= 1
Write Binary Output= 1
Write DSS Sediment File= 0
DSS Sediment Output Type= 1
SV Curve= 0
Specific Gage Flag= 0
Subcell Erosion Methods= 0
Subcell Deposition Methods= 0
Advection Scheme= 1
Matrix Solver= 0
Implicit Weighting Factor= 1
Maximum Outer Loop Convergence Iterations= 5
Convergence Maximum Absolute= 0.001
Convergence RMSE= 0.0001
Grain Fractions Max Abs Error= 0.001
Max Subgrid Regions= 1
Max Subgrid Length Scale= 3.402823E+38
Initial Layer Thickness= 3.402823E+38
Min Layer Thickness= 3.402823E+38
Max Layer Thickness= 3.402823E+38
Number of Layers= 5

--- LTLFSHNGCK.f01 (steady flow) ---

Flow Title=Flow
Program Version=6.30
Number of Profiles= 1
Profile Names=F01pct
River Rch & RM=River 1,Reach 1,106220
     629
River Rch & RM=River 1,Reach 1,104016
     733
River Rch & RM=River 1,Reach 1,102744
     921
River Rch & RM=River 1,Reach 1,100011
    1030
River Rch & RM=River 1,Reach 1,97965
    1160
River Rch & RM=River 1,Reach 1,93630
    1590
River Rch & RM=River 1,Reach 1,88506
    1810
River Rch & RM=River 1,Reach 1,84506
    2510
River Rch & RM=River 1,Reach 1,80006
    2790
River Rch & RM=River 1,Reach 1,77001
    3840
River Rch & RM=River 1,Reach 1,65506
    4930
River Rch & RM=River 1,Reach 1,58506
    5480
River Rch & RM=River 1,Reach 1,47500
    6120
River Rch & RM=River 1,Reach 1,31500
    6800
Boundary for River Rch & Prof#=River 1,Reach 1         , 1
Up Type= 0
Dn Type= 3
Dn Slope=0.00153
DSS Import GetInterval= 0
DSS Import GetPeak= 0
DSS Import FillOption= 0

--- LTLFSHNGCK.g01 (geometry) ---

Geom Title=Geometry
Program Version=6.30

River Reach=River 1         ,Reach 1
Reach XY= 30
1660456.90894088412091.0222445581658214.08632681412427.365403891
1652490.69816731 409544.593938471644790.97340931409233.330453396
1641223.42608248413149.5152063071635842.30856389414319.302892983
1631555.16950038410949.9753140661627097.49468872412157.506363556
1624926.57777072411647.9532488141624702.96076389410072.370441973
1622014.19678447409333.5182451461620883.06469797407148.838715299
1617403.24340796410409.2162249831616430.64758414407935.912444562
1614369.75177155406765.1313215641612709.80856913408321.972367972
1612422.26846181406225.563831151 1609826.3878268406327.520320147
1610453.01911947404755.7869150641608977.51419647403323.813729137
1605602.64004073 404871.490095721606859.33962706406060.600578398
1605899.34482789 407109.95051381 1603256.4954548405758.167784303
1602185.37981489407513.1941298991599833.50722206404635.501066387
1597986.83473431408945.1669877321597434.66589114407162.646930724
1595559.35402498409107.8392345611593461.39463823408542.023108974

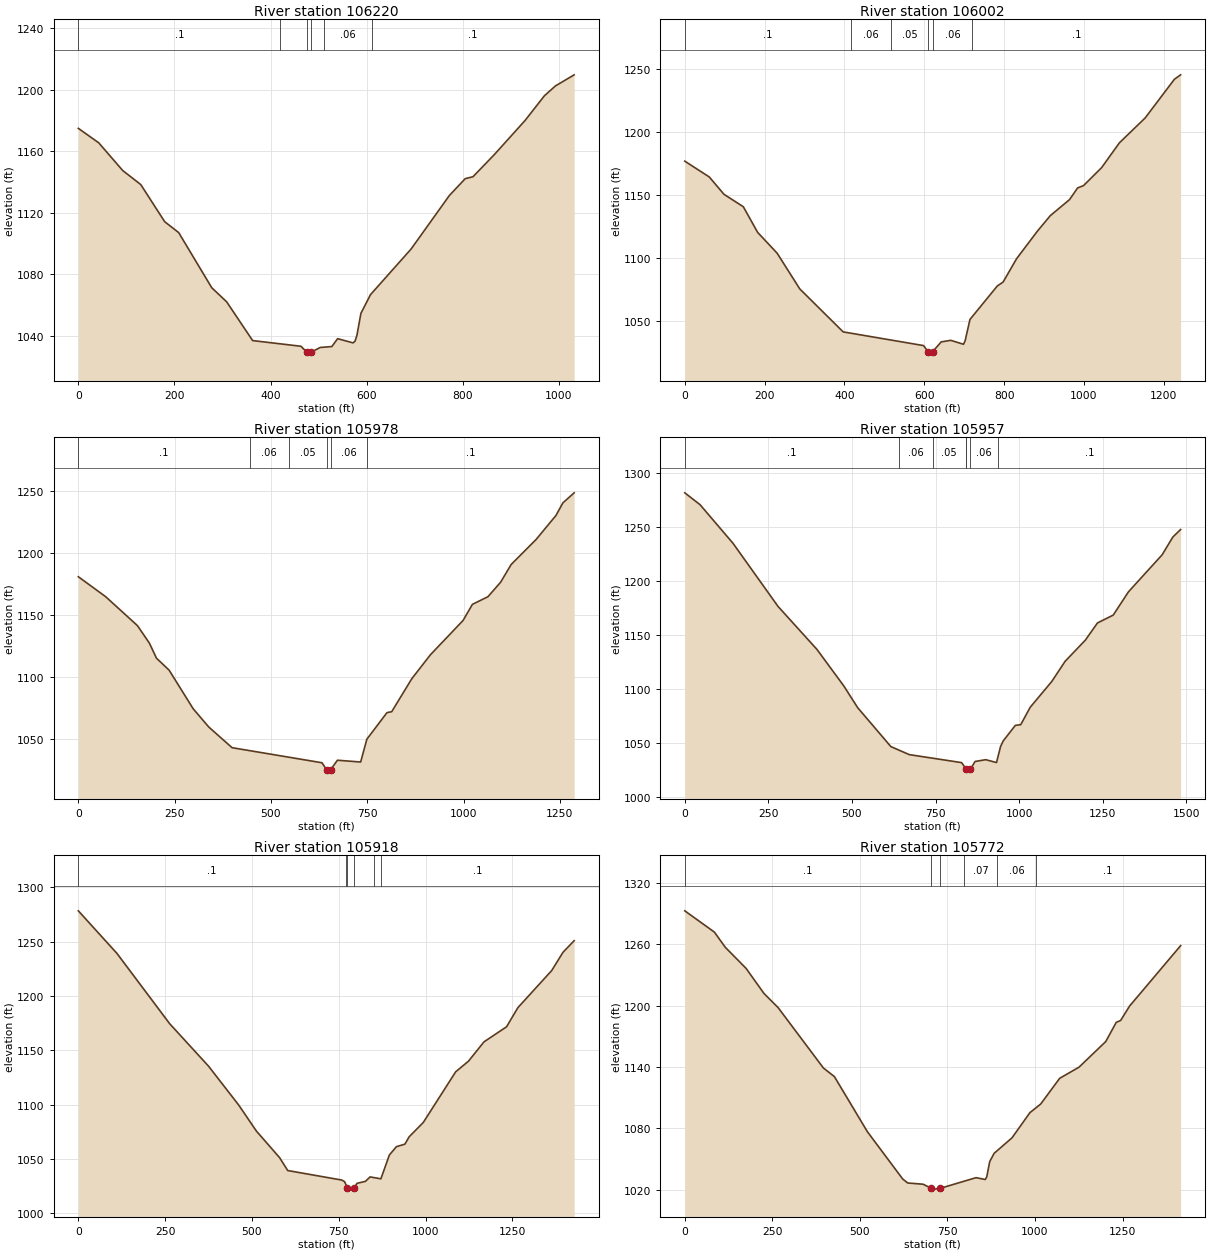
Type RM Length L Ch R = 1 ,106220  ,216.8,217.3,217.4
BEGIN DESCRIPTION:
Structure 26 XS 4
END DESCRIPTION:
XS GIS Cut Line= 3
1660446.24087117411623.6280793461660347.69587546411970.234615963
1660419.05604476412637.961914447
#Sta/Elev= 30
       0 1174.92    42.5  1165.5    92.4 1147.48   129.9 1138.38   179.8 1114.19
   208.9 1107.12   277.7 1071.26   308.7 1062.11   362.8  1036.9   463.2 1033.22
   475.3 1029.46   479.3 1028.75   484.1 1029.32   503.5 1032.43   527.6 1033.03
   539.7 1038.16   571.8  1035.4   575.9 1036.53   579.9 1040.45   588.1 1054.63
     608 1066.75   692.5 1096.43   772.3 1131.29   805.2  1142.2   821.3 1143.45
   865.5 1157.75   929.8 1180.06   970.1 1196.14     993 1202.51  1031.9 1209.72
#Mann= 6, -1 ,  0
       0     0.1       0  420.34    0.05       0   475.3   0.045       0
   484.1    0.05       0  510.34    0.06       0  610.34     0.1       0
Bank Sta=475.3,484.1
XS Rating Curve= 0 ,0
Exp/Cntr(USF)=0,0
Exp/Cntr=0.3,0.1

Type RM Length L Ch R = 1 ,106002  ,24.8,24.7,24.6
BEGIN DESCRIPTION:
Structure 26 XS 3
END DESCRIPTION:
XS GIS Cut Line= 4
1660412.54267352411610.330663648 1660137.2963062411923.805693089
1660155.64606402412206.6977928281660216.81192343412744.957355575
#Sta/Elev= 30
       0 1176.88    61.4 1164.32    98.2 1150.58   146.7 1140.71   182.5 1120.42
   231.5 1103.85   288.1 1075.58   396.8  1041.5   598.3 1030.64  609.65 1025.75
   614.3 1024.66  620.711025.663   642.4 1033.56   666.4  1034.8   698.5 1031.68
   702.5 1034.56   714.6 1051.38     783 1077.87   797.6 1081.03   831.3 1099.49
   883.9 1121.52     916 1133.71   964.2 1146.43   984.3 1155.65   999.2  1157.5
  1044.7 1171.83    1089 1191.41  1153.4 1211.08  1226.9 1241.83  1242.4 1245.32
#Mann= 6, -1 ,  0
       0     0.1       0  417.17    0.06       0  517.17    0.05       0
  609.65   0.045       0  620.71    0.06       0  720.65     0.1       0
Bank Sta=609.65,620.71
XS Rating Curve= 0 ,0
Exp/Cntr(USF)=0,0
Exp/Cntr=0.3,0.1

Type RM Length L Ch R = 1 ,105978  ,21.2,21.2,21.3
BEGIN DESCRIPTION:
Structure 26 XS 2
END DESCRIPTION:
XS GIS Cut Line= 4
1660400.30950163411584.3351734021660109.77166947411922.276546604
1660132.70886675412214.343525254 1660198.4621656412758.719673941
#Sta/Elev= 30
       0 1180.65    71.2 1164.53   153.5 1141.29   184.4 1127.27   202.8 1115.14
   235.7 1105.46   298.1 1074.43   338.5 1059.76   399.1 1043.11   632.5 1030.98
   644.5 1025.34   648.5 1024.25   654.6 1025.29   654.6  1025.3   672.6 1033.02
   732.8 1031.57   748.9 1049.93   801.2 1071.32   813.4 1072.06   865.7 1098.66
   914.1 1117.93   998.7 1145.48  1022.9 1158.42  1063.2 1164.56    1096 1176.17
  1123.6 1190.51  1188.1 1210.58  1239.8 1229.93  1257.7 1240.04    1287 1248.15
#Mann= 6, -1 ,  0
       0     0.1       0  445.66    0.06       0  545.66    0.05       0
   644.5   0.045       0   654.6    0.06       0  748.63     0.1       0
Bank Sta=644.5,654.6
XS Rating Curve= 0 ,0
Exp/Cntr(USF)=0,0
Exp/Cntr=0.3,0.1

Type RM Length L Ch R = 1 ,105957  ,38.5,38.7,39.2
BEGIN DESCRIPTION:
Structure 25 XS 3
END DESCRIPTION:
XS GIS Cut Line= 4
1659507.33135917411638.571795728 1660088.4070235411932.167920862
1660111.34422078412207.4142881761660177.09751964412759.436169289
#Sta/Elev= 30
       0 1281.37    45.7 1270.37   144.3 1234.62   278.9  1176.2   395.3  1136.4
   475.9 1102.47   517.1 1082.47   616.4 1046.41   671.5 1038.97     828 1031.57
  842.531025.292   848.1 1023.69  854.451025.361   868.2  1032.6   900.3 1034.29
   932.4 1031.62   944.5 1046.37   952.5 1051.68   988.8 1066.06  1004.9 1066.68
  1033.3 1082.84  1097.6 1106.62  1137.8 1125.41  1198.3 1145.01  1234.5  1160.9
  1281.7  1168.2  1327.2 1189.71  1427.9 1223.99  1460.1 1240.52  1483.2 1247.41
#Mann= 7, -1 ,  0
       0     0.1       0     640    0.06       0  741.04    0.05       0
  841.04    0.06       0  842.53   0.045       0  854.45    0.06       0
  937.24     0.1       0
Bank Sta=842.53,854.45
XS Rating Curve= 0 ,0
Exp/Cntr(USF)=0,0
Exp/Cntr=0.3,0.1

Type RM Length L Ch R = 1 ,105918  ,141.6,145.7,152.8
BEGIN DESCRIPTION:
Structure 25 XS 2
END DESCRIPTION:
XS GIS Cut Line= 4
1659523.25250973 411659.359506961660053.86634005 411960.60136452
1660070.68695138412189.9733372821660176.19805885 412767.99070864
#Sta/Elev= 30
       0 1278.21   111.4 1238.99   263.2 1174.36   375.1 1135.31   462.1  1099.5
   512.8 1075.68   579.5 1051.28     603  1039.4   758.5 1030.66   766.5 1029.23
   774.5 1023.69   782.6 1022.31   794.6 1023.76   802.6 1027.66   826.7 1029.45
   840.1 1033.55   871.2 1031.78   895.6 1053.69   915.9 1061.34   940.3 1063.66
   952.5 1070.39   993.2 1083.58  1086.7 1130.25  1123.3 1139.92    1168  1157.7
  1233.1 1171.61  1265.6 1189.13  1363.2 1223.36  1395.7 1240.14  1427.7 1250.74
#Mann= 6, -1 ,  0
       0     0.1       0  770.16    0.05       0   774.5   0.045       0
   794.6    0.05       0  850.15    0.06       0  870.15     0.1       0
Bank Sta=774.5,794.6
XS Rating Curve= 0 ,0
Exp/Cntr(USF)=0,0
Exp/Cntr=0.3,0.1

Type RM Length L Ch R = 1 ,105772  ,268.5,260.8,248.7
BEGIN DESCRIPTION:
Structure 25 XS 1
END DESCRIPTION:
XS GIS Cut Line= 6
1659446.36331833411658.9633951391659943.76117658412108.403628957
1659928.71208145412128.4690891351659914.66625933412165.590190462
 1659897.6130818412250.6235628731660098.10117651 412809.61155575
#Sta/Elev= 30
       0 1292.55    84.5 1271.76   115.7 1256.89   174.9 1236.38   226.1 1211.81
   266.5 1197.99   395.9 1138.96   427.2 1130.59   521.4 1076.75   622.3 1030.51
   636.7 1026.64   680.5 1025.43   704.1 1021.46   712.6 1020.64   730.1 1021.48
   831.7 1031.84     858 1030.05   862.3 1032.63   870.8 1047.61   883.5 1055.67
   934.5 1070.81   985.5 1095.34  1016.3 1103.77  1070.5  1128.9  1125.8  1139.8
  1202.2 1164.87    1232 1183.57  1244.6 1185.42  1270.2 1199.52  1415.9 1258.52
#Mann= 6, -1 ,  0
       0     0.1       0   704.1   0.045       0   730.1     0.1       0
  796.98    0.07       0  892.01    0.06       0 1002.01     0.1       0
Bank Sta=704.1,730.1
XS Rating Curve= 0 ,0
Exp/Cntr(USF)=0,0
Exp/Cntr=0.3,0.1

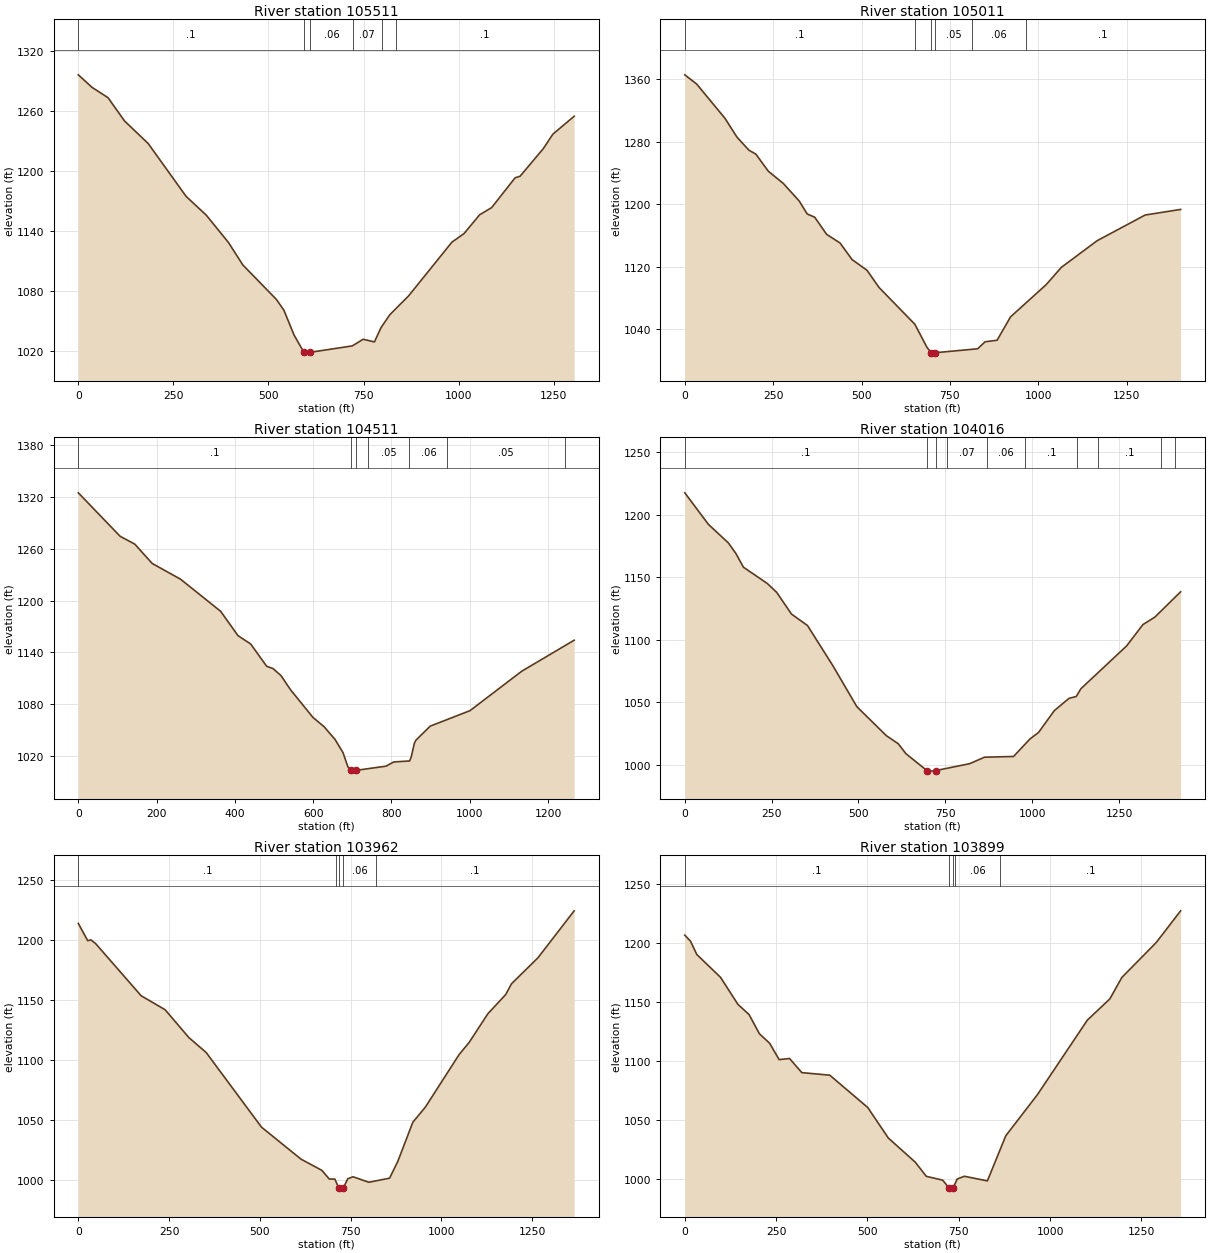
Type RM Length L Ch R = 1 ,105511  ,499.4,500.5,501.4
XS GIS Cut Line= 6
1659373.76740642411701.4954645931659618.85418659412110.830603927
1659707.90748617412261.7046460061659921.84964359412659.323929504
1659960.94864675 412750.917578341659996.77337825412844.759254172
#Sta/Elev= 30
       0 1296.11      36 1283.57    78.1 1273.22   121.5 1249.91   183.7 1227.32
   283.3 1174.43   336.4 1155.58   394.7 1128.27   432.5 1105.75   520.9 1071.13
   540.6 1060.36   567.4 1035.42593.20061018.189   601.9 1017.38609.55051018.198
   720.3  1024.6     749 1031.27   778.6 1028.61   796.2 1043.02     819 1055.76
     869 1074.92   982.3 1128.48  1014.3 1137.12  1055.2 1155.89    1087 1163.15
  1148.6 1192.96  1161.7 1194.54  1222.3 1221.97    1248 1236.68  1303.9 1254.64
#Mann= 6, -1 ,  0
       0     0.1       0593.2006   0.045       0609.5505    0.06       0
  722.29    0.07       0  797.34    0.06       0  834.85     0.1       0
Bank Sta=593.2006,609.5505
XS Rating Curve= 0 ,0
Exp/Cntr(USF)=0,0
Exp/Cntr=0.3,0.1

Type RM Length L Ch R = 1 ,105011  ,497.2,499.6,502.9
XS GIS Cut Line= 6
1659021.08602518411796.7272295061659053.45374259411893.194884345
1659117.70787917 412080.115770341659208.12174034412343.134273171
1659444.05926059413029.4957613351659476.43977326413123.695048004
#Sta/Elev= 30
       0  1365.8    33.6 1353.98   113.7 1310.06   147.6 1285.97   181.4 1269.24
   200.9 1264.24   236.4 1242.24   278.7 1226.62   323.7 1204.14   346.4 1187.45
   367.5 1183.39   401.4 1161.33   439.4 1150.23   473.3 1129.04   515.6 1115.31
   549.4 1093.37     651 1046.11   685.7 1016.19  697.621009.644   701.7 1009.16
   707.7 1009.63   828.6 1014.73   849.7 1023.71   883.6 1025.67   921.7 1055.64
  1022.5 1096.94  1065.4 1119.04  1166.3 1153.12  1302.6 1186.15  1402.9  1193.3
#Mann= 6, -1 ,  0
       0     0.1       0  652.53    0.05       0  697.62   0.045       0
   707.7    0.05       0  812.53    0.06       0  965.03     0.1       0
Bank Sta=697.62,707.7
XS Rating Curve= 0 ,0
Exp/Cntr(USF)=0,0
Exp/Cntr=0.3,0.1

Type RM Length L Ch R = 1 ,104511  ,507.3,495.6,484.6
XS GIS Cut Line= 6
1658887.42192243411787.6632712481658767.98449726412426.993029341
1658750.48650075412525.4541185051658728.32873668 412686.62604025
1658691.08766942412973.7320933341658686.03309368 413037.63830109
#Sta/Elev= 30
       0    1325     107 1274.46   144.2 1265.47   188.7 1243.02   261.3 1224.69
   363.6 1187.47   407.8 1159.24   440.4 1149.48   481.1 1123.69   497.4 1120.99
   517.7 1112.89   542.1 1096.41   599.1 1064.43   627.5 1053.66     656 1038.63
   676.3 1023.34   688.5 1007.08   696.6 1002.92   704.8 1001.94   710.3  1002.9
   785.8 1007.67     806  1012.6   846.4 1013.75   850.4 1018.26   858.5 1034.34
   862.5 1037.88   898.9 1054.16  1000.6 1072.14  1132.7 1117.88  1266.7 1153.92
#Mann= 7, -1 ,  0
       0     0.1       0   696.6   0.045       0   710.3     0.1       0
  740.39    0.05       0  845.47    0.06       0  943.08    0.05       0
 1242.59     0.1       0
Bank Sta=696.6,710.3
XS Rating Curve= 0 ,0
Exp/Cntr(USF)=0,0
Exp/Cntr=0.3,0.1

Type RM Length L Ch R = 1 ,104016  ,41.8,53.4,65.1
BEGIN DESCRIPTION:
Structure 24 XS 4
END DESCRIPTION:
XS GIS Cut Line= 6
1658522.62097305411786.1664462451658248.90375223412406.999919186
1658288.66156084412446.0263417741658305.48343938412460.654062244
1658367.65125137412473.8190106661658621.54203438413025.395975623
#Sta/Elev= 30
       0 1217.32    68.2 1192.07   125.1 1177.41   146.9    1169   168.7 1157.96
   237.3 1144.99   264.6 1137.83   307.1 1120.53   353.2 1111.37   426.6 1079.15
   495.2  1046.6   580.1 1023.45   614.6 1016.96   636.5 1009.06  696.82995.6078
   715.4  995.12  723.19995.6077   820.1 1001.07   862.7 1006.23   946.4 1006.82
   993.4 1020.75  1018.5 1026.05  1063.7 1043.43  1105.9  1053.2  1126.9 1054.71
  1140.1 1060.88  1271.8 1095.07  1318.6 1112.07  1353.2 1118.11  1427.3 1138.31
#Mann= 10, -1 ,  0
       0     0.1       0  696.82   0.045       0  723.19    0.06       0
  754.24    0.07       0  870.08    0.06       0  980.08     0.1       0
 1130.08    0.05       0 1190.08     0.1       0 1370.08    0.05       0
 1410.08     0.1       0
Bank Sta=696.82,723.19
XS Rating Curve= 0 ,0
Exp/Cntr(USF)=0,0
Exp/Cntr=0.3,0.1

Type RM Length L Ch R = 1 ,103962  ,63.3,63.2,63.1
BEGIN DESCRIPTION:
Structure 24 XS 3
END DESCRIPTION:
XS GIS Cut Line= 3
1658503.42168941411764.7583954541658180.60187589412520.836379741
1657738.84844687412836.859986657
#Sta/Elev= 30
       0 1213.99    25.9 1199.58    34.6  1200.3    47.6 1197.19     173 1153.66
     239 1141.99   304.2 1118.83   352.1 1106.29   504.3 1044.07     613 1017.39
   670.6 1007.99   691.2 1000.73   706.4 1000.72   717.4  993.03   721.8  992.34
  729.23993.0525   741.9 1000.99   756.5 1002.64     800  998.06   857.1  1001.5
   879.6 1015.39   921.1 1048.15   955.5  1060.7  1048.9 1104.75    1076 1114.65
  1127.6 1138.61  1176.8 1154.66  1192.8 1163.67  1265.3 1185.22  1365.3 1224.51
#Mann= 5, -1 ,  0
       0     0.1       0     710    0.06       0   717.4   0.045       0
  729.23    0.06       0     820     0.1       0
Bank Sta=717.4,729.23
XS Rating Curve= 0 ,0
Exp/Cntr(USF)=0,0
Exp/Cntr=0.3,0.1

Type RM Length L Ch R = 1 ,103899  ,386.6,388,390.4
BEGIN DESCRIPTION:
Structure 24 XS 2
END DESCRIPTION:
XS GIS Cut Line= 3
1658440.55677836411734.1754657521658124.53317144 412493.65155334
1657699.77025892412818.170418506
#Sta/Elev= 30
       0 1206.46    15.6 1201.34    32.9 1190.06    97.9 1170.64   145.5  1147.7
   175.9 1139.12   204.1 1122.87   232.2 1114.75   258.2 1100.89   286.7 1101.84
   320.3 1089.84   396.8 1087.69   500.8 1060.25   557.1 1034.36   630.8 1013.89
   661.1 1001.87   705.8  998.65  722.87992.1537   730.3  991.03   734.7  992.24
   745.6  999.59   765.1 1001.93   828.2  998.01   878.5 1036.25   965.7  1071.4
  1101.8 1134.38  1163.4 1152.38  1196.3  1170.6  1290.1 1200.13  1357.1 1227.09
#Mann= 5, -1 ,  0
       0     0.1       0  722.87   0.045       0   734.7     0.1       0
     740    0.06       0   862.6     0.1       0
Bank Sta=722.87,734.7
XS Rating Curve= 0 ,0
Exp/Cntr(USF)=0,0
Exp/Cntr=0.3,0.1

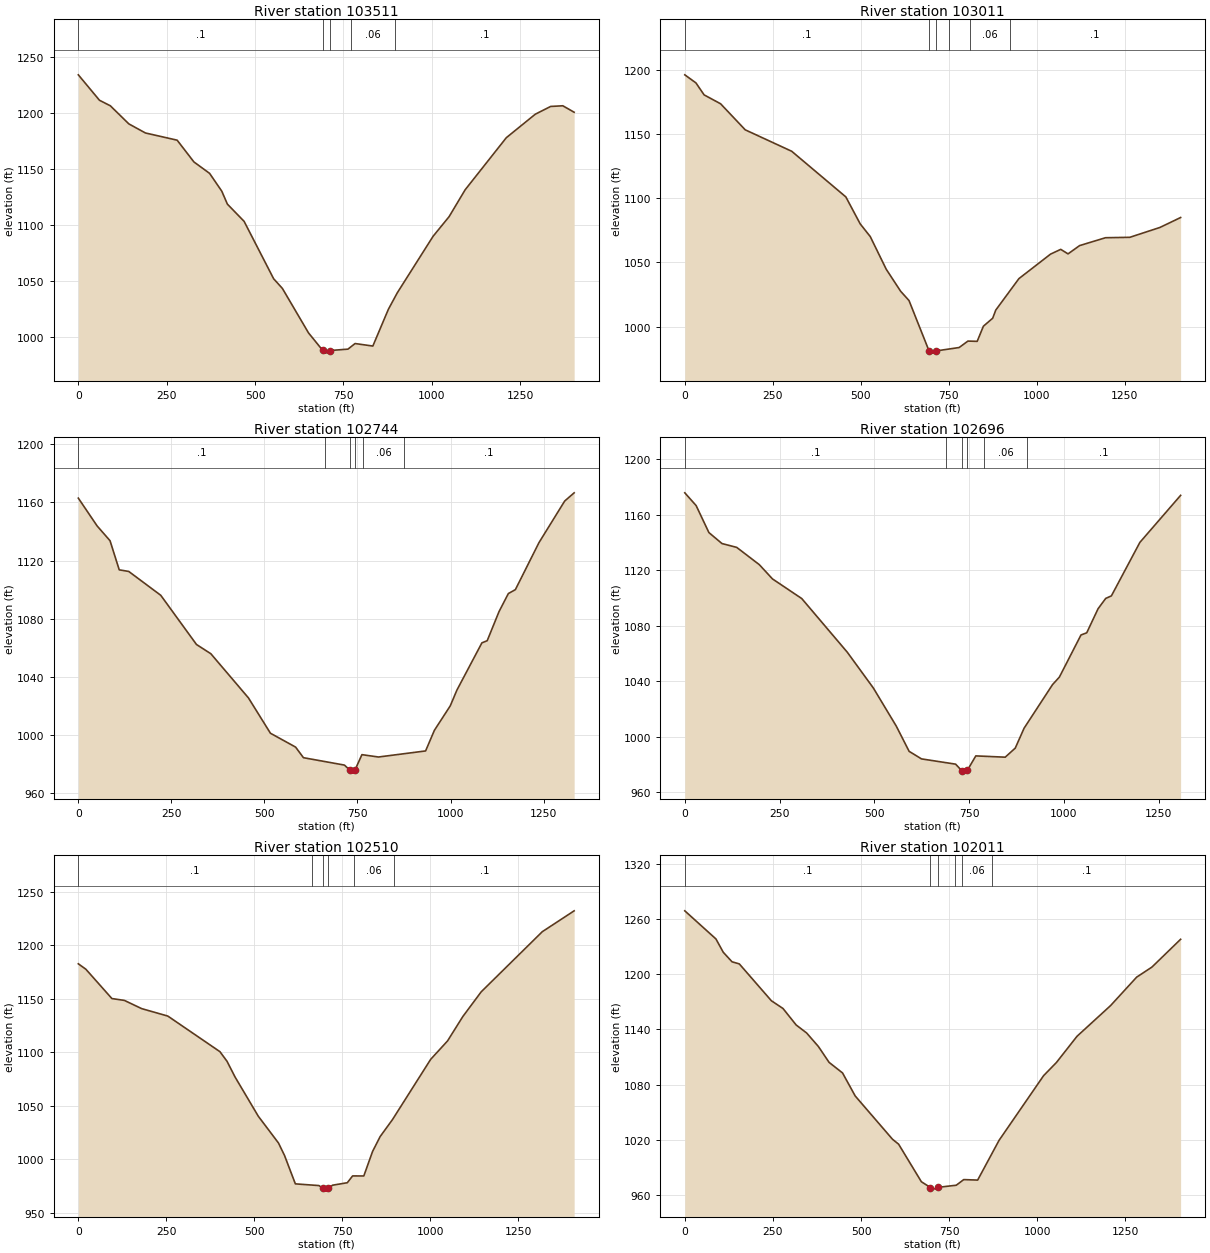
Type RM Length L Ch R = 1 ,103511  ,502.2,500.2,496.8
BEGIN DESCRIPTION:
Structure 24 XS 1
END DESCRIPTION:
XS GIS Cut Line= 6
1658310.92241925411635.8555040061657823.97457425412206.791698083
1657778.22499384412266.3480094221657668.79017334412411.469766423
1657549.01219767412566.6964900941657423.92550559412721.898935586
#Sta/Elev= 30
       0 1233.82    59.8 1211.15    90.6 1206.21   142.9 1190.09   189.7    1182
   279.6 1175.56     327 1156.17   371.3 1145.99   405.9 1130.08   421.6 1118.59
     469  1103.2   552.6    1052   577.3 1043.41   651.2 1003.78  691.45988.1398
   700.2  985.74   710.7  988.03   762.7  989.29   782.9  994.28   833.2  992.05
   877.1 1024.78   902.4 1039.53  1003.6 1089.88  1048.9 1107.39  1094.3 1131.34
  1210.8 1177.78  1292.7  1198.7  1336.2 1205.63  1370.6 1206.23  1402.7 1200.47
#Mann= 5, -1 ,  0
       0     0.1       0  691.45   0.045       0   710.7     0.1       0
  770.39    0.06       0  895.49     0.1       0
Bank Sta=691.45,710.7
XS Rating Curve= 0 ,0
Exp/Cntr(USF)=0,0
Exp/Cntr=0.3,0.1

Type RM Length L Ch R = 1 ,103011  ,267.1,266.7,263.5
BEGIN DESCRIPTION:
Structure 23 XS 4
END DESCRIPTION:
XS GIS Cut Line= 6
1657719.63160709  411283.59439751657559.18835843411643.630422845
1657342.99292468412115.1826293321657305.40113634412201.082720011
1657280.31522851412295.8135016711657222.21232635412594.335214332
#Sta/Elev= 30
       0    1196    31.7  1189.7    54.9 1180.39   101.7 1173.47   171.7 1153.19
   303.9 1136.48   457.6 1100.97   498.4 1079.97   526.9 1070.13   572.3 1044.69
   613.3 1027.54   637.1  1020.3   694.3  980.91   703.1  979.38  713.02981.0554
   779.5  983.74   804.5  988.75   830.8  988.56   848.4 1000.33   874.8 1006.54
   883.6 1012.89   949.3 1037.36  1039.2 1056.44  1068.2 1060.15  1088.9 1056.63
  1121.8 1063.08  1195.3  1069.2  1264.5 1069.53    1350  1077.2  1408.8 1084.93
#Mann= 6, -1 ,  0
       0     0.1       0   694.3   0.045       0  713.02    0.06       0
  750.42    0.07       0  810.42    0.06       0  922.92     0.1       0
Bank Sta=694.3,713.02
XS Rating Curve= 0 ,0
Exp/Cntr(USF)=0,0
Exp/Cntr=0.3,0.1

Type RM Length L Ch R = 1 ,102744  ,48.7,48.3,46.4
BEGIN DESCRIPTION:
Structure 23 XS 3
END DESCRIPTION:
XS GIS Cut Line= 5
1657423.59505552411200.084125758 1657216.6101434411807.127121968
1657175.07464083411923.6071182961657126.68134444 412076.31995005
 1656782.6233853412293.458750931
#Sta/Elev= 30
       0 1162.94    50.4 1143.85    85.2 1133.65   109.9 1113.63   135.5 1112.52
   221.5 1096.12   317.4 1062.31   356.1 1055.92     457 1025.59   516.1 1001.28
   583.7  991.75   604.8  984.46   714.9  979.37   730.5  975.66   736.3  975.22
     743  975.81   761.9  986.54   806.4  984.93     933   989.1   956.6 1003.28
   999.2 1020.09  1017.1 1030.94  1084.3 1063.45  1098.5  1064.9  1130.2 1084.88
  1155.3 1097.32  1174.2 1100.02  1237.5 1132.31  1306.7 1160.95  1332.1 1166.59
#Mann= 6, -1 ,  0
       0     0.1       0  661.36    0.05       0   730.5   0.045       0
     743    0.05       0  765.03    0.06       0  875.03     0.1       0
Bank Sta=730.5,743
XS Rating Curve= 0 ,0
Exp/Cntr(USF)=0,0
Exp/Cntr=0.3,0.1

Type RM Length L Ch R = 1 ,102696  ,184.6,185.6,189.6
BEGIN DESCRIPTION:
Structure 23 XS 2
END DESCRIPTION:
XS GIS Cut Line= 4
1657386.96038006411180.9886578241657173.00572783411730.558450814
1657114.54539713412006.4550735291656766.42049456412269.324897912
#Sta/Elev= 30
       0 1175.67    29.9 1166.49    63.6 1147.03    98.2 1139.11   136.9 1136.38
   196.5 1123.94   231.3 1113.65   308.6 1099.48   428.8 1060.79   497.4 1035.06
     558 1007.55   591.8  989.42   624.5  983.98   714.4   980.2   730.5  975.54
     739  975.17  745.19975.6585   767.7  986.14   845.3  985.22   871.8  991.77
   895.1 1006.11   970.1 1037.49   988.1 1042.89  1045.2 1073.27  1060.3 1074.82
  1090.3 1092.19  1110.4  1099.6  1125.4 1101.43  1200.5 1139.95    1308 1173.85
#Mann= 6, -1 ,  0
       0     0.1       0  689.75    0.05       0   730.5   0.045       0
  745.19    0.05       0  789.75    0.06       0  901.77     0.1       0
Bank Sta=730.5,745.19
XS Rating Curve= 0 ,0
Exp/Cntr(USF)=0,0
Exp/Cntr=0.3,0.1

Type RM Length L Ch R = 1 ,102510  ,500.8,499.8,497.7
BEGIN DESCRIPTION:
Structure 23 XS 1
END DESCRIPTION:
XS GIS Cut Line= 6
1657362.43579917411168.8866216691657278.72402434411351.421361595
 1657225.8980145411434.6167332531657020.14088009411721.750345334
1656828.99920201412024.6024299261656608.08527376412355.724471092
#Sta/Elev= 30
       0  1182.8    21.4 1177.74    95.4 1150.32   130.9 1148.59   179.9 1140.92
   254.3 1133.95   402.4 1100.67   422.5 1091.69   445.4 1076.97   511.3 1040.38
   568.7 1015.32   585.9 1003.67   616.7  977.12   683.7  975.52   695.2  972.94
   703.4   972.2  710.04972.8776   722.4  975.87   764.3  978.18   779.3  984.53
   811.2  984.51     836 1007.33   857.6 1021.31   892.5 1037.11  1001.2  1093.5
    1049 1110.66  1092.7 1133.58  1144.8 1156.62  1318.3 1212.79  1408.9 1232.32
#Mann= 6, -1 ,  0
       0     0.1       0  662.67    0.05       0   695.2   0.045       0
  710.04    0.05       0  782.67    0.06       0  898.06     0.1       0
Bank Sta=695.2,710.04
XS Rating Curve= 0 ,0
Exp/Cntr(USF)=0,0
Exp/Cntr=0.3,0.1

Type RM Length L Ch R = 1 ,102011  ,501.7,499.7,496.8
XS GIS Cut Line= 6
1656777.06754734410903.4964044241656722.85735393411099.935316011
1656698.54998784411196.2136667521656667.96835609411288.282052174
1656537.08804043411619.6196440911656285.61413392412219.606633082
#Sta/Elev= 30
       0 1269.18    88.4 1238.56   109.1 1224.09     134 1213.69   154.7  1211.4
   245.7 1171.28   278.7 1162.84   316.1 1144.87   345.6 1136.25   379.3 1121.39
   409.4 1104.21   447.6  1092.7   483.5 1067.64   589.5 1020.45   606.7 1015.16
   671.2   974.3     697  967.96   705.9  966.22  719.58968.1961   770.3  970.47
   791.5  976.59     831  976.06   891.7 1019.31  1018.1 1089.74  1054.4 1104.02
  1112.9 1132.58  1208.3 1166.08  1282.1 1196.97  1325.5 1207.94  1406.9 1238.21
#Mann= 6, -1 ,  0
       0     0.1       0     697   0.045       0  719.58     0.1       0
  766.35    0.07       0  786.35    0.06       0  871.37     0.1       0
Bank Sta=697,719.58
XS Rating Curve= 0 ,0
Exp/Cntr(USF)=0,0
Exp/Cntr=0.3,0.1

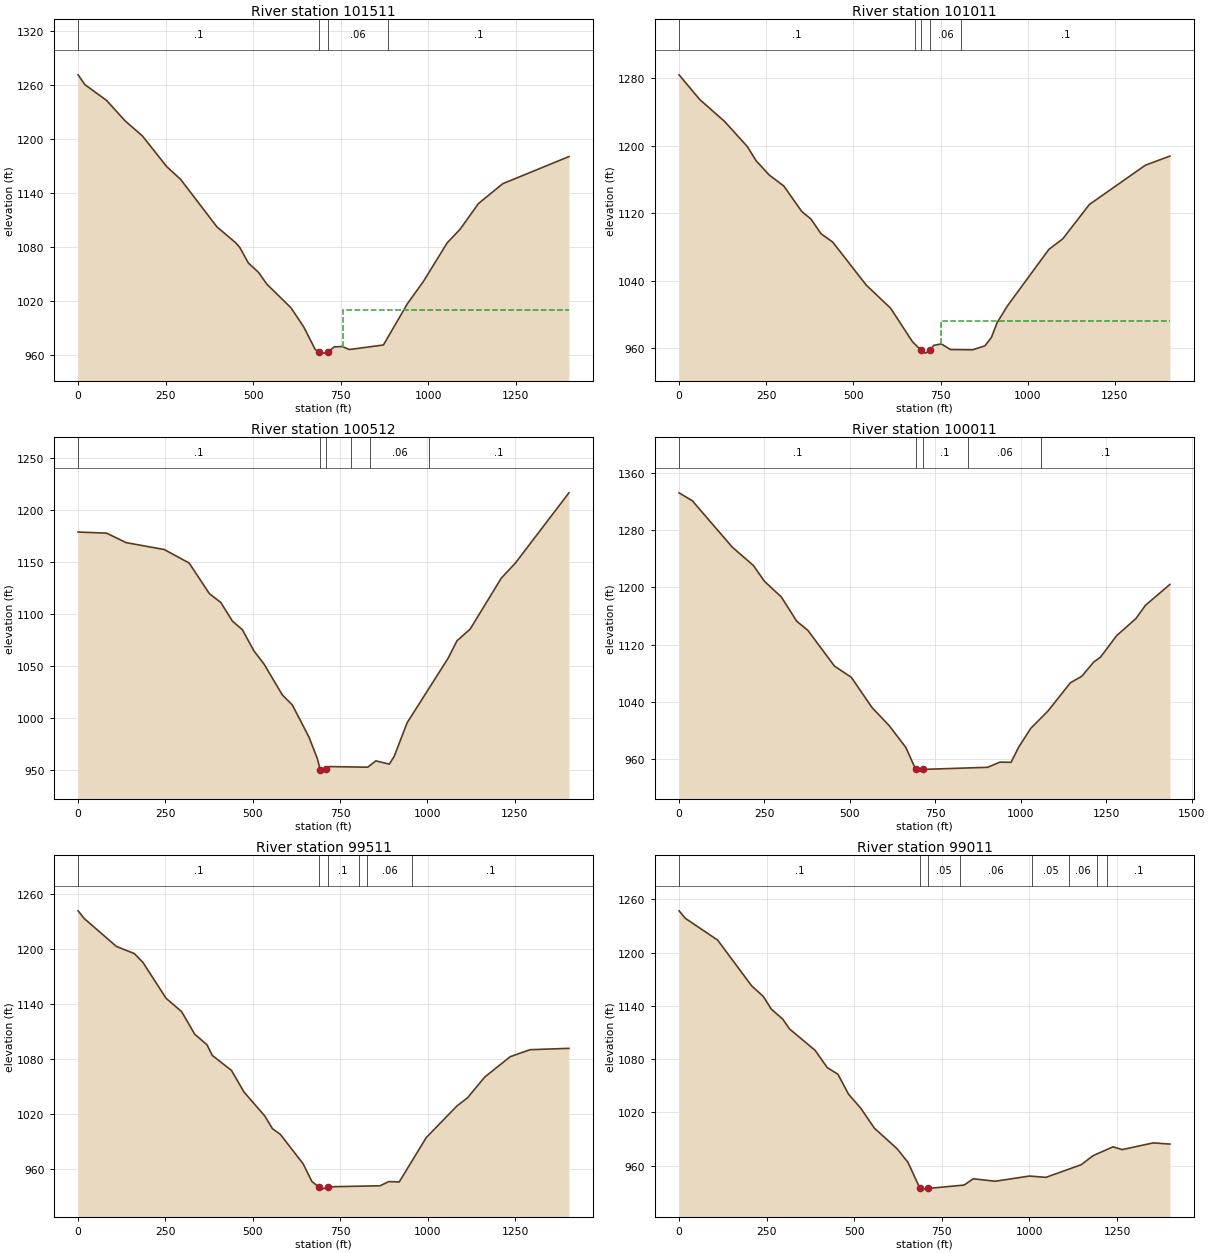
Type RM Length L Ch R = 1 ,101511  ,495.2,500,504.5
XS GIS Cut Line= 6
 1656218.5224046410761.3857962491656195.81050776410858.790785179
1656174.33548509410955.9411814211656132.94842875411147.096310928
1656114.32215367411239.0206677621655960.08000809 412138.78658475
#Sta/Elev= 30
       0 1271.22    19.7 1260.24    81.3 1242.78   134.6 1219.88   183.7 1203.24
   253.3 1169.01   292.8 1154.93   396.6 1102.03   449.6 1084.55   461.9 1079.08
   486.4 1061.79   514.8 1051.66   539.1  1038.3   608.1 1011.96   644.6  990.63
   677.1  965.75   689.3  962.38   701.5  961.56  712.94962.4349   731.2  968.45
   754.2  968.98   774.5  965.56   871.9   970.6   940.9 1016.75   985.5 1040.91
  1054.5 1084.45  1091.1  1099.4  1143.4 1127.99  1212.9 1150.09  1401.8 1180.26
#Mann= 4, -1 ,  0
       0     0.1       0   689.3   0.045       0  712.94    0.06       0
  886.39     0.1       0
#XS Ineff= 2 , 0
                          756.87         1009.74
Permanent Ineff=
       F       F
Bank Sta=689.3,712.94
XS Rating Curve= 0 ,0
Exp/Cntr(USF)=0,0
Exp/Cntr=0.3,0.1

Type RM Length L Ch R = 1 ,101011  ,494,499.3,504.5
XS GIS Cut Line= 6
1656051.57916893410688.0640925021655854.73343401410918.464222252
1655793.94976293410995.2869032621655690.14813326411144.267576426
1655648.33095968411206.6086590891655257.03974751411846.903310254
#Sta/Elev= 30
       0 1283.94    59.5  1254.6   130.5 1228.75   195.7 1198.97   221.2 1182.01
   258.6  1165.2   300.7 1152.03   351.9 1121.95   378.2 1113.04   407.4 1095.46
   440.6 1085.74     537 1034.64     607  1007.2   669.3  967.63  694.47957.3945
   706.8  953.99   720.9  957.29   730.2  963.16   752.3  964.94   778.5  958.24
   842.2  957.92   877.4  962.65   895.9  972.49   912.3  989.94   941.4 1009.63
  1060.7 1076.94  1100.6 1089.48  1177.1 1130.24  1337.8 1176.82    1408 1187.59
#Mann= 5, -1 ,  0
       0     0.1       0  677.65    0.06       0  694.47   0.045       0
   720.9    0.06       0  807.65     0.1       0
#XS Ineff= 2 , 0
                          749.96          992.24
Permanent Ineff=
       F       F
Bank Sta=694.47,720.9
XS Rating Curve= 0 ,0
Exp/Cntr(USF)=0,0
Exp/Cntr=0.3,0.1

Type RM Length L Ch R = 1 ,100512  ,506.5,500.7,491.4
XS GIS Cut Line= 6
1655899.53583784410484.1327418391655353.01462117410836.726524845
1655269.70835733410892.0604036751655057.61855842411039.614898592
1654976.94385101411094.7798145121654728.56770734411261.418588832
#Sta/Elev= 30
       0 1179.01    81.9 1177.91   137.4 1168.81   246.8 1162.16     318 1149.17
     376 1119.68   408.7 1111.17     442 1093.22   470.6 1084.91   503.3 1064.73
   532.5 1051.92   584.8 1022.24   613.4 1012.56   661.1  981.67   685.1  960.99
   693.4  950.22     700  948.81   709.1  950.38   718.7  953.19   829.5  952.59
   852.5  958.69   891.3  955.55   905.3  963.08   942.4  995.43  1059.4 1057.37
  1085.3 1074.39  1122.8 1085.55    1212 1134.63  1252.3 1149.12  1405.6 1216.74
#Mann= 6, -1 ,  0
       0     0.1       0   693.4   0.045       0   709.1     0.1       0
   780.4    0.05       0   835.8    0.06       0 1004.09     0.1       0
Bank Sta=693.4,709.1
XS Rating Curve= 0 ,0
Exp/Cntr(USF)=0,0
Exp/Cntr=0.3,0.1

Type RM Length L Ch R = 1 ,100011  ,494.6,500,504.8
XS GIS Cut Line= 6
1655133.97175217409824.235439584  1654957.002946410630.431005672
1654931.35043825   410714.3888431654895.31343684410803.790895179
1654844.00054733410894.2575777621654658.81751876 411158.42732501
#Sta/Elev= 30
       0 1332.12    38.8 1321.05   155.9 1256.21   217.4 1230.73   250.1 1208.51
   299.3 1186.71   344.3 1152.91   377.1 1140.02   454.9 1090.13     504 1074.65
   564.6 1032.39   614.6 1007.27   663.7  976.63   692.4  946.07   700.3  943.59
  712.44945.9859   902.9  948.92   938.8  956.16   971.6  955.92   993.1  976.47
  1028.8  1003.1    1080 1027.79  1145.1 1066.95  1178.7 1076.12  1213.3 1095.86
  1233.4 1102.82  1280.7 1132.82  1336.7 1156.49  1364.5 1174.98  1436.3 1204.23
#Mann= 5, -1 ,  0
       0     0.1       0   692.4   0.045       0  712.44     0.1       0
  845.39    0.06       0 1059.57     0.1       0
Bank Sta=692.4,712.44
XS Rating Curve= 0 ,0
Exp/Cntr(USF)=0,0
Exp/Cntr=0.3,0.1

Type RM Length L Ch R = 1 ,99511   ,503.2,500,496.9
XS GIS Cut Line= 6
1654919.98760009409773.2184812581654868.87680992409860.298687667
1654758.19724126410024.9755236661654215.38172585410748.723420009
1654163.45236775410833.7606514991654116.58435126410922.801155835
#Sta/Elev= 30
       0 1241.39    17.8 1232.92   109.7 1202.65   161.3  1194.8   185.6 1185.27
   251.8 1146.21   296.1 1131.81   333.9 1107.08   368.9 1095.62   383.9 1084.11
   438.9 1067.72   474.9 1044.14   533.9 1018.31   556.2 1004.32   578.9  998.11
   643.9  966.14   668.9  946.92   688.9  940.93   698.9  938.56   713.9  941.06
   863.9  942.21   888.9  946.74   918.9  946.42   996.2  994.64  1083.9 1029.03
  1113.9 1037.78  1163.9 1060.66  1236.7 1082.72  1292.9 1090.26  1404.4 1091.76
#Mann= 6, -1 ,  0
       0     0.1       0   688.9   0.045       0   713.9     0.1       0
  802.54    0.05       0  827.54    0.06       0  955.04     0.1       0
Bank Sta=688.9,713.9
XS Rating Curve= 0 ,0
Exp/Cntr(USF)=0,0
Exp/Cntr=0.3,0.1

Type RM Length L Ch R = 1 ,99011   ,497.4,500,500.8
XS GIS Cut Line= 6
1654332.80701593409519.9729247541654291.68078583409610.738491252
1654252.42331843409701.8652774991654214.31873584409792.628547415
1654106.65294068410049.0686513331653787.13750359410810.107155502
#Sta/Elev= 30
       0 1247.18    18.2 1238.67   110.3 1214.15   207.3 1162.61   240.8 1150.55
   263.1 1136.46   295.9 1125.15   315.4 1114.07   388.3 1090.03     423 1070.55
   453.4 1063.11   483.8 1040.55   518.5 1024.83   557.5 1002.29   622.6     979
   653.4  963.75   687.7  934.35   702.2  933.63   710.6934.3844   813.5  938.22
   839.7  945.28   902.3  942.52    1000  948.38    1047   946.9  1147.5   961.1
  1181.3  971.28  1238.6  981.32  1264.6  978.15    1353  985.72  1400.8   984.4
#Mann= 8, -1 ,  0
       0     0.1       0   687.7   0.045       0   710.6    0.05       0
  800.43    0.06       0 1006.68    0.05       0 1113.56    0.06       0
 1193.56    0.05       0    1222     0.1       0
Bank Sta=687.7,710.6
XS Rating Curve= 0 ,0
Exp/Cntr(USF)=0,0
Exp/Cntr=0.3,0.1