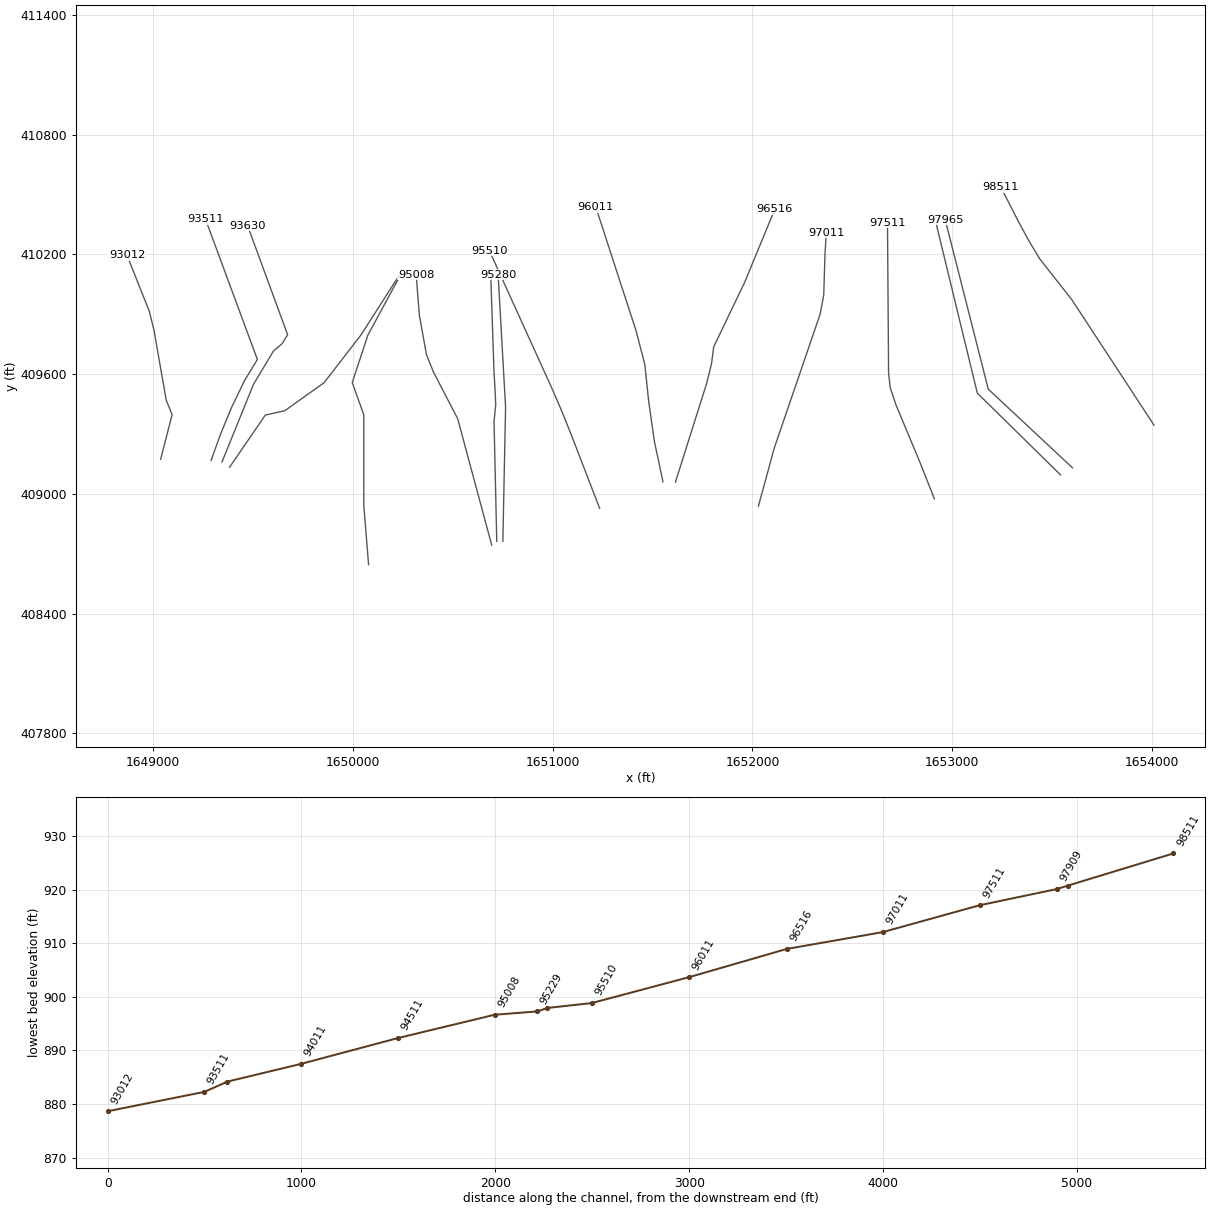
HEC-RAS study LTLFSHNGCK.prj: LTLFSHNGCK

--- LTLFSHNGCK.g01 (geometry) --- (continued)

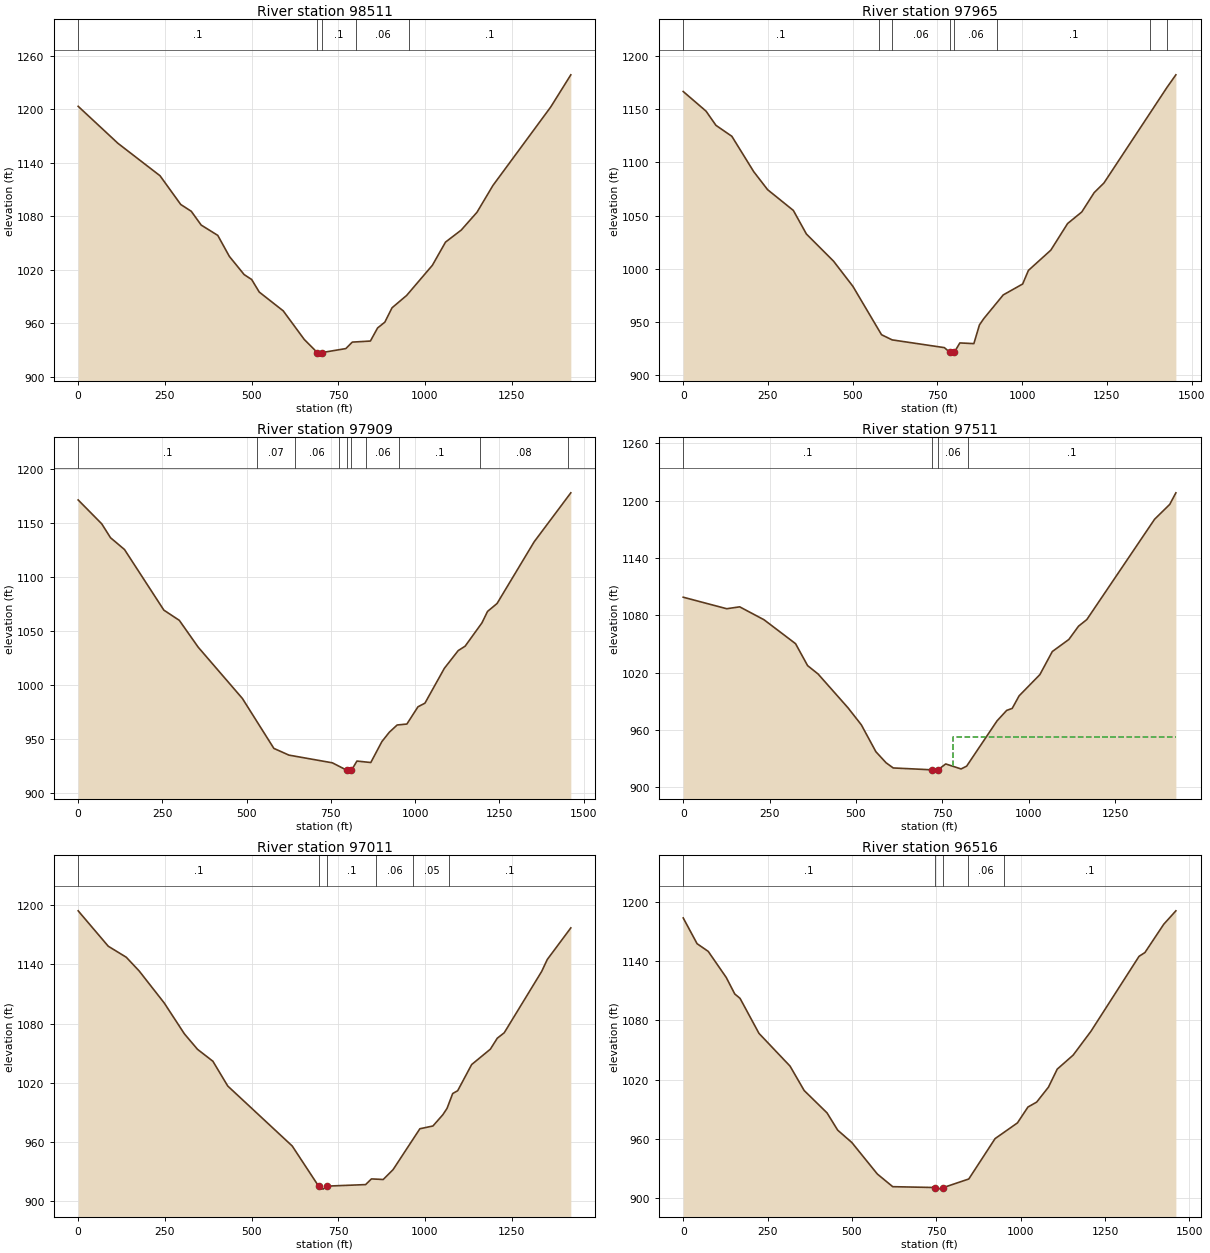
Type RM Length L Ch R = 1 ,98511   ,548.2,546.1,543.5
BEGIN DESCRIPTION:
Structure 22 XS 4
END DESCRIPTION:
XS GIS Cut Line= 6
1654010.05241209409343.7255738381653599.09621301 409971.58028926
1653438.26385751 410176.52476126 1653386.0359436410262.920257762
1653336.88151434410353.0040670931653243.07395917410536.274041757
#Sta/Elev= 30
       0 1203.35   114.7 1161.88     236 1125.55   295.7 1093.37   326.1 1085.73
   354.7 1070.28   402.5 1058.72     436 1035.14   478.7 1014.74   500.2 1009.31
   522.1  995.21   591.2  974.16   652.1  941.99   689.4  927.46   698.3  926.79
   704.1  927.48   771.7  931.88   790.3  939.13   842.5  940.32   863.3  954.99
   884.1  961.46   904.9  977.59   946.9  991.37  1021.3 1025.25  1059.1 1051.18
  1104.5  1064.7  1149.9 1084.66  1195.8 1114.64  1362.5 1202.63  1420.4 1238.64
#Mann= 5, -1 ,  0
       0     0.1       0   689.4   0.045       0   704.1     0.1       0
  800.39    0.06       0  954.76     0.1       0
Bank Sta=689.4,704.1
XS Rating Curve= 0 ,0
Exp/Cntr(USF)=0,0
Exp/Cntr=0.3,0.1

Type RM Length L Ch R = 1 ,97965   ,55.8,55.7,55.7
BEGIN DESCRIPTION:
Structure 22 XS 3
END DESCRIPTION:
XS GIS Cut Line= 3
1653601.52170295409130.5120094191653180.15689373409524.691992239
1652964.37733417 410374.21781728
#Sta/Elev= 30
       0  1166.5    67.4 1148.03    96.6 1134.71   143.5 1124.42   207.9 1091.26
   248.9 1074.31     325 1054.77   363.4 1032.67   443.9 1007.01   500.7  983.46
   585.1  938.05   616.4   933.2   770.4  925.93   786.9  921.49   791.4  920.76
   799.7  921.51   816.2  930.34   857.5  929.69     874  947.28   886.5  953.07
   944.1  975.41  1001.5   985.7  1018.4  998.44  1084.5 1017.45    1134 1042.46
  1175.9 1053.35  1212.4 1071.49  1241.3 1080.56    1427 1170.21  1453.5 1182.16
#Mann= 8, -1 ,  0
       0     0.1       0     577    0.07       0     617    0.06       0
   786.9   0.045       0   799.7    0.06       0     927     0.1       0
    1377    0.08       0    1427     0.1       0
Bank Sta=786.9,799.7
XS Rating Curve= 0 ,0
Exp/Cntr(USF)=0,0
Exp/Cntr=0.3,0.1

Type RM Length L Ch R = 1 ,97909   ,399.3,398.2,395.7
BEGIN DESCRIPTION:
Structure 22 XS 2
END DESCRIPTION:
XS GIS Cut Line= 4
 1653542.0548952409094.8319247681653125.78724093409504.303372438
1653113.89387937 409551.876818641652918.50293961410357.227300779
#Sta/Elev= 30
       0 1171.03    70.1 1148.87    95.9 1136.09   137.4 1125.18   254.3 1069.07
   300.1 1059.63   356.1 1034.81   487.3  987.34   580.6  941.17   625.4  934.94
   754.2  927.81   798.3  920.76   802.4  920.13   810.6  920.75   827.1  929.44
   868.2  928.09   901.2   947.5   923.1  956.09   946.4  962.81   975.3   963.7
  1008.2  979.66  1028.8  982.99  1086.4 1015.21  1127.5 1031.63  1148.1 1035.73
  1198.1 1057.35  1214.6 1067.89  1242.8  1075.2    1353 1132.34  1461.7 1177.62
#Mann= 10, -1 ,  0
       0     0.1       0     530    0.07       0  642.94    0.06       0
  772.94    0.05       0   798.3   0.045       0   810.6    0.05       0
  852.94    0.06       0  952.94     0.1       0 1192.94    0.08       0
 1452.94     0.1       0
Bank Sta=798.3,810.6
XS Rating Curve= 0 ,0
Exp/Cntr(USF)=0,0
Exp/Cntr=0.3,0.1

Type RM Length L Ch R = 1 ,97511   ,504,500,494.2
BEGIN DESCRIPTION:
Structure 22 XS 1
END DESCRIPTION:
XS GIS Cut Line= 6
1652910.47652726408975.1183714271652834.84610109409166.397188336
1652718.01398568409446.1650015121652689.28438434409532.831822917
1652681.25388859409607.7762268331652675.89267884 410358.14775759
#Sta/Elev= 30
       0  1099.1     126 1087.04   163.4 1089.03   233.9 1075.51   325.2 1050.47
     360 1027.54   390.4 1018.75   476.9  983.41   515.6  965.53   557.7  937.43
   587.2  925.84   607.9  920.44   720.3  918.46   728.3  917.11  737.66918.5488
   759.8  924.63   804.3  919.39   820.4  922.32   908.3  969.67   936.3  980.66
   952.3  982.76   972.3   995.9  1032.3 1018.08  1068.3 1042.24  1116.3 1054.91
  1144.3 1068.81  1168.3 1075.73  1364.3 1180.64  1408.3 1196.24    1426 1208.33
#Mann= 4, -1 ,  0
       0     0.1       0   720.3   0.045       0  737.66    0.06       0
  825.56     0.1       0
#XS Ineff= 2 , 0
                          782.17           952.5
Permanent Ineff=
       F       F
Bank Sta=720.3,737.66
XS Rating Curve= 0 ,0
Exp/Cntr(USF)=0,0
Exp/Cntr=0.3,0.1

Type RM Length L Ch R = 1 ,97011   ,493.3,495.2,489.7
XS GIS Cut Line= 6
1652029.89397085408938.4954131691652109.05326134409229.034530252
1652338.78541343409900.2323348371652356.81293643   409996.256421
1652363.02322584410201.5220865911652369.71054843410308.442148343
#Sta/Elev= 30
       0 1194.43    86.8 1158.51   138.7 1147.36     176 1133.38   248.2 1100.94
   306.3 1069.65   344.2 1053.92   388.5 1041.84   431.4 1016.69   617.3  955.86
   693.5  915.07   706.2  912.09  717.35915.1326   828.9  916.68   845.8  922.46
   879.8  921.87   908.1  931.82   985.5  973.35  1023.1  976.14  1051.6  987.53
  1063.8  993.99  1080.1 1009.07  1094.5 1011.93  1134.8 1038.47  1188.7 1054.06
  1208.7 1065.18  1228.7  1070.7  1336.8 1132.97  1352.8    1145  1420.8 1177.14
#Mann= 6, -1 ,  0
       0     0.1       0   693.5   0.045       0  717.35     0.1       0
  859.32    0.06       0  966.82    0.05       0 1070.57     0.1       0
Bank Sta=693.5,717.35
XS Rating Curve= 0 ,0
Exp/Cntr(USF)=0,0
Exp/Cntr=0.3,0.1

Type RM Length L Ch R = 1 ,96516   ,491.4,505,503.9
XS GIS Cut Line= 6
 1651614.5355496409058.7769967621651771.25570859 409555.02042684
1651795.27108051409652.7387353331651805.79107259409735.967243418
1651960.84883334410059.0991430881652111.90200892410425.762123674
#Sta/Elev= 30
       0 1183.76    41.1 1157.66    74.1 1149.87   127.5 1123.44   152.8 1106.69
   168.4 1102.28   224.5 1066.79   316.6 1033.61   358.5 1008.86   426.2  986.21
   457.8   968.7   499.8  956.17   575.3  924.25   620.9  911.43   745.2910.5825
   754.4  908.95   769.6  910.37   846.3  919.22   924.2  960.13   990.5  976.06
  1021.6  992.14  1047.5  997.15  1082.4  1012.3  1108.4 1030.53  1155.6 1044.75
  1208.2 1068.85    1351 1144.91  1368.2 1148.65  1424.2 1177.42    1460 1190.97
#Mann= 5, -1 ,  0
       0     0.1       0   745.2   0.045       0   769.6     0.1       0
  845.16    0.06       0  950.63     0.1       0
Bank Sta=745.2,769.6
XS Rating Curve= 0 ,0
Exp/Cntr(USF)=0,0
Exp/Cntr=0.3,0.1

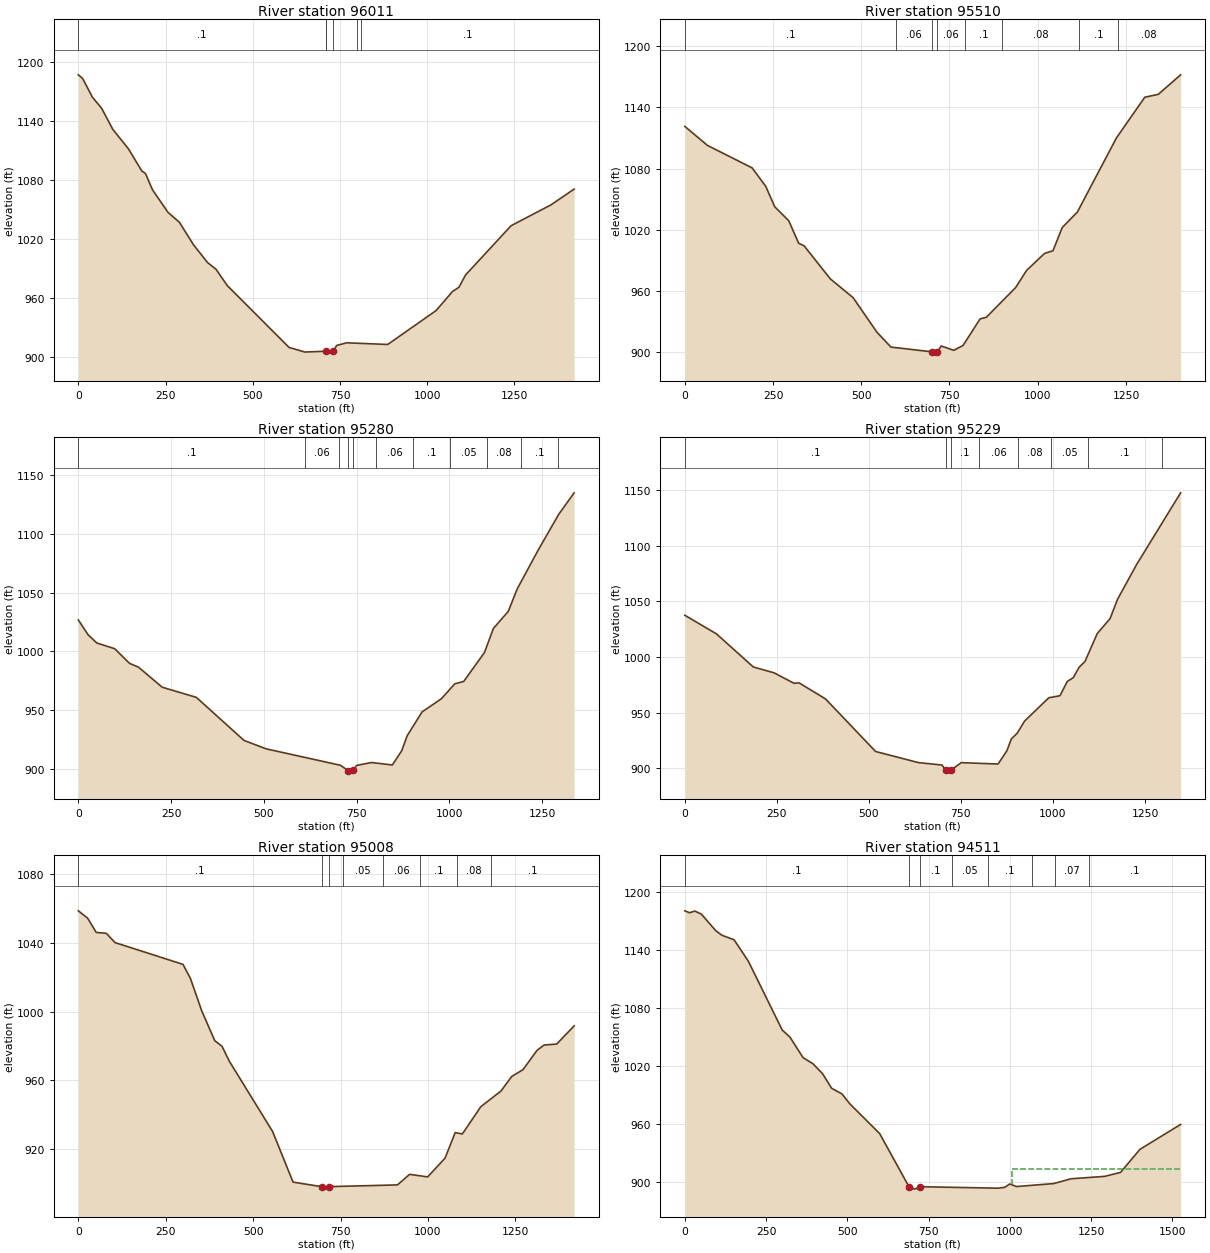
Type RM Length L Ch R = 1 ,96011   ,498.3,500.5,501.6
XS GIS Cut Line= 6
1651552.24302326409060.4515340921651509.20931667409262.128624171
1651480.58503009 409462.954009921651461.36951734409647.658364922
1651417.47984134409817.0655064281651215.93398459410436.457640335
#Sta/Elev= 30
       0 1186.74    12.4 1183.04    40.1 1164.13    66.8 1152.72    98.7 1131.33
   143.5 1111.54   181.9    1089   192.4 1086.35   212.7 1069.71   257.2  1046.8
   289.6 1036.81     330 1013.93   370.4  995.79   394.6  989.02   426.8  972.45
     604  909.45   649.4  904.78     710905.6046   715.5  903.67   731.2  905.76
   740.3  911.45   769.3  914.17   886.8  912.48  1025.8  947.05  1072.1  966.22
    1091  970.67    1110  983.19  1240.5 1033.29    1354 1054.32  1421.2  1070.5
#Mann= 6, -1 ,  0
       0     0.1       0  709.82    0.07       0     710   0.045       0
   731.2    0.07       0  799.82    0.06       0  809.82     0.1       0
Bank Sta=710,731.2
XS Rating Curve= 0 ,0
Exp/Cntr(USF)=0,0
Exp/Cntr=0.3,0.1

Type RM Length L Ch R = 1 ,95510   ,232.1,229.8,227.2
BEGIN DESCRIPTION:
Structure 21.5 XS 4
END DESCRIPTION:
XS GIS Cut Line= 6
1651235.35979876 408926.70836325  1651092.404376409297.563592672
1651057.46284483409385.1500316711651023.48062934409466.142651841
1650993.35240875409535.0349025131650683.33137526410218.139507428
#Sta/Elev= 30
       0 1121.37    64.2 1102.72   190.6 1080.69   229.2 1062.64   254.9 1042.48
   294.7  1028.7   322.6 1006.69   338.1 1004.14   412.3  971.76   476.9  953.29
   544.3  919.45     584  904.79  699.46900.1707   709.2  898.85   715.3  900.21
   726.8  905.87     762  901.58   788.4  906.35   836.7  932.45   854.3  934.02
   937.6  963.27   968.4  980.03  1019.3  996.69  1043.1   999.3  1069.4 1022.08
  1112.3 1037.31  1223.1 1110.09  1303.4 1149.99  1341.7 1152.83  1404.9 1171.98
#Mann= 8, -1 ,  0
       0     0.1       0  599.59    0.06       0  699.46   0.045       0
   715.3    0.06       0  794.86     0.1       0  899.84    0.08       0
 1117.83     0.1       0 1226.22    0.08       0
Bank Sta=699.46,715.3
XS Rating Curve= 0 ,0
Exp/Cntr(USF)=0,0
Exp/Cntr=0.3,0.1

Type RM Length L Ch R = 1 ,95280   ,51,51,50.4
BEGIN DESCRIPTION:
Structure 21.5 XS 3
END DESCRIPTION:
XS GIS Cut Line= 3
1650750.75435343408762.4461201421650764.34676663409435.270573577
1650726.96763033410097.900717112
#Sta/Elev= 30
       0 1026.83    26.1 1014.25    49.7 1007.19    98.1 1002.27   138.1  989.77
   162.1  986.58   226.1  969.46   318.2   960.8   446.5  924.14   506.2  916.93
   706.3  902.94   727.5  898.42   734.3  897.93  740.14898.5421   750.4  902.83
   790.4  905.27   846.5  903.16   871.6   915.2   886.6  928.15   926.6  948.42
   978.7  959.63  1014.8  972.36  1038.8  974.35  1094.9  999.06  1118.9 1019.59
    1159  1034.1    1183 1053.18  1239.1 1086.05  1295.2 1116.95  1336.6 1135.16
#Mann= 11, -1 ,  0
       0     0.1       0     610    0.06       0  702.96     0.1       0
   727.5   0.045       0  740.14     0.1       0  802.96    0.06       0
  902.96     0.1       0 1002.96    0.05       0 1102.96    0.08       0
 1192.96     0.1       0 1292.96    0.08       0
Bank Sta=727.5,740.14
XS Rating Curve= 0 ,0
Exp/Cntr(USF)=0,0
Exp/Cntr=0.3,0.1

Type RM Length L Ch R = 1 ,95229   ,217.4,221,225
BEGIN DESCRIPTION:
Structure 21.5 XS 2
END DESCRIPTION:
XS GIS Cut Line= 6
1650720.17142373408762.4461201421650706.57901053409362.211352624
1650715.07426878409447.1639351281650711.67616548409521.922207732
1650706.57901053409606.8747902361650689.58849403410108.095027012
#Sta/Elev= 30
       0 1037.48    86.1 1020.71   186.1  990.95   242.2  985.74   296.8  976.27
   310.2   976.7   382.2  962.25   518.2  914.95   634.4  904.97   698.7  902.77
   708.8  898.08   714.7  897.29   722.7  898.09   750.7  904.91   850.9  903.68
   874.9  915.68   886.9  926.25   902.9  931.43   922.9  942.31   988.6  963.25
    1019  965.11    1039     978    1055  981.33    1071  990.69    1087  995.92
  1120.2 1020.99  1155.1 1034.47  1175.1 1051.67  1227.1 1083.06  1346.7 1147.57
#Mann= 8, -1 ,  0
       0     0.1       0   708.8   0.045       0   722.7     0.1       0
  800.13    0.06       0  905.24    0.08       0  995.24    0.05       0
 1095.24     0.1       0 1295.24    0.08       0
Bank Sta=708.8,722.7
XS Rating Curve= 0 ,0
Exp/Cntr(USF)=0,0
Exp/Cntr=0.3,0.1

Type RM Length L Ch R = 1 ,95008   ,498.8,497.5,485.2
BEGIN DESCRIPTION:
Structure 21.5 XS 1
END DESCRIPTION:
XS GIS Cut Line= 6
1650694.97505276408743.116866916  1650524.629921409376.207792342
1650403.80404717409609.3234678361650368.40451168409696.697308838
1650332.97151168 409893.932806761650316.60441843 410098.40779151
#Sta/Elev= 30
       0 1058.71    26.6 1054.43    51.2 1046.14    80.1 1045.61     105 1040.21
   299.4 1027.53   320.9  1019.2   353.1  1000.4   390.3   983.1     411  979.85
   431.6  971.24   555.8   930.2   614.2  900.75   696.5  898.07   709.5  896.66
  717.64898.1069   912.9  899.12   947.6  905.27   999.4  903.78    1049  914.72
    1078  929.57  1098.5  928.78  1151.2  944.63  1209.1  953.81  1239.8  962.27
    1272  966.23    1312  977.44  1332.2  980.56  1368.3  981.12  1418.3  991.74
#Mann= 8, -1 ,  0
       0     0.1       0   696.5   0.045       0  717.64     0.1       0
  755.67    0.05       0   870.7    0.06       0  978.28     0.1       0
 1082.56    0.08       0 1181.56     0.1       0
Bank Sta=696.5,717.64
XS Rating Curve= 0 ,0
Exp/Cntr(USF)=0,0
Exp/Cntr=0.3,0.1

Type RM Length L Ch R = 1 ,94511   ,513.2,500,484.5
XS GIS Cut Line= 6
1650078.60030125408645.8214578331650054.73551959408942.609906256
1650054.73551959409395.734984249 1649996.8534175409557.768452838
1650075.28009792409795.3808384981650242.70003867410104.617752835
#Sta/Elev= 30
       0 1180.98    14.8    1179    30.9 1180.73      51 1177.58    95.2 1160.43
   114.3 1155.64   151.7 1150.93   195.6 1128.68   299.7 1057.42   323.7 1049.93
   363.7 1028.81   394.4 1022.31   423.7 1012.19   451.7  996.99   483.7     991
   507.7  980.82   599.7  949.91  689.72894.8973   707.7  892.32   723.7  894.84
   962.9   893.3   984.3  894.14    1000  897.69  1020.5     895  1134.8  898.06
  1188.8  903.06  1291.9  905.55    1341  909.72  1400.6  933.61  1525.7  959.43
#Mann= 8, -1 ,  0
       0     0.1       0  689.72   0.045       0   723.7     0.1       0
  820.94    0.05       0  933.01     0.1       0 1067.61    0.05       0
 1137.61    0.07       0 1244.01     0.1       0
#XS Ineff= 2 , 0
                         1005.96          912.73
Permanent Ineff=
       F       F
Bank Sta=689.72,723.7
XS Rating Curve= 0 ,0
Exp/Cntr(USF)=0,0
Exp/Cntr=0.3,0.1

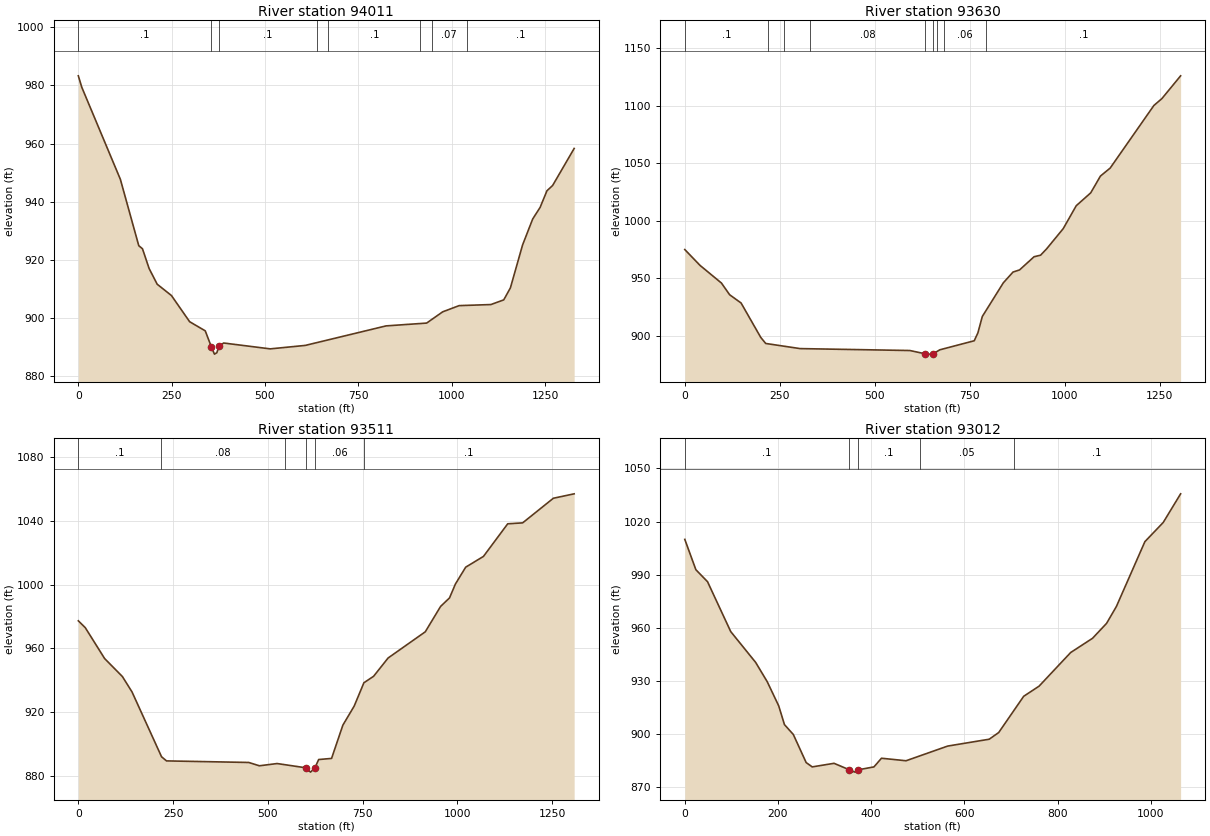
Type RM Length L Ch R = 1 ,94011   ,379.3,380.6,380
XS GIS Cut Line= 6
1649382.76223636409133.1075110341649561.91334251409394.651325002
1649659.48532584409416.554168344 1649855.8225316409556.583743915
1650040.02229442409795.0845792591650238.29256718410104.580679417
#Sta/Elev= 30
       0  983.33     9.2  979.41   112.6   947.7   161.9  924.84   171.8  923.79
   189.7  916.96   211.2  911.58   249.4  907.68   298.2  898.66     340  895.52
356.4282889.9774   364.6   887.5   370.9  887.96376.9282890.1785   389.2  891.33
   514.1  889.31   607.9   890.5   824.3  897.22     933  898.19   976.1  902.07
  1020.1   904.2  1105.2  904.57  1139.6  906.18  1157.4  910.31    1190  925.08
  1217.2  934.05    1237  938.02  1255.3  943.75  1270.6  945.58  1328.2  958.32
#Mann= 8, -1 ,  0
       0     0.1       0356.4282   0.045       0376.9282     0.1       0
  638.35    0.05       0  669.08     0.1       0  916.57    0.08       0
  946.57    0.07       0 1040.58     0.1       0
Bank Sta=356.4282,376.9282
XS Rating Curve= 0 ,0
Exp/Cntr(USF)=0,0
Exp/Cntr=0.3,0.1

Type RM Length L Ch R = 1 ,93630   ,110.8,119.4,133.9
XS GIS Cut Line= 6
  1649344.774927409159.1756856451649502.27701496409547.578892854
1649601.67153649409714.2558597271649646.01678456409752.484521854
1649673.54142129409796.8297699211649473.22323174410342.735065093
#Sta/Elev= 30
       0  975.01    40.3   961.2    96.4  945.95     118  935.78   148.2  928.59
     200   898.7     213  893.44   303.6  888.98   592.6  887.31  633.19884.4342
   644.9  884.18   653.4  884.44   671.7  887.96     762  895.78   771.6   902.6
   783.3  916.89   838.7  946.15   864.2  955.48   881.3  957.31   919.6  968.78
   936.7  970.12   952.4  975.55   996.3  993.18  1030.6  1013.1  1068.7 1024.27
  1094.3 1038.85  1119.9 1045.78  1234.9 1100.12  1256.2 1106.19  1305.4 1125.92
#Mann= 9, -1 ,  0
       0     0.1       0     220    0.08       0     260     0.1       0
     330    0.08       0  633.19   0.045       0   653.4    0.08       0
  663.19    0.07       0  681.73    0.06       0  793.93     0.1       0
Bank Sta=633.19,653.4
XS Rating Curve= 0 ,0
Exp/Cntr(USF)=0,0
Exp/Cntr=0.3,0.1

Type RM Length L Ch R = 1 ,93511   ,499.3,498.6,496.4
XS GIS Cut Line= 6
1649290.41519783409167.1914780891649337.01188943409297.152832344
1649393.32247233409433.7440945951649457.92831425409567.587658927
1649522.08304159409673.1258336751649261.96151459410376.988599166
#Sta/Elev= 30
       0  977.29    18.4  972.96    69.4  953.59   116.2  942.31   141.7  932.62
   219.6  891.91   232.6  889.31   449.6  888.33   477.7  886.24   524.5  887.65
599.9872884.9923   612.7  882.26624.3873884.9714   634.1  890.16   668.2  890.87
     698  911.76   727.9  923.74   753.5  938.38   779.1  942.45   817.4  953.94
   915.5  970.39   955.9  986.33   979.5   991.7   994.9 1000.36  1022.1 1010.97
    1069 1017.74    1133 1038.22  1172.4  1038.8  1253.4 1054.26  1308.3 1057.04
#Mann= 6, -1 ,  0
       0     0.1       0  218.06    0.08       0  544.43    0.06       0
599.9872   0.045       0624.3873    0.06       0  752.93     0.1       0
Bank Sta=599.9872,624.3873
XS Rating Curve= 0 ,0
Exp/Cntr(USF)=0,0
Exp/Cntr=0.3,0.1

Type RM Length L Ch R = 1 ,93012   ,511.9,506.7,496.4
XS GIS Cut Line= 6
1649037.93717257409173.5792062011649095.42444609409396.702502012
1649065.79130326409469.6328023371649004.41314517409820.950669259
1648980.79639451409915.1827642621648869.62404467410194.889553919
#Sta/Elev= 30
       0 1009.91    23.8   992.8    48.8  986.05    98.6  957.91   152.2  940.49
   176.9  929.65   201.5  916.06   213.9  905.44   232.9  899.89   260.5  884.03
   273.5   881.6   320.3  883.62352.9264879.9866   365.1  878.65372.7664879.9912
   405.9  881.59   422.1  886.49   474.8  885.06   564.1  893.34   653.3  897.21
   673.7  900.98   727.3  921.42   760.3  927.13   828.1   946.1     875  954.12
   905.2  962.55   926.3  972.09   987.4 1008.63  1026.7 1019.43  1064.1 1035.61
#Mann= 5, -1 ,  0
       0     0.1       0352.9264   0.045       0372.7664     0.1       0
   504.6    0.05       0  705.85     0.1       0
Bank Sta=352.9264,372.7664
XS Rating Curve= 0 ,0
Exp/Cntr(USF)=0,0
Exp/Cntr=0.3,0.1