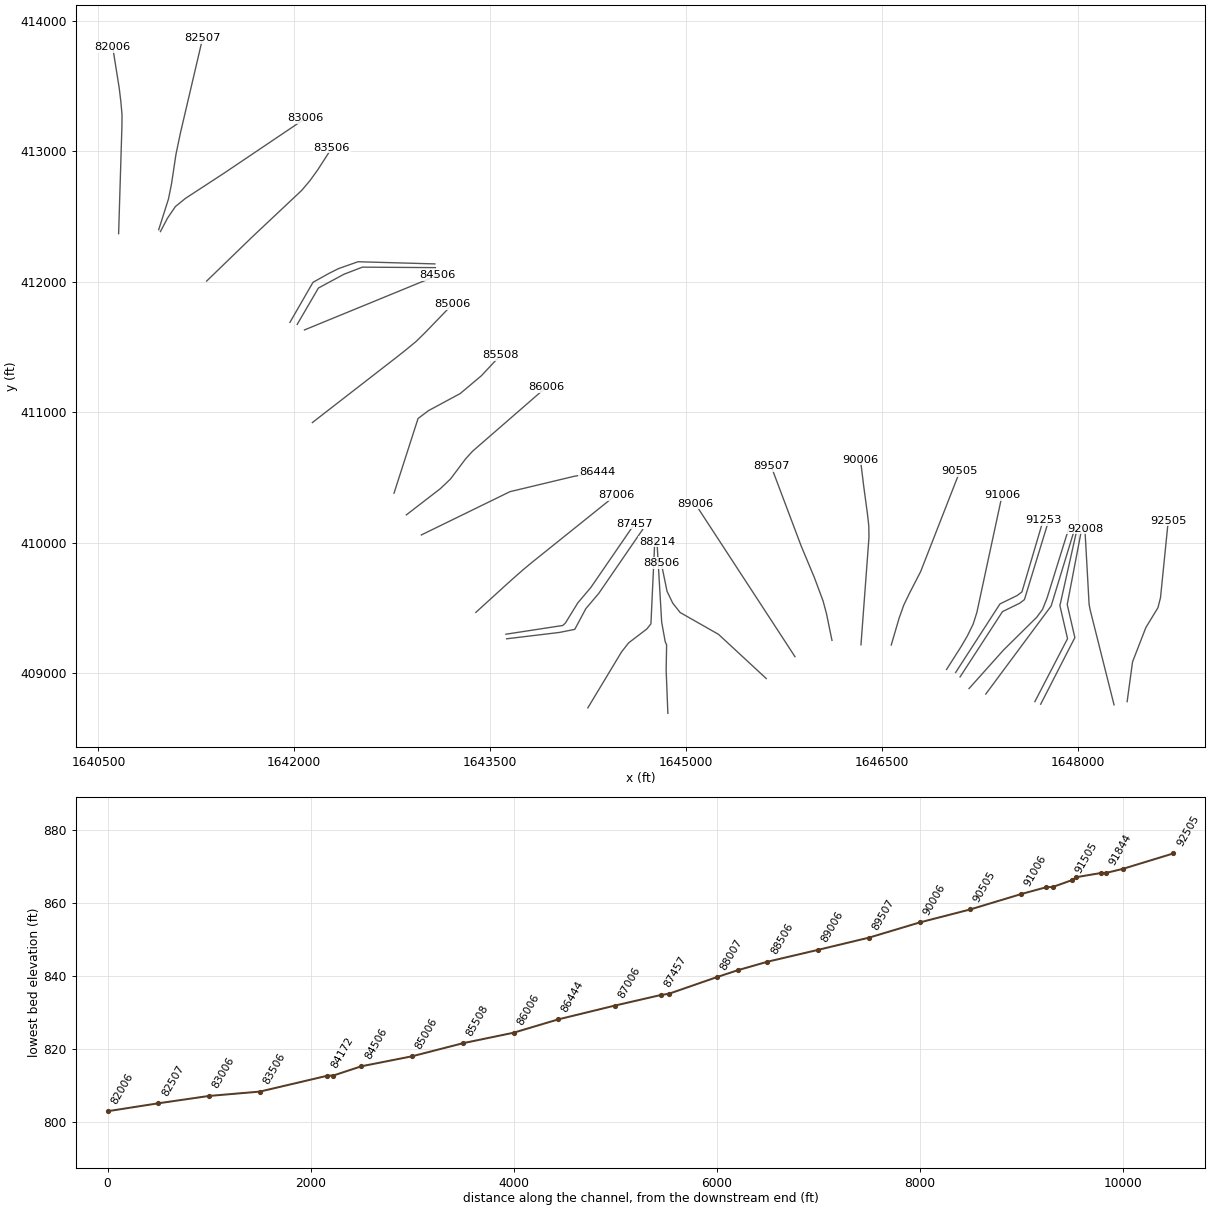
HEC-RAS study LTLFSHNGCK.prj: LTLFSHNGCK

--- LTLFSHNGCK.g01 (geometry) --- (continued)

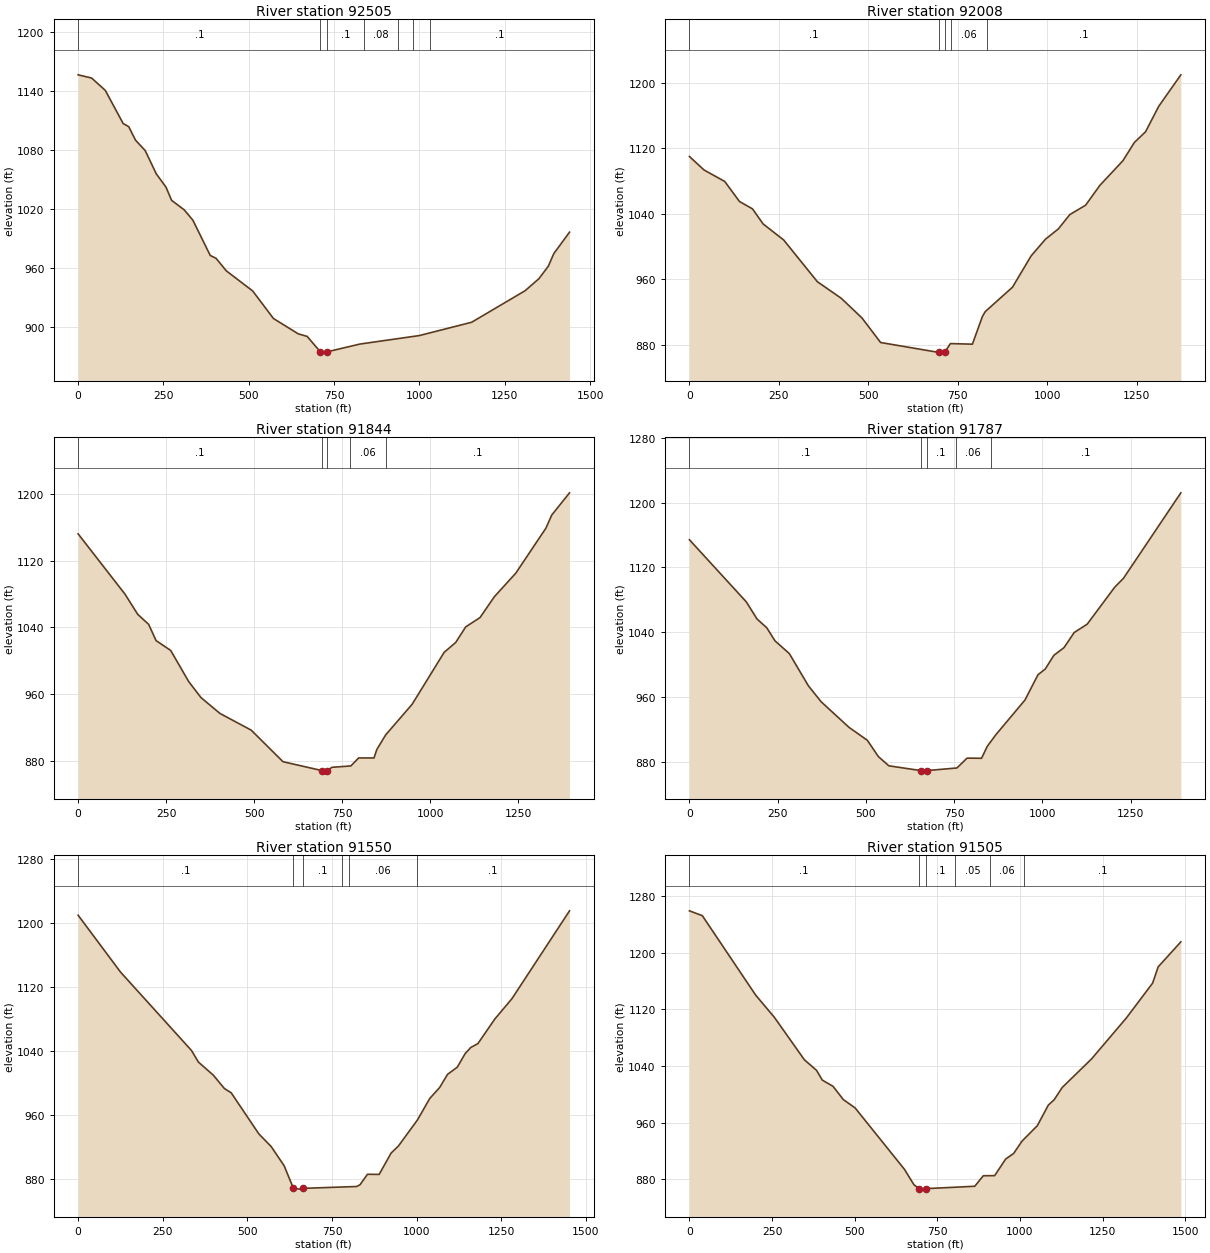
Type RM Length L Ch R = 1 ,92505   ,490,497.9,505.2
XS GIS Cut Line= 6
1648378.73230992408781.0711873321648420.18301442409086.156207085
1648522.30026425409349.5382262621648614.52744201 409500.80301559
1648634.32661501409578.1220866741648693.47511876 410166.51821959
#Sta/Elev= 30
       0 1156.78    39.6 1153.52    79.7 1140.95     132 1107.26   148.3 1104.04
   168.3 1090.28   196.5 1079.78     229 1056.09   257.6 1042.49     274 1029.06
   310.8 1019.47   336.3  1008.9   387.2  973.02   404.2  970.16   434.2  957.37
   511.6  936.91   572.4  908.89   644.9  893.31   671.1  890.68  709.94874.9808
   719.6  873.68   728.7  874.95   825.9  882.91   999.9  891.55  1153.1  905.08
  1309.6  937.13  1350.3  949.43  1377.8  962.13  1393.8   974.9  1439.9  996.72
#Mann= 7, -1 ,  0
       0     0.1       0  709.94   0.045       0   728.7     0.1       0
  838.39    0.08       0   938.2     0.1       0  980.35    0.07       0
 1030.35     0.1       0
Bank Sta=709.94,728.7
XS Rating Curve= 0 ,0
Exp/Cntr(USF)=0,0
Exp/Cntr=0.3,0.1

Type RM Length L Ch R = 1 ,92008   ,163.7,163.8,163.6
BEGIN DESCRIPTION:
Structure 21 XS 4
END DESCRIPTION:
XS GIS Cut Line= 6
1648278.40737934408756.8304221781648182.33408067409139.082610428
1648159.48242034409230.005000755  1648095.496984409484.587168753
1648087.45460076409526.6066711911648055.23176376410106.401896492
#Sta/Elev= 30
       0 1110.12    40.9 1093.59    98.7 1079.56   139.9 1055.06   176.3 1046.01
     206 1027.58   263.7 1007.86   357.6   956.9   424.5  936.56   482.3  912.53
   534.5  882.45   697.1  870.31     705  869.44   713.2  870.24   729.7  881.11
   791.1  880.39   819.1  914.26   827.2  920.31   903.3  950.16   955.4  988.49
   995.5 1008.91  1031.5  1021.5  1063.5    1039  1107.6 1050.48  1147.6 1074.82
  1211.9 1104.91  1243.8 1127.18  1275.3 1140.41  1311.9  1171.4  1373.9 1210.07
#Mann= 5, -1 ,  0
       0     0.1       0   697.1   0.045       0   713.2     0.1       0
  730.39    0.06       0  833.17     0.1       0
Bank Sta=697.1,713.2
XS Rating Curve= 0 ,0
Exp/Cntr(USF)=0,0
Exp/Cntr=0.3,0.1

Type RM Length L Ch R = 1 ,91844   ,56.5,56.5,56.5
BEGIN DESCRIPTION:
Structure 21 XS 3
END DESCRIPTION:
XS GIS Cut Line= 4
1647716.69927008408761.8481409511647978.37293625409272.193055097
1647919.86205437409525.740209895 1648025.5067022410078.342983173
#Sta/Elev= 30
       0 1151.95   133.4 1079.75   169.3 1055.77   200.4 1043.78   221.5 1024.37
   263.1 1012.54   314.3  975.32   349.1  956.24   403.1  937.27   491.9  917.29
   582.1  879.61   692.9  868.96   701.1  868.33   705.8  868.87   721.7  872.92
     775  874.52     797  884.08   840.7  884.07   848.8  894.22   873.9  911.62
   949.2  948.31  1040.2 1010.36  1072.8 1022.05  1101.3 1040.72    1142 1051.86
  1182.7 1076.77  1243.8 1105.04  1329.3 1158.78  1345.7 1174.37  1396.3 1200.96
#Mann= 5, -1 ,  0
       0     0.1       0   692.9   0.045       0   705.8     0.1       0
  773.52    0.06       0  873.73     0.1       0
Bank Sta=692.9,705.8
XS Rating Curve= 0 ,0
Exp/Cntr(USF)=0,0
Exp/Cntr=0.3,0.1

Type RM Length L Ch R = 1 ,91787   ,244.3,236.9,221.5
BEGIN DESCRIPTION:
Structure 21 XS 2
END DESCRIPTION:
XS GIS Cut Line= 4
1647672.00345753408781.3517682441647922.30000778409264.066543725
1647863.78912591409517.6136985231647992.18800558410091.345401368
#Sta/Elev= 30
       0 1154.09   161.3 1077.26   191.4 1056.24   219.1 1045.36   242.4 1029.17
   282.9 1013.53     337  973.65   373.3  953.87   452.1  922.32   503.9   906.4
   535.3  886.21   564.8  874.86   656.4868.8807   663.3  868.28   671.5   868.9
   757.7  872.19   786.4  884.35   827.4  884.15   843.8  899.03   868.4  913.48
   950.4  956.11   987.3  987.35  1007.8   994.4  1032.4 1011.37  1061.1 1020.89
  1089.8 1039.48  1126.7 1049.84  1204.6 1095.48  1229.1 1106.29  1391.9 1212.04
#Mann= 5, -1 ,  0
       0     0.1       0   656.4   0.045       0   671.5     0.1       0
  753.75    0.06       0  853.96     0.1       0
Bank Sta=656.4,671.5
XS Rating Curve= 0 ,0
Exp/Cntr(USF)=0,0
Exp/Cntr=0.3,0.1

Type RM Length L Ch R = 1 ,91550   ,46.9,45.6,42.9
BEGIN DESCRIPTION:
Structure 21 XS 1
END DESCRIPTION:
XS GIS Cut Line= 3
1647296.39610193 408839.862650121647796.66414198409514.200563747
 1647975.1223317410099.309382512
#Sta/Elev= 30
       0 1209.64   125.4 1138.46   334.8 1040.54   355.3 1026.05   399.3 1009.67
     432  992.96   452.1  987.63   533.8  936.24   570.2  920.41   608.5  896.39
  636.01 868.078   655.1  867.16  662.82868.1051   822.6  870.44   832.6  872.64
   854.6  885.71   889.1  885.55   924.4   912.2   946.3  921.23  1002.3   953.7
  1038.6  980.51  1067.9  994.24    1091 1010.61  1119.9 1019.67  1143.2 1036.64
  1159.9  1044.3  1180.8 1049.11    1231 1079.98  1281.2  1105.2  1451.4 1215.11
#Mann= 6, -1 ,  0
       0     0.1       0  636.01   0.045       0  662.82     0.1       0
     780    0.05       0     800    0.06       0  999.64     0.1       0
Bank Sta=636.01,662.82
XS Rating Curve= 0 ,0
Exp/Cntr(USF)=0,0
Exp/Cntr=0.3,0.1

Type RM Length L Ch R = 1 ,91505   ,190.7,188.8,185.1
BEGIN DESCRIPTION:
Structure 20 XS 4
END DESCRIPTION:
XS GIS Cut Line= 6
1647167.95323542408881.6306975041647432.33853342409177.261667922
1647686.86459917409428.4061787581647731.44292209 409489.47692275
1647765.41431084409575.051226676  1647933.225655410114.312287256
#Sta/Elev= 30
       0 1259.21      39 1252.39   200.5 1140.21   257.2 1108.76   347.8 1048.94
   384.5 1034.04   402.1 1020.21   434.4 1011.51   465.7  992.72   501.2  981.02
   650.6  894.28   678.9  872.84   693.8  867.03   699.4  866.33  716.39 867.051
   863.3  870.38   889.1  885.21   923.5  885.37   956.7  908.77   980.8  916.62
  1006.4  934.17  1052.4  955.79    1086  985.05  1103.3  992.36    1128 1009.85
  1216.7 1050.19  1321.8 1107.86  1401.5 1157.22  1418.2 1180.08  1486.8 1215.41
#Mann= 6, -1 ,  0
       0     0.1       0   693.8   0.045       0  716.39     0.1       0
  804.28    0.05       0  909.89    0.06       0 1011.96     0.1       0
Bank Sta=693.8,716.39
XS Rating Curve= 0 ,0
Exp/Cntr(USF)=0,0
Exp/Cntr=0.3,0.1

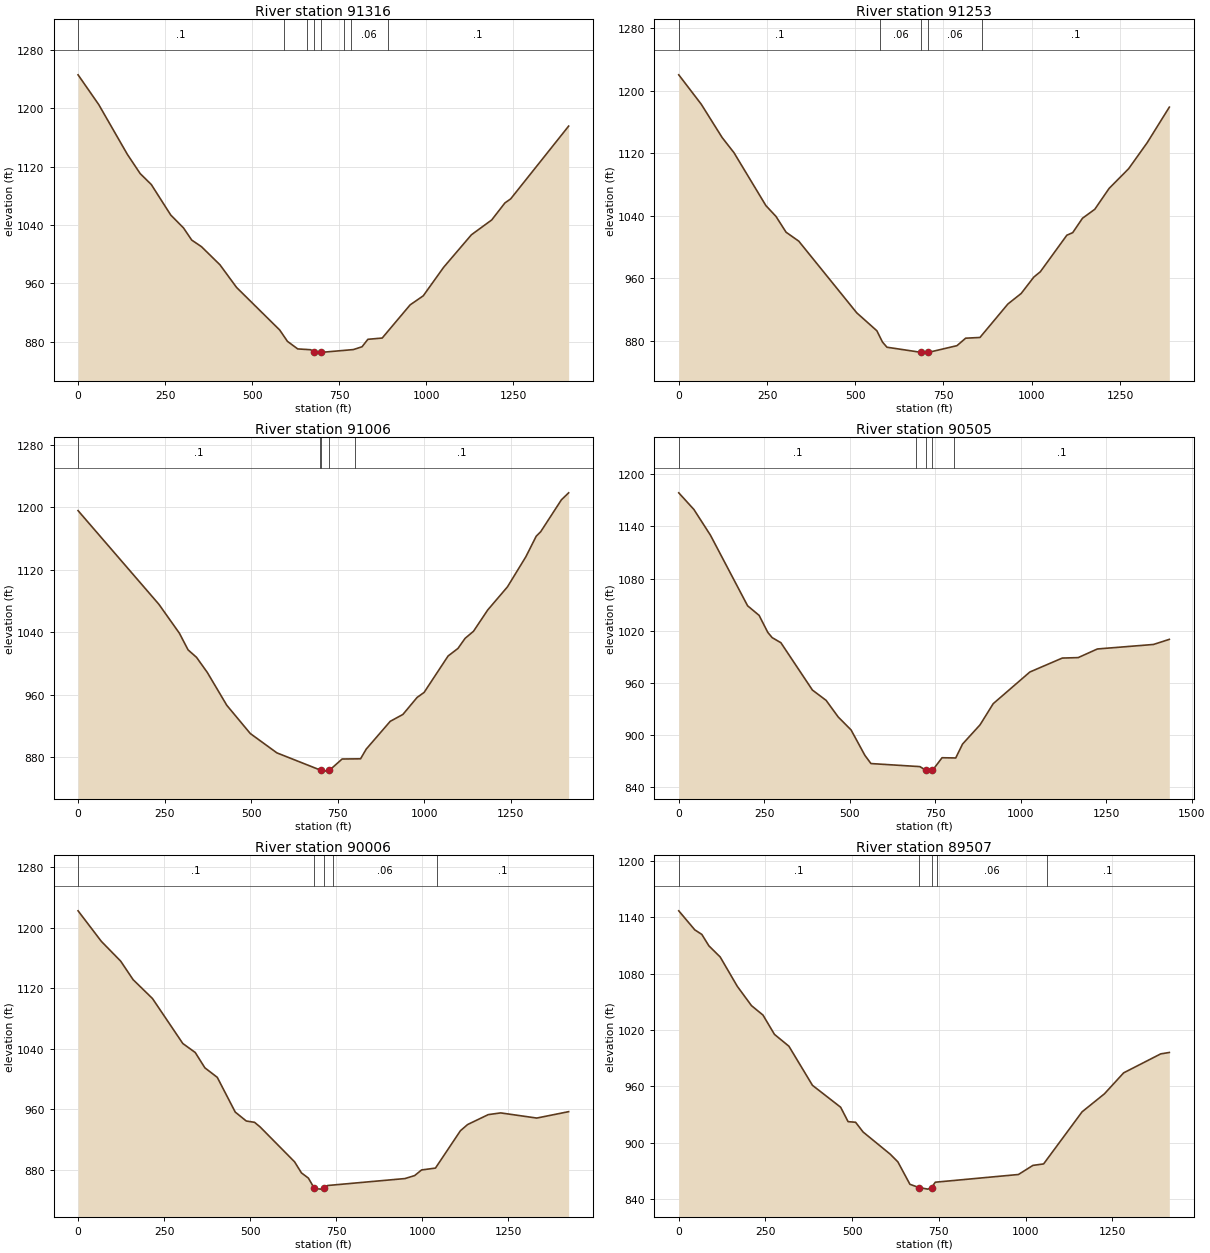
Type RM Length L Ch R = 1 ,91316   ,62.7,62.9,62.4
BEGIN DESCRIPTION:
Structure 20 XS 3
END DESCRIPTION:
XS GIS Cut Line= 5
1647099.15573272408970.8022296171647423.89112714409471.070269661
1647555.54061136409535.4322397251647592.10991253409563.224908616
1647773.49364635410155.647587616
#Sta/Elev= 30
       0 1245.82    59.3 1205.09   141.3 1137.02   178.3 1110.52   210.2 1095.53
   266.2 1053.63   302.7 1036.05   326.3 1019.39   354.4 1010.29   407.4  985.49
   455.1  954.46   579.1  896.05   601.1  880.62   630.6  870.24   667.9   869.1
   678.4  865.42   684.4  864.46  696.98865.4454   790.3  869.31   815.4  873.21
   832.1   883.4   873.2  885.13   953.4  930.57   991.1  943.01  1049.6  982.07
  1129.4 1026.66  1187.7 1046.99  1225.5 1070.26  1242.1 1075.85  1408.5 1175.56
#Mann= 8, -1 ,  0
       0     0.1       0     590    0.06       0  656.42     0.1       0
   678.4   0.045       0  696.98     0.1       0  762.96    0.05       0
  782.96    0.06       0   888.9     0.1       0
Bank Sta=678.4,696.98
XS Rating Curve= 0 ,0
Exp/Cntr(USF)=0,0
Exp/Cntr=0.3,0.1

Type RM Length L Ch R = 1 ,91253   ,240.4,247,259.5
BEGIN DESCRIPTION:
Structure 20 XS 2
END DESCRIPTION:
XS GIS Cut Line= 5
1647065.51197564409005.1773727191647404.87509053409530.312537561
1647536.52457475409594.6745076251647573.09387592409622.467176516
1647735.46157313410171.006694108
#Sta/Elev= 30
       0 1220.13    63.8 1182.51   122.9 1139.97   156.4 1120.62   246.9 1052.96
   275.5 1039.12     304 1018.97   339.9 1007.56   504.1  915.97   561.2     893
   577.1  878.58   589.8  871.95   686.7  865.37   698.1   864.4  707.23865.3603
   788.1  873.93   812.8   883.5   853.3  884.42   932.5  927.22   970.1  940.66
  1005.9  961.62  1024.3  968.39  1099.4 1015.09  1116.1 1018.42  1143.7 1036.78
  1178.6 1048.25  1219.2 1074.96  1274.6 1100.17  1327.2 1133.47  1389.8 1178.82
#Mann= 5, -1 ,  0
       0     0.1       0     570    0.06       0   686.7   0.045       0
  707.23    0.06       0  857.72     0.1       0
Bank Sta=686.7,707.23
XS Rating Curve= 0 ,0
Exp/Cntr(USF)=0,0
Exp/Cntr=0.3,0.1

Type RM Length L Ch R = 1 ,91006   ,500.6,501.1,495.8
BEGIN DESCRIPTION:
Structure 20 XS 1
END DESCRIPTION:
XS GIS Cut Line= 6
1646995.59531242409027.8220061661647105.29095918409200.044430763
1647156.25214334409287.2099388391647199.50271301409375.732071504
1647227.94589759409465.369359419 1647421.2998416410364.856077507
#Sta/Elev= 30
       0 1195.84   233.6    1076   292.8 1039.02     318 1017.63   342.3 1008.15
   373.4  988.88   429.7  946.85   497.7  910.65   574.7  885.86   701.8  863.59
     714  862.52  726.29863.5878   763.2  878.03   816.4  878.28   832.8   890.7
   902.1  926.21   938.8  935.06   979.7  956.76  1000.1  963.25  1069.4 1009.85
    1098 1019.55  1118.4 1032.36  1142.9 1041.53  1183.7  1068.6  1240.9 1098.27
    1294  1136.7  1324.1 1163.12  1336.9 1168.78  1396.9  1209.7  1417.8 1218.63
#Mann= 5, -1 ,  0
       0     0.1       0  700.23    0.06       0   701.8   0.045       0
  726.29    0.06       0  800.23     0.1       0
Bank Sta=701.8,726.29
XS Rating Curve= 0 ,0
Exp/Cntr(USF)=0,0
Exp/Cntr=0.3,0.1

Type RM Length L Ch R = 1 ,90505   ,493.4,498.9,499.2
XS GIS Cut Line= 6
1646572.15226167409215.3426285091646632.24236459409420.502651259
1646667.68192625409520.4351941791646711.76484334409612.050496504
1646797.50778209409778.6279192571647097.89235193410547.807155177
#Sta/Elev= 30
       0 1178.68    44.2 1159.55    92.7 1129.89   201.3 1048.67     235  1037.6
   260.5 1017.95   273.2 1011.97   298.7 1006.12     391   951.6     431  939.74
   466.3  920.64     504  905.68   544.4  876.42   562.1  867.01   705.4  863.48
   723.1859.1183   731.2   858.3     742  859.12     742  859.13     770  873.72
     810  873.46   829.9  889.43   881.2  911.63   919.6  935.94  1026.8  972.41
  1121.6  988.45  1168.2  988.99  1224.2  998.92  1388.2 1004.11  1434.7    1010
#Mann= 5, -1 ,  0
       0     0.1       0   694.3    0.06       0   723.1   0.045       0
     742    0.06       0  804.32     0.1       0
Bank Sta=723.1,742
XS Rating Curve= 0 ,0
Exp/Cntr(USF)=0,0
Exp/Cntr=0.3,0.1

Type RM Length L Ch R = 1 ,90006   ,489.3,499.2,505.6
XS GIS Cut Line= 6
1646340.22556017409217.0050267581646401.44820675410040.122146919
 1646400.1755715 410129.227611751646388.97841543410226.818623915
1646361.36528167410430.8415098341646336.34433433410636.493657589
#Sta/Elev= 30
       0 1222.54    67.7 1182.17   123.9 1156.02     160 1131.55   216.3 1106.61
   304.4  1047.2   340.5 1035.32   368.5 1015.06   404.6 1002.46   456.8  956.56
   488.9  944.75   512.9  943.01     529  936.96   629.3  890.79   649.3  876.13
   669.4  869.28   686.9855.6022   705.1  854.72   713.5  855.64   725.5  859.51
   950.1  868.69   978.2  872.62   998.4  880.07  1038.7  882.52  1111.4  931.98
  1132.2  940.09  1192.1  953.18  1228.4  955.46  1333.2  948.65  1425.8  957.11
#Mann= 5, -1 ,  0
       0     0.1       0   686.9   0.045       0   713.5     0.1       0
  740.39    0.06       0 1042.74     0.1       0
Bank Sta=686.9,713.5
XS Rating Curve= 0 ,0
Exp/Cntr(USF)=0,0
Exp/Cntr=0.3,0.1

Type RM Length L Ch R = 1 ,89507   ,496.9,500.8,503
XS GIS Cut Line= 6
1646118.08099134409251.1844203321646076.36257084409454.413344592
1646050.20645517409552.1562593431645983.21938442409732.592578262
1645881.74222517409975.3680113411645652.75121334410583.774930999
#Sta/Elev= 30
       0  1147.1    46.2 1126.83    66.5 1121.96    86.9 1109.79   119.5 1097.89
   168.7 1066.71   209.7 1046.05   242.8 1036.04   275.9 1015.46   317.6 1002.82
   385.5  961.16   466.8   937.8   488.2  922.45   509.8  921.81   531.6  911.38
   609.6  887.81   631.7  879.62   666.5   855.7   692.3  852.26   718.2  850.55
  728.77852.2626   739.7  857.93   979.3  866.13  1021.1  875.84  1051.9   877.4
    1163  932.98  1227.1  952.05  1282.7  974.46  1389.6  994.67  1414.4  996.17
#Mann= 5, -1 ,  0
       0     0.1       0   692.3   0.045       0  728.77     0.1       0
  744.21    0.06       0 1060.46     0.1       0
Bank Sta=692.3,728.77
XS Rating Curve= 0 ,0
Exp/Cntr(USF)=0,0
Exp/Cntr=0.3,0.1

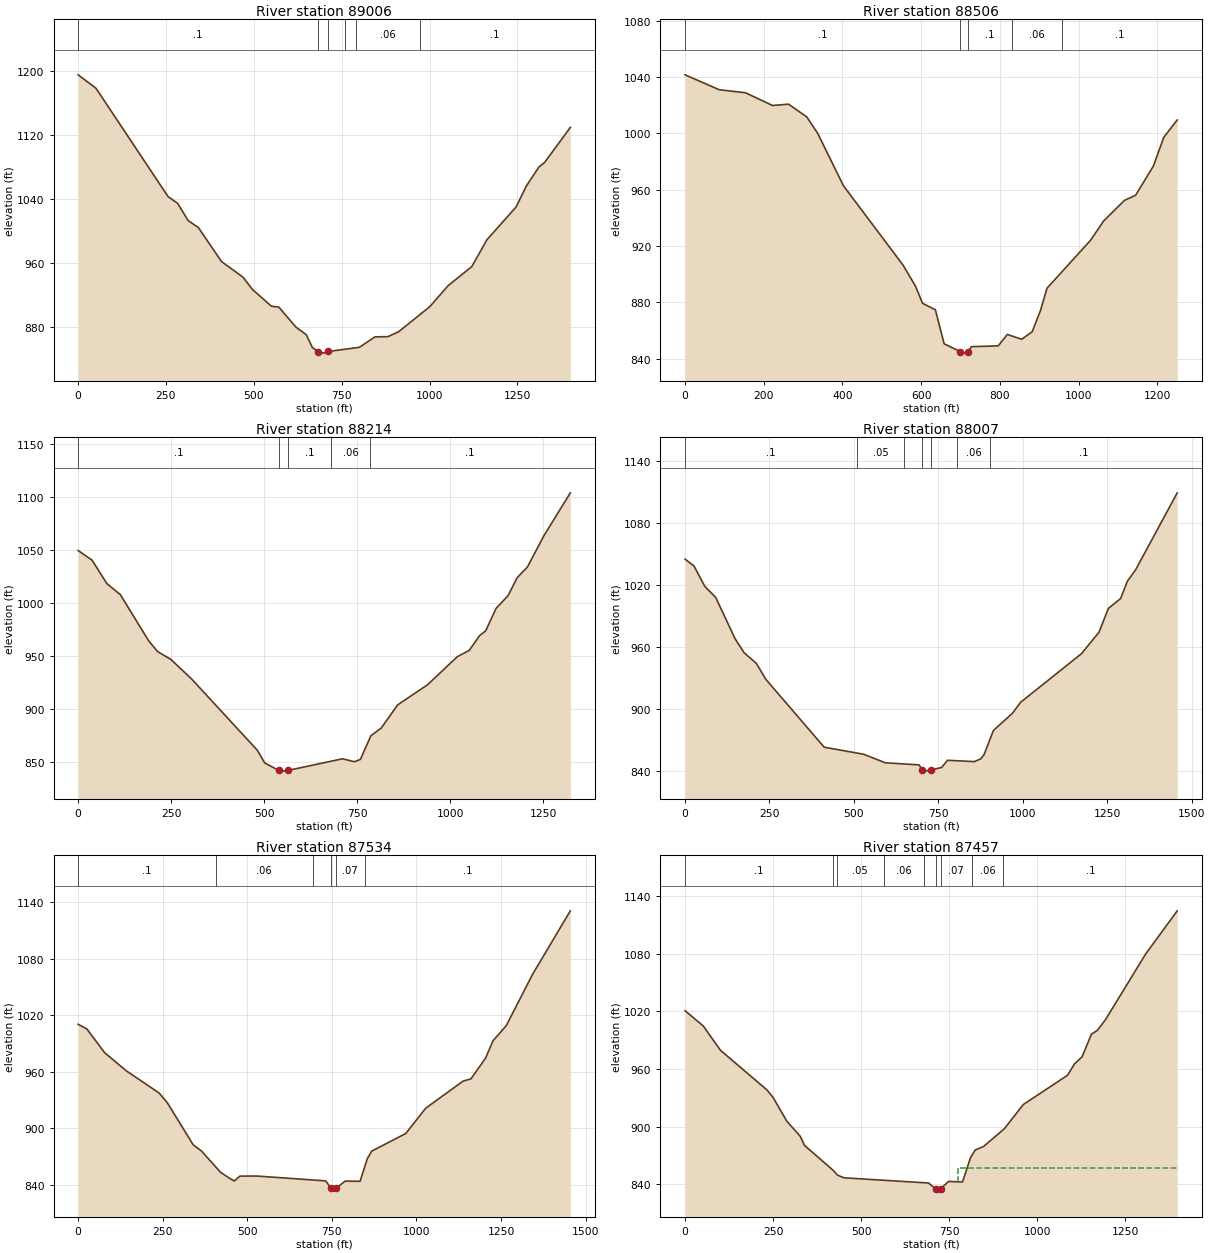
Type RM Length L Ch R = 1 ,89006   ,493.2,500,503.8
XS GIS Cut Line= 6
1645834.65668942409125.9645264151645780.39236225409209.514884248
1645726.19266751409292.6220014991645424.89143284409754.615828171
1645124.01736267410215.9564409261645069.77009584 410299.47989592
#Sta/Elev= 30
       0 1195.06    50.8 1178.25     256 1042.78   283.2 1034.46     313 1012.91
     342 1004.19   408.4   961.5   469.1   942.2   495.5  927.04     550  905.87
   571.2  904.72   619.4  879.89   649.3  870.19   666.7  854.18  683.01849.1732
   697.4   847.2   711.9  849.24   800.5  854.49   844.9  867.54   881.6  867.79
   911.3  873.67  1000.8  905.28    1053  931.56  1120.4  955.36  1163.4  988.91
  1246.6 1029.96  1275.5 1056.01  1311.4 1079.87  1327.6 1085.52  1400.8 1129.36
#Mann= 6, -1 ,  0
       0     0.1       0  683.01   0.045       0   711.9     0.1       0
  760.41    0.05       0  790.41    0.06       0  972.91     0.1       0
Bank Sta=683.01,711.9
XS Rating Curve= 0 ,0
Exp/Cntr(USF)=0,0
Exp/Cntr=0.3,0.1

Type RM Length L Ch R = 1 ,88506   ,300.5,292.2,282.4
XS GIS Cut Line= 6
1645614.81953068408958.3437986671645249.19690233 409297.11018151
1644955.81461509409464.0527610031644898.53449932409536.244159432
1644854.98668616 409626.812922521644810.53950339409843.796424091
#Sta/Elev= 30
       0 1041.65      87 1031.05   153.4 1028.92   222.3 1019.86   262.9 1020.81
   309.4 1011.73   337.3  999.93   402.4  962.85     554  906.42   585.4  891.53
   603.5  879.34     636  874.71   658.3  850.56   699.3  845.01   708.4  843.93
  719.31 844.884   727.4  848.53   795.6  849.08   818.8  857.18   855.2  853.78
     882  859.12   903.3  874.44   919.5  890.01  1030.7  924.24  1063.3  937.74
  1116.2   952.4  1144.7   956.1  1189.8  976.77  1216.3  997.27  1250.5 1009.58
#Mann= 5, -1 ,  0
       0     0.1       0   699.3   0.045       0  719.31     0.1       0
  831.33    0.06       0  958.49     0.1       0
Bank Sta=699.3,719.31
XS Rating Curve= 0 ,0
Exp/Cntr(USF)=0,0
Exp/Cntr=0.3,0.1

Type RM Length L Ch R = 1 ,88214   ,219.4,207.1,190.3
BEGIN DESCRIPTION:
Low water crossing
END DESCRIPTION:
XS GIS Cut Line= 6
1644861.31811743408691.4278203681644848.11431596409023.512995524
 1644851.6707192409216.0623598491644840.95994062 409241.05417655
1644813.87138418409389.6546709411644777.75355586410007.670844396
#Sta/Elev= 30
       0 1049.74    37.4 1040.59    77.2 1018.53   113.2 1008.17   189.3  964.65
   213.3  954.45   249.3  946.95   305.4  928.34   481.4  861.32   501.4  849.28
539.3927842.2065   555.8   841.6  563.18842.2338   710.3  853.24   742.3  850.43
   758.4  852.65   786.4  874.94   814.4  882.27   858.5  904.09   938.7  923.06
  1018.8  949.58  1050.8  955.52  1078.8  969.52  1094.9  973.93    1123  995.19
    1155 1007.11  1179.1 1023.89  1207.1 1034.15  1251.2 1063.57  1322.4 1104.14
#Mann= 5, -1 ,  0
       0     0.1       0539.3927   0.045       0  563.18     0.1       0
  680.62    0.06       0  783.38     0.1       0
Bank Sta=539.3927,563.18
XS Rating Curve= 0 ,0
Exp/Cntr(USF)=0,0
Exp/Cntr=0.3,0.1

Type RM Length L Ch R = 1 ,88007   ,468.1,472.7,477.6
BEGIN DESCRIPTION:
Structure 19 XS 4
END DESCRIPTION:
XS GIS Cut Line= 6
1644248.45776209408733.8754155931644505.98414992409161.667867094
 1644560.9295781409231.9357711671644700.37155643409338.366988748
1644731.60299745409377.6153948351644761.37534813410020.033555568
#Sta/Elev= 30
       0 1044.88    26.2 1038.44    58.5 1018.53    90.8 1007.83   148.1   967.9
   174.8  954.34   211.2  944.02   239.1   928.6     412  862.86   528.9  856.03
   592.7  847.78   693.1  845.72   702.5  840.67   709.3  839.69   728.2  840.79
   759.7  843.25   777.1  850.18   857.2  848.92   875.6  851.64   885.3  855.66
   913.2  879.12   969.3  895.64   993.6  906.31  1173.6  953.33  1225.6  974.08
  1253.6  997.22  1289.7 1006.77  1309.7 1023.48  1334.2  1034.6  1457.4  1109.1
#Mann= 7, -1 ,  0
       0     0.1       0  509.42    0.05       0  648.62     0.1       0
   702.5   0.045       0   728.2     0.1       0   804.1    0.06       0
  904.25     0.1       0
Bank Sta=702.5,728.2
XS Rating Curve= 0 ,0
Exp/Cntr(USF)=0,0
Exp/Cntr=0.3,0.1

Type RM Length L Ch R = 1 ,87534   ,77.2,77.1,77.4
BEGIN DESCRIPTION:
Structure 19 XS 3
END DESCRIPTION:
XS GIS Cut Line= 6
1643626.35919812409262.9750565691644030.87887529409311.734124799
1644148.26181732409335.2107132071644233.13871387 409494.12915781
1644332.46274175409611.5120998461644668.35854511410100.908673565
#Sta/Elev= 30
       0 1010.22    25.9 1005.22    78.1  980.14   142.2  960.83   239.5  937.21
   263.6  926.89   340.2  882.15   364.4   875.7   420.9     853   449.5  846.19
   461.7  843.78   478.1  848.94     528  849.02   731.7  843.89   748.3  835.83
   755.5  835.12   761.4835.8414   789.3  843.62   833.4  843.43   854.6   867.3
   867.4  875.41   968.3  894.15  1027.5  921.13    1138  949.88    1161  952.21
  1204.2  974.18  1226.4  992.79  1265.3 1008.67  1342.9 1063.04  1454.9 1130.75
#Mann= 6, -1 ,  0
       0     0.1       0  407.45    0.06       0   692.8    0.07       0
   748.3   0.045       0   761.4    0.07       0  847.57     0.1       0
Bank Sta=748.3,761.4
XS Rating Curve= 0 ,0
Exp/Cntr(USF)=0,0
Exp/Cntr=0.3,0.1

Type RM Length L Ch R = 1 ,87457   ,452.5,450.9,448.9
BEGIN DESCRIPTION:
Structure 19 XS 2
END DESCRIPTION:
XS GIS Cut Line= 6
1643620.94152387 409298.189939181644056.16135511 409365.00792157
1644076.02616068409383.0668357291644171.73840573  409538.3734975
1644271.06243361409655.7564395361644606.95823697410145.153013256
#Sta/Elev= 30
       0 1020.58    51.8 1004.68   100.3  979.48   232.9  937.98   250.1  930.15
     289  905.48     327  889.82   339.1   880.3     420  854.53   432.8  849.35
   451.3  846.58   691.1  841.17     711  835.16   718.3   834.8   725.2   835.1
   747.9   842.8   787.6  842.28   810.4  867.71   823.7  875.53   847.6   879.3
   906.2  897.64     960  922.87  1085.7   953.4  1105.1  965.11  1126.9  972.61
  1153.6  996.23  1170.1 1000.07  1193.1 1011.14  1307.1 1079.52    1397 1124.63
#Mann= 9, -1 ,  0
       0     0.1       0     420    0.06       0     430    0.05       0
  564.84    0.06       0  679.61    0.07       0     711   0.045       0
   725.2    0.07       0  813.38    0.06       0  903.38     0.1       0
#XS Ineff= 2 , 0
                          774.96          857.32
Permanent Ineff=
       F       F
Bank Sta=711,725.2
XS Rating Curve= 0 ,0
Exp/Cntr(USF)=0,0
Exp/Cntr=0.3,0.1

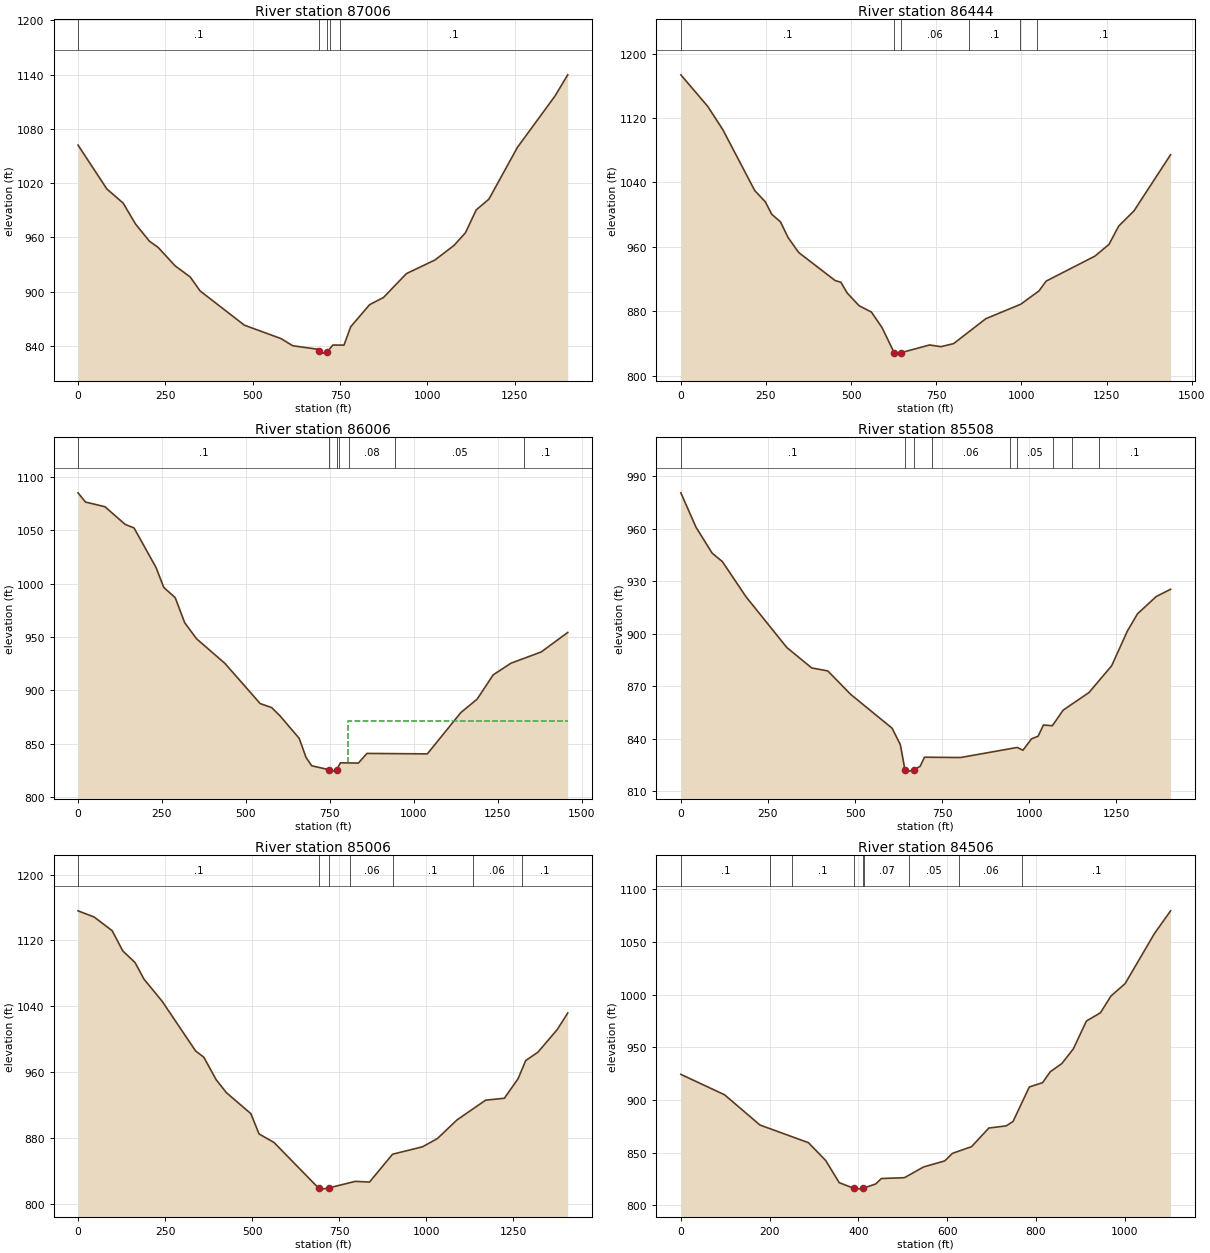
Type RM Length L Ch R = 1 ,87006   ,564.4,562,560.3
BEGIN DESCRIPTION:
Structure 19 XS 1
END DESCRIPTION:
XS GIS Cut Line= 6
1643390.66059317 409465.418243841643610.75857817409666.043170676
1643682.90607168409730.9193532621643753.44005135409792.813586429
1643820.74733143409848.7439207581644464.38613601410365.463031679
#Sta/Elev= 30
       0 1062.04    82.5 1013.48   129.2  997.83   164.6  974.71   204.3  955.74
   229.4  948.82     278  928.42   321.2  916.11   349.4   900.7   476.1  862.83
   581.3  847.95   614.2   840.1   683.7  836.31   689.4  833.74   703.6  831.91
   713.9  833.64   729.2  840.87   761.2  840.74   780.3  861.02   834.5  885.51
   874.4  893.49   939.8  919.83  1021.7  934.95  1076.4  951.14  1108.9  965.09
  1139.6  990.29    1176 1002.24  1257.6 1059.51  1365.3 1116.37  1401.6 1139.73
#Mann= 5, -1 ,  0
       0     0.1       0   689.4   0.045       0   713.9     0.1       0
  721.19    0.06       0  751.19     0.1       0
Bank Sta=689.4,713.9
XS Rating Curve= 0 ,0
Exp/Cntr(USF)=0,0
Exp/Cntr=0.3,0.1

Type RM Length L Ch R = 1 ,86444   ,434.4,438,440.8
XS GIS Cut Line= 4
1642973.19592182410058.805090638 1643652.2680172410390.608852207
1644141.76863136 410507.858026671644318.12433821410538.165696193
#Sta/Elev= 30
       0 1173.63    78.9 1134.49   123.5 1105.36   216.9 1029.99   248.1 1015.94
   266.7 1000.63   292.6  991.02   314.9  971.64     346  953.03   452.9  918.27
     470  916.05   488.5  902.72   523.3  886.98   559.7  879.03   590.9  859.72
   626.5  828.58   635.4  828.09   646.5  828.64   730.2  838.21   763.9  836.12
   800.9  839.88   895.5  870.82   998.3  888.84  1051.8  905.41  1072.5  917.45
  1216.3  948.62  1257.4  963.15  1285.7  985.82  1330.5 1004.61  1438.1 1074.44
#Mann= 6, -1 ,  0
       0     0.1       0   626.5   0.045       0   646.5    0.06       0
   845.8     0.1       0   995.8    0.12       0  1045.8     0.1       0
Bank Sta=626.5,646.5
XS Rating Curve= 0 ,0
Exp/Cntr(USF)=0,0
Exp/Cntr=0.3,0.1

Type RM Length L Ch R = 1 ,86006   ,497.4,498.6,494.5
XS GIS Cut Line= 6
1642858.26172359410212.5988360941643118.60864384410413.395678595
1643196.73611225410487.912589923 1643312.2844376410642.115037426
1643365.45296642410700.4259444181643931.75137451411192.809146002
#Sta/Elev= 30
       0 1085.07    22.3 1076.43    80.2 1072.06   140.3 1055.54   166.9 1052.18
   232.7 1014.95   255.4  996.47   289.5  986.91   317.9  963.37     353  948.44
   437.6  925.34   542.7   887.7   576.8  883.96   602.3  876.01     659  855.09
   679.3  837.24   696.2  829.45  747.89825.7493   758.6  824.44   770.3  825.72
   781.8  832.24   835.2  831.98   860.7  841.02  1040.6  840.59  1140.2   879.2
    1189  891.87  1236.7  914.57  1289.7  925.51  1379.8  936.02  1458.9  954.31
#Mann= 7, -1 ,  0
       0     0.1       0  747.89   0.045       0   770.3     0.1       0
  778.44    0.06       0  808.44    0.08       0  943.47    0.05       0
 1330.03     0.1       0
#XS Ineff= 2 , 0
                          805.18          871.38
Permanent Ineff=
       F       F
Bank Sta=747.89,770.3
XS Rating Curve= 0 ,0
Exp/Cntr(USF)=0,0
Exp/Cntr=0.3,0.1

Type RM Length L Ch R = 1 ,85508   ,500.7,501.4,499.7
XS GIS Cut Line= 6
1642763.97736202410379.0667520731642947.96069117410951.111466676
1643027.78205384411011.4131833311643270.85505851411142.368302003
1643433.54469375411279.3211120961643579.79735401411435.996979833
#Sta/Elev= 30
       0  980.48    43.6  960.79    89.8  946.03   119.2  941.21   186.4  921.28
   304.1  892.14   375.5  880.49   421.7  878.78   487.7  865.34   606.1  846.08
   629.8  836.71643.1111822.2679   656.2  821.56667.7111822.3411   686.3  824.24
   699.1  829.51   802.8  829.33   965.1  835.08   981.7   833.5  1006.2  839.99
  1025.3  841.53  1040.4  847.88  1066.1   847.5    1097  856.39    1171  866.41
  1236.1  881.69  1281.3  901.53  1310.4  911.41    1364  921.25  1405.3   925.4
#Mann= 9, -1 ,  0
       0     0.1       0643.1111   0.045       0667.7111     0.1       0
  720.94    0.06       0  944.68    0.07       0  964.68    0.05       0
 1068.12    0.06       0 1123.79    0.05       0 1200.95     0.1       0
Bank Sta=643.1111,667.7111
XS Rating Curve= 0 ,0
Exp/Cntr(USF)=0,0
Exp/Cntr=0.3,0.1

Type RM Length L Ch R = 1 ,85006   ,502.8,500,496.2
XS GIS Cut Line= 6
 1642138.5958401410920.145977423  1642790.672948411426.175149083
1642859.12851976411480.6842264241642931.54110458411540.290078342
1643001.59017709411608.7194034161643211.64257851411826.532944173
#Sta/Elev= 30
       0 1155.95    46.3 1148.44    98.1 1131.83   128.5 1107.34   163.9 1093.12
   189.2 1073.19   242.1 1045.91   337.8  985.84   361.4  978.22   396.8  950.97
   426.1   935.2   496.6  909.67   520.2  884.99     563  874.69   691.3  819.22
   700.6  817.97   719.8  819.34   796.7  827.41   837.5  826.56   903.9  860.37
   990.2  869.42  1032.7   879.4  1089.3  902.13  1171.3  926.03  1225.1  928.33
  1264.7  952.21  1286.4  974.13  1321.4  984.23  1376.8 1011.64  1407.2 1031.87
#Mann= 7, -1 ,  0
       0     0.1       0   691.3   0.045       0   719.8     0.1       0
  780.39    0.06       0  905.39     0.1       0 1134.61    0.06       0
 1274.75     0.1       0
Bank Sta=691.3,719.8
XS Rating Curve= 0 ,0
Exp/Cntr(USF)=0,0
Exp/Cntr=0.3,0.1

Type RM Length L Ch R = 1 ,84506   ,273.9,275.2,275.8
BEGIN DESCRIPTION:
Structure 18 XS 4
END DESCRIPTION:
XS GIS Cut Line= 6
1642078.07135484411629.9670643361642335.34019725411735.666328013
1642566.66716242411830.471256509 1642647.5967906411863.720533833
1642823.91566367411936.1623180961643098.87771218412049.130268008
#Sta/Elev= 30
       0  924.22    98.6  904.81   178.2  876.11   287.6  859.31   326.5  842.34
   356.8  821.36  389.99 815.959   395.7  815.22   409.8  815.99   438.9  820.08
   451.9   825.3   503.8  826.08     547  836.29   594.6  842.04   611.9  849.17
   655.1  855.58     694  873.25   733.1  875.29   748.5  879.48   785.2  912.25
   815.1  916.34   832.4  926.72   858.4  934.44   884.3  948.39     914  974.97
   945.4  982.68   969.1  998.61  1001.1 1010.46  1067.2 1058.02  1103.5 1079.55
#Mann= 9, -1 ,  0
       0     0.1       0  200.63    0.05       0  250.63     0.1       0
  389.99   0.045       0   409.8     0.1       0  413.14    0.07       0
  513.14    0.05       0  625.63    0.06       0  769.38     0.1       0
Bank Sta=389.99,409.8
XS Rating Curve= 0 ,0
Exp/Cntr(USF)=0,0
Exp/Cntr=0.3,0.1

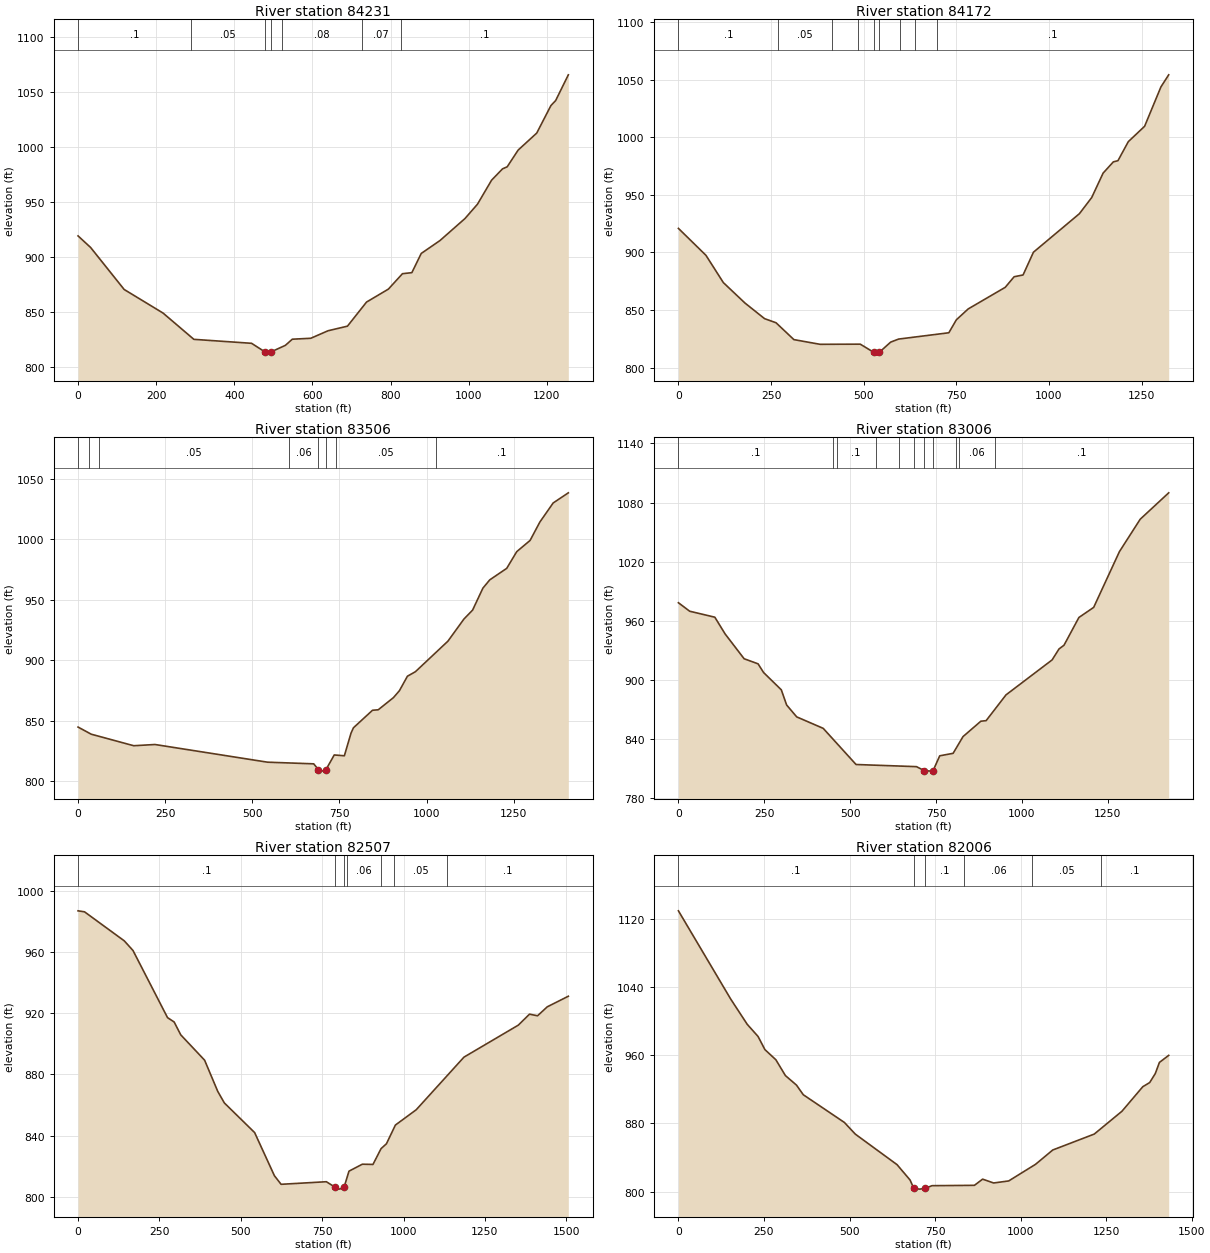
Type RM Length L Ch R = 1 ,84231   ,59.5,59.2,59
BEGIN DESCRIPTION:
Structure 19 XS 3
END DESCRIPTION:
XS GIS Cut Line= 5
 1642022.5585997 411672.712034411642184.88241375411951.150693539
1642380.38189782412056.6019304011642521.37849542412111.104816869
1643080.62550439412107.550280795
#Sta/Elev= 30
       0  919.17    32.2  908.64     118  870.51   217.5  849.09   296.4  825.21
   444.1  821.61  477.92813.9103     485  812.69     494  813.83   530.5  819.73
   548.4  825.34   595.6  826.18     640  833.03   689.5  837.18   738.3  859.06
   794.3  870.85   830.3  884.84   854.3  885.78   878.3  903.22   926.3  914.95
   990.3  934.95  1022.3  947.98  1058.3  969.75  1086.3  980.05  1098.3  981.93
  1126.3   997.1  1173.9 1012.56  1210.3 1037.61  1222.3 1042.07  1254.8 1065.48
#Mann= 7, -1 ,  0
       0     0.1       0     290    0.05       0  477.92   0.045       0
     494    0.05       0   522.3    0.08       0  725.59    0.07       0
  825.59     0.1       0
Bank Sta=477.92,494
XS Rating Curve= 0 ,0
Exp/Cntr(USF)=0,0
Exp/Cntr=0.3,0.1

Type RM Length L Ch R = 1 ,84172   ,661.9,665.5,665.4
BEGIN DESCRIPTION:
Structure 19 XS 2
END DESCRIPTION:
XS GIS Cut Line= 6
1641966.87086787411688.1150240641642143.41282622411994.989971785
1642266.63674345412063.7110025491642340.09715564412100.441208647
1642488.20282539412152.5744043991643077.07096832412135.986569387
#Sta/Elev= 30
       0  920.86    74.3   897.5   121.3  873.81   179.9  856.01   232.6  842.53
   263.5  838.98   311.7  824.35   382.3  820.28   490.9   820.4   526.7  813.44
     537  812.63  542.48813.4041   572.8  822.17   594.2  824.82   729.9  830.29
   750.2  841.54   782.2  850.98   882.1  869.71   906.2   878.9   930.3  880.44
   958.3  900.19  1082.3  933.59  1115.6  947.63  1146.3   968.8    1174  978.58
  1186.4  979.59  1214.4  996.12  1258.4 1009.45  1302.4 1043.61  1323.4 1054.09
#Mann= 9, -1 ,  0
       0     0.1       0     270    0.05       0  414.03    0.07       0
  484.03    0.05       0   526.7   0.045       0  542.48    0.05       0
  597.26    0.08       0  637.26    0.05       0  697.26     0.1       0
Bank Sta=526.7,542.48
XS Rating Curve= 0 ,0
Exp/Cntr(USF)=0,0
Exp/Cntr=0.3,0.1

Type RM Length L Ch R = 1 ,83506   ,501.6,500,497.6
BEGIN DESCRIPTION:
Structure 19 XS 1
END DESCRIPTION:
XS GIS Cut Line= 6
1641328.94490033412004.5191367571641679.73619351412344.423968762
1642057.50151409 412699.949504421642120.27632293412774.509722754
1642178.63972326412855.2618578371642288.08996367413025.346819505
#Sta/Elev= 30
       0  844.69    37.7  838.81   159.7  829.27   220.8  830.27   543.7  815.66
   676.1   814.3   689.7  809.48   701.1  808.27   711.3  809.54     735  821.64
     764  820.95   783.1  839.65   790.1  844.11   844.8  858.58   861.2  858.98
   904.8  869.02     922  874.76     945  886.73   967.9  890.46    1061  915.65
  1107.2  934.03  1131.9  941.35  1161.5  959.52  1181.2  966.38  1229.8  975.87
  1258.6   989.7  1296.9  998.97  1324.8 1014.11  1363.1 1029.93  1406.6 1038.31
#Mann= 8, -1 ,  0
       0    0.05       0      30     0.1       0      60    0.05       0
  605.96    0.06       0   689.7   0.045       0   711.3    0.06       0
  740.96    0.05       0 1027.23     0.1       0
Bank Sta=689.7,711.3
XS Rating Curve= 0 ,0
Exp/Cntr(USF)=0,0
Exp/Cntr=0.3,0.1

Type RM Length L Ch R = 1 ,83006   ,487.9,499.6,508.6
XS GIS Cut Line= 6
1640974.91640893412383.5236280861641027.92384884412484.732743248
1641089.51526108412575.6088738441641166.67291518412638.304614589
1641462.57357009412831.5411047491642084.84627567413250.901158422
#Sta/Elev= 30
       0  978.17    32.8  969.55     106  963.49     136  946.44   191.3  921.26
   231.8  916.11     248  907.24   299.5   889.7     315  874.28   344.4  862.18
   421.5  850.55   517.1  813.81     693  811.63  715.87807.5896   735.9  807.08
   741.4  807.55   760.7  822.64   799.7  825.17   828.5  842.16   880.4  857.79
   895.8  858.38   953.7  884.57  1087.9   920.1    1108  931.24  1122.5  935.01
  1165.9   963.2  1208.9  973.47  1283.8 1030.08  1344.3 1063.02  1427.3 1089.86
#Mann= 11, -1 ,  0
       0     0.1       0  450.48    0.05       0  460.48     0.1       0
  574.33    0.05       0  641.86     0.1       0  686.87    0.06       0
  715.87   0.045       0   741.4    0.06       0  806.87    0.08       0
  816.87    0.06       0  921.87     0.1       0
Bank Sta=715.87,741.4
XS Rating Curve= 0 ,0
Exp/Cntr(USF)=0,0
Exp/Cntr=0.3,0.1

Type RM Length L Ch R = 1 ,82507   ,494.9,500.4,498.4
XS GIS Cut Line= 6
1640961.63986067412397.8903972511641036.40939617412633.076606676
1641060.46118534412753.240080252 1641093.6707646412974.537537917
1641126.82981901413134.0441086741641297.82783659413864.692253679
#Sta/Elev= 30
       0  986.92    19.9  986.27   142.1  967.29   168.8     961   274.9  917.14
   295.3  914.27   315.6  905.87   388.9  889.31   429.3  868.91   449.5  861.39
   542.6  842.01   603.4  813.81   623.9  808.21     763   809.9   789.5  806.33
   803.8  805.06  817.65806.4446   832.5   816.8   873.5  821.34   906.2   821.2
   931.1  831.53   947.5  834.68   975.1  846.92  1039.2  856.95  1185.8  891.31
  1352.8  912.22  1387.2   919.4  1411.9  918.33  1441.7  924.18  1506.5  931.11
#Mann= 7, -1 ,  0
       0     0.1       0   789.5   0.045       0  817.65     0.1       0
  826.11    0.06       0  931.11     0.1       0  971.11    0.05       0
 1132.36     0.1       0
Bank Sta=789.5,817.65
XS Rating Curve= 0 ,0
Exp/Cntr(USF)=0,0
Exp/Cntr=0.3,0.1

Type RM Length L Ch R = 1 ,82006   ,497,500,502.3
XS GIS Cut Line= 6
1640654.68542209412367.8074521721640680.07185426413192.807770669
1640680.60138075413281.487383336 1640671.6027111413381.694860086
1640659.04105642413485.3390097621640609.57166718413795.242589429
#Sta/Elev= 30
       0 1129.56   152.8 1025.99   201.1  996.34   232.8  982.06   252.8  966.64
   284.9   954.7   312.6  936.19   344.9  925.04   364.9  913.69     485  881.16
     517  867.43     639   831.6     677  813.59  687.99803.7629   705.1  802.88
   721.1  803.71   741.1  806.93   865.1  807.34   889.1   814.6   921.2  810.09
   965.3   812.5  1043.7     832  1094.1  848.83  1215.3   867.5  1296.3  894.31
  1357.1  923.07  1377.4     928  1393.7  938.55  1405.8  951.64  1432.9  959.88
#Mann= 6, -1 ,  0
       0     0.1       0  687.99   0.045       0   721.1     0.1       0
  835.39    0.06       0 1034.68    0.05       0 1234.22     0.1       0
Bank Sta=687.99,721.1
XS Rating Curve= 0 ,0
Exp/Cntr(USF)=0,0
Exp/Cntr=0.3,0.1