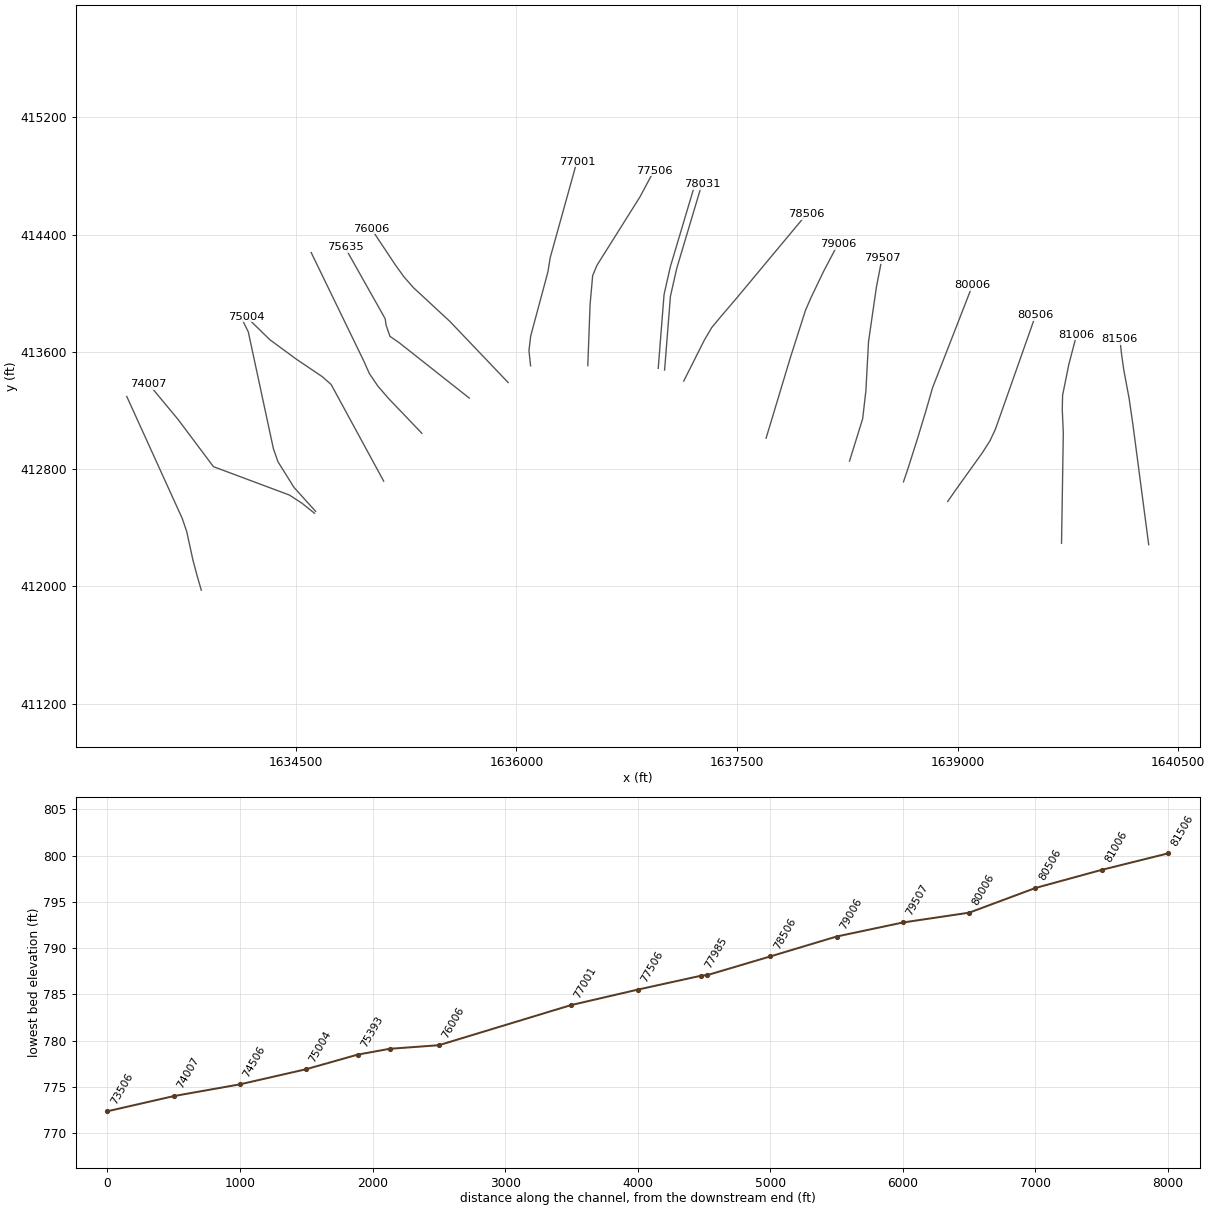
HEC-RAS study LTLFSHNGCK.prj: LTLFSHNGCK

--- LTLFSHNGCK.g01 (geometry) --- (continued)

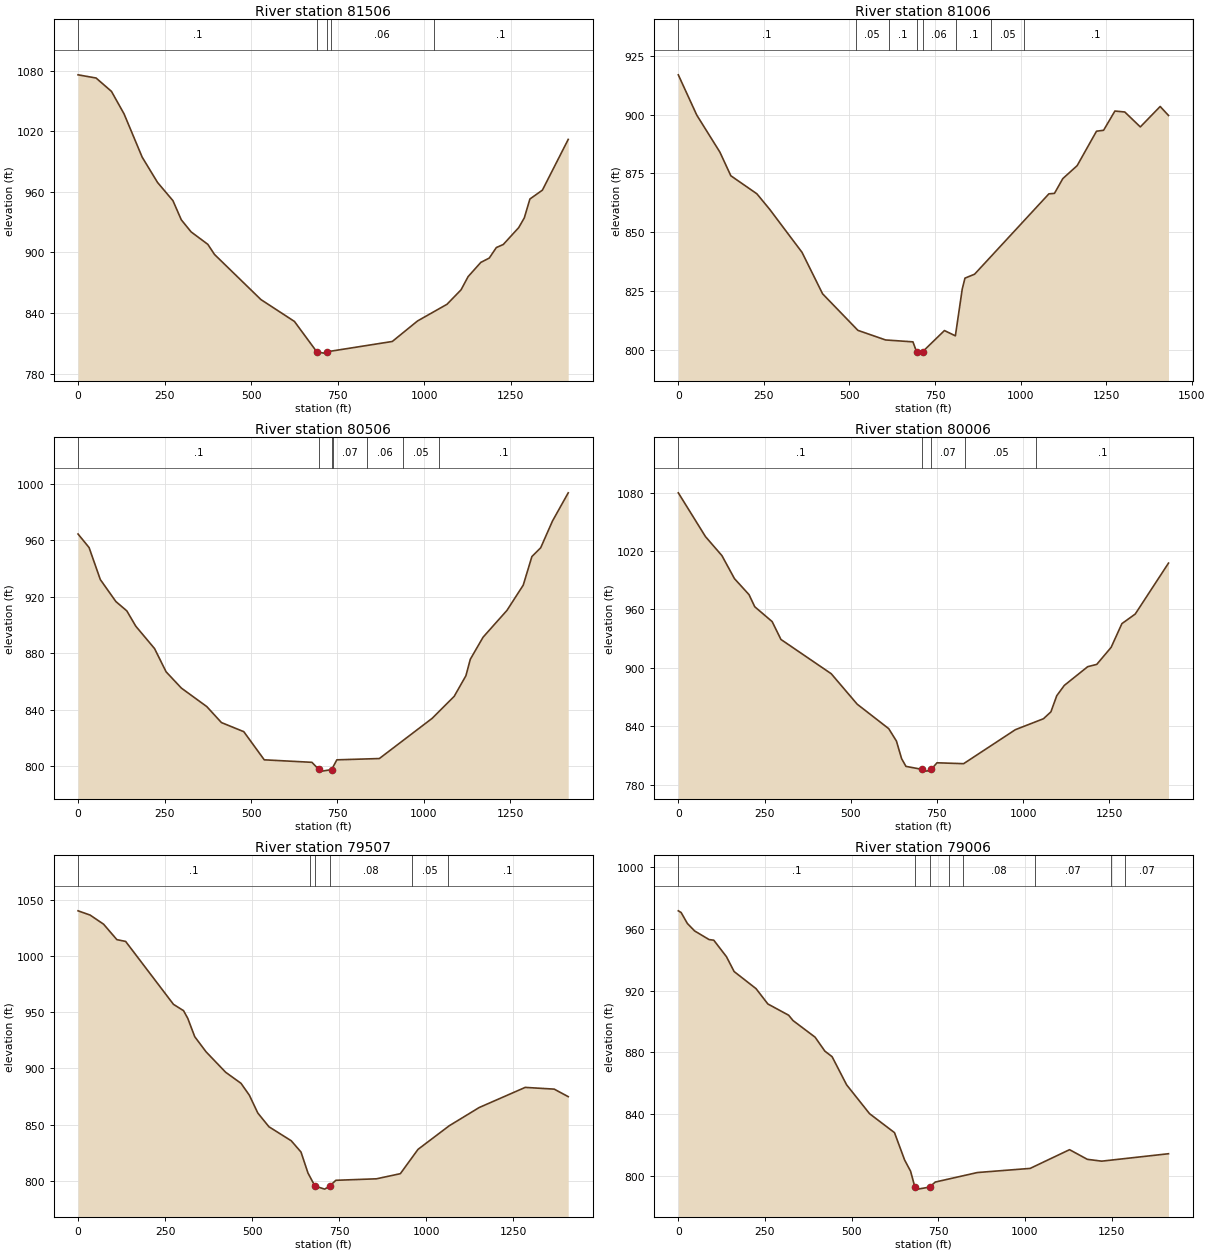
Type RM Length L Ch R = 1 ,81506   ,502,500,496.5
XS GIS Cut Line= 6
1640299.70975409412284.8627361661640192.41698967413103.250207007
1640166.53974484413282.660281256 1640130.1014975413477.968617678
1640115.45749792413581.762045249 1640103.6487945413686.489526093
#Sta/Elev= 30
       0 1075.84    52.1 1072.68    96.5 1059.44   132.8 1037.23   185.2   994.3
   229.6  969.25     274  951.25   298.2  932.25   326.4  920.34   374.8  907.97
   394.1  897.95   528.1  853.29   624.9  831.62   689.5  801.54   709.5  800.25
  718.34801.5492   907.5  811.79   980.3  832.08  1065.5  848.63  1106.1  862.95
  1126.5  876.03  1163.1  890.08  1187.6   894.4  1207.9  904.77  1228.1  907.86
  1272.6  924.56  1288.7  934.14  1304.9  952.86    1341  961.66  1415.6  1011.9
#Mann= 5, -1 ,  0
       0     0.1       0   689.5   0.045       0  718.34     0.1       0
  730.39    0.06       0 1026.66     0.1       0
Bank Sta=689.5,718.34
XS Rating Curve= 0 ,0
Exp/Cntr(USF)=0,0
Exp/Cntr=0.3,0.1

Type RM Length L Ch R = 1 ,81006   ,497.2,500,494.5
XS GIS Cut Line= 6
1639706.89696334412295.0352880061639718.99700476413045.328406841
1639711.86414501413208.2509812561639714.13349742413304.213059679
1639755.47855909413510.4045764211639809.01322892413715.996356845
#Sta/Elev= 30
       0     917    53.9  899.86   121.5  884.08   153.5  874.01   229.5  866.34
   266.5  859.81   361.5  841.39   421.6  823.73   524.8  808.17   605.6  804.08
   685.6  803.27  696.19799.0483   701.6  798.47   713.6  799.04   777.6  808.08
   809.6  805.84   829.6  825.73   837.6  830.41   865.7  832.08  1082.8  866.31
  1099.1  866.51  1123.5   872.8  1165.4  878.32  1221.9  892.98  1242.7  893.39
  1275.7  901.58  1304.6  901.17    1350  894.81    1408  903.52  1432.3  899.69
#Mann= 8, -1 ,  0
       0     0.1       0  517.89    0.05       0  615.39     0.1       0
  696.19   0.045       0   713.6    0.06       0  810.39     0.1       0
  913.49    0.05       0 1009.47     0.1       0
Bank Sta=696.19,713.6
XS Rating Curve= 0 ,0
Exp/Cntr(USF)=0,0
Exp/Cntr=0.3,0.1

Type RM Length L Ch R = 1 ,80506   ,501,500,498.9
XS GIS Cut Line= 6
1638932.76235676412579.5665430871638991.12444475412663.843277425
1639168.24023226412911.9051172581639220.04721525412993.189403504
  1639257.262692413072.8575512621639531.12369284413851.517083168
#Sta/Elev= 30
       0  964.52    31.9  954.93    64.4  932.24   109.4  916.67     141  910.06
   166.8  899.25   221.2  883.33   254.6  866.88   298.6  855.37   372.2  842.24
   414.5  830.92   479.2  824.46   538.3  804.52   676.1  802.75  696.17 797.675
   705.8  796.51     733   797.6   748.2  804.51   871.1  805.43  1023.8  833.93
  1087.4  849.49  1121.3  864.11    1134  875.76  1170.9  891.41    1240  910.42
    1287   928.3  1312.1  948.58  1337.5  954.79  1371.6  973.76  1417.1  993.71
#Mann= 7, -1 ,  0
       0     0.1       0  696.17   0.045       0     733     0.1       0
  736.64    0.07       0  836.64    0.06       0  939.14    0.05       0
 1042.89     0.1       0
Bank Sta=696.17,733
XS Rating Curve= 0 ,0
Exp/Cntr(USF)=0,0
Exp/Cntr=0.3,0.1

Type RM Length L Ch R = 1 ,80006   ,490,499.1,503.8
XS GIS Cut Line= 6
1638632.09202634412713.8267732561638664.57457292412810.261619762
1638726.03540801413004.4390529251638783.75674926413194.865181252
 1638829.6556076413355.1929445861639101.29121917414054.531769007
#Sta/Elev= 30
       0 1079.72    78.8 1034.74   126.5 1015.19   162.9  991.55     205  975.16
   221.7  962.68   272.1  947.45   297.6   929.1   443.5  893.87   518.6  862.64
   610.1  837.48   632.5  824.72   647.5  806.66   660.1  798.72     708  795.57
   720.4  793.84  733.67795.6534   750.1  802.41   827.3  801.49   977.5  836.44
    1059  847.68  1080.4  854.74  1097.4  871.32  1119.2  881.86  1187.1  901.12
  1213.4   903.5  1255.1  921.01  1286.3  945.36  1324.9  955.19  1421.4 1007.52
#Mann= 5, -1 ,  0
       0     0.1       0     708   0.045       0  733.67    0.07       0
  831.21    0.05       0  1037.4     0.1       0
Bank Sta=708,733.67
XS Rating Curve= 0 ,0
Exp/Cntr(USF)=0,0
Exp/Cntr=0.3,0.1

Type RM Length L Ch R = 1 ,79507   ,507.6,501.3,496.5
XS GIS Cut Line= 6
 1638265.0382985412855.3602828381638354.43050817413143.674994916
 1638376.3395851413333.4328175041638394.45798717413670.495135501
1638448.31056976414044.0409763461638486.16449668414240.012369171
#Sta/Elev= 30
       0 1039.99    34.7 1036.22    73.4 1028.11   111.5  1014.4   136.7  1012.8
   274.1   956.9   302.9  951.32   315.1  944.53   335.2  928.17   367.5  914.82
   423.9   896.6   468.1  886.76   492.1  876.17   516.3   860.4   548.3  848.17
   612.3  835.75   640.3  825.75   660.3  807.16   680.3  795.55   708.3  792.78
  722.37795.3903   740.4  800.62   857.1  801.95   925.7   806.5   976.4  828.09
  1065.9  849.02  1152.1  865.26  1284.3  883.15  1367.6  881.61  1407.9  874.92
#Mann= 6, -1 ,  0
       0     0.1       0  665.64    0.08       0   680.3   0.045       0
  722.37    0.08       0  958.56    0.05       0 1062.53     0.1       0
Bank Sta=680.3,722.37
XS Rating Curve= 0 ,0
Exp/Cntr(USF)=0,0
Exp/Cntr=0.3,0.1

Type RM Length L Ch R = 1 ,79006   ,505.7,499.5,489.4
XS GIS Cut Line= 6
1637697.77106035413011.4957973361637863.22939084413562.388068259
1637965.80562925413884.1682645831638003.71533035413971.472551927
1638090.25879243414152.359001175 1638185.9518425414334.505946592
#Sta/Elev= 30
       0  971.87     8.1  970.78    26.1  963.68      47  958.83    88.8  953.21
   102.3  952.81   138.9  942.12   161.1  932.46   224.3  921.37   258.4  911.43
   318.5   904.1     331  900.65   394.6  889.89   422.9  880.82   443.8   877.2
   485.6  858.96   551.9  840.21   623.8  827.92     653  810.17   670.2   802.9
   682.8  792.44   691.2  791.26   724.8  792.57   741.6  795.86   862.9  802.03
  1015.2  804.71  1128.9  816.86  1180.2   810.6  1221.7  809.41  1414.4  814.23
#Mann= 8, -1 ,  0
       0     0.1       0   682.8   0.045       0   724.8    0.06       0
  780.21    0.07       0  820.21    0.08       0 1028.14    0.07       0
 1248.67    0.05       0 1288.67    0.07       0
Bank Sta=682.8,724.8
XS Rating Curve= 0 ,0
Exp/Cntr(USF)=0,0
Exp/Cntr=0.3,0.1

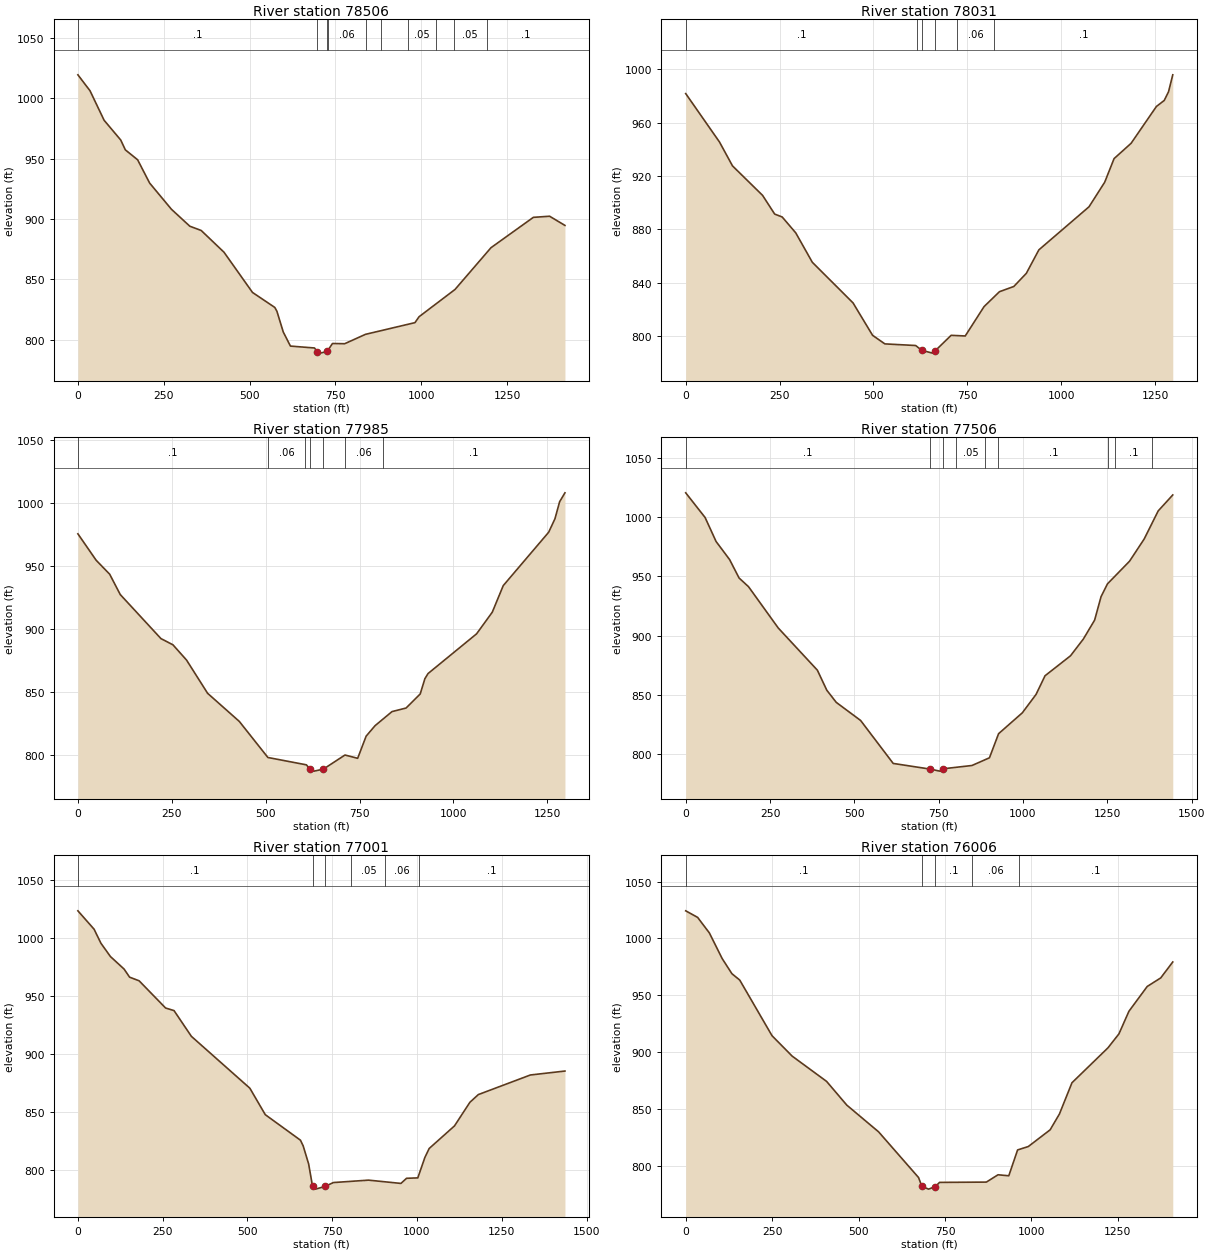
Type RM Length L Ch R = 1 ,78506   ,464.6,474.9,478
BEGIN DESCRIPTION:
Structure 18 XS 4
END DESCRIPTION:
XS GIS Cut Line= 6
1637137.68031701413401.0685090121637277.93364543413680.679826424
1637328.10578917413765.9601676761637387.86223134413838.323211923
1637493.23373976413962.0454054181637972.65961817414539.311967418
#Sta/Elev= 30
       0 1019.18    35.3 1006.01    76.4   981.6   124.8  965.27   138.2  957.15
     174  948.94     209  929.68   272.4  908.05     326  894.02   359.1  890.51
   425.5  872.54   508.5  839.28   573.5  826.88   579.7  823.66   598.1  806.61
     619  794.93     689  793.37   697.7  790.37     706  789.11   725.9  790.49
   741.5  797.08     777  796.89   837.7  804.65   981.6   814.3   993.7  819.21
  1098.4  841.75  1203.1  876.26  1326.5  901.36  1373.8  902.28  1418.5  894.69
#Mann= 10, -1 ,  0
       0     0.1       0   697.7   0.045       0   725.9     0.1       0
  728.12    0.06       0  838.12    0.07       0  883.12     0.1       0
  960.62    0.05       0 1044.37    0.06       0 1094.37    0.05       0
 1191.25     0.1       0
Bank Sta=697.7,725.9
XS Rating Curve= 0 ,0
Exp/Cntr(USF)=0,0
Exp/Cntr=0.3,0.1

Type RM Length L Ch R = 1 ,78031   ,45.7,46,45.8
BEGIN DESCRIPTION:
Structure 18 XS 3
END DESCRIPTION:
XS GIS Cut Line= 4
1637007.55630456413476.3349448661637047.28591571413980.178649913
1637090.62730969414171.6031400021637260.38110279414742.264827439
#Sta/Elev= 30
       0  981.86      90  945.51   124.6  927.61   204.8  905.45   236.9  891.45
     257  889.24   293.1  877.32   337.2  855.26   445.6  824.78   497.7  800.45
   530.4  794.02   612.4   792.8   628.8  789.17   657.5  787.09     665788.9911
   706.8  800.44   744.4  799.97   794.5  821.98   835.5  833.18   873.8  837.11
   907.1  846.96   940.5  864.58  1074.1  896.92  1115.8  915.33  1140.8  933.06
  1186.1  944.54  1253.5  972.18  1274.4  976.73  1285.8  983.21  1297.1  995.94
#Mann= 6, -1 ,  0
       0     0.1       0  615.41    0.05       0   628.8   0.045       0
     665    0.05       0  721.68    0.06       0  821.68     0.1       0
Bank Sta=628.8,665
XS Rating Curve= 0 ,0
Exp/Cntr(USF)=0,0
Exp/Cntr=0.3,0.1

Type RM Length L Ch R = 1 ,77985   ,484.3,479.1,472.1
BEGIN DESCRIPTION:
Structure 18 XS 2
END DESCRIPTION:
XS GIS Cut Line= 4
1636964.21491058413488.0732390691637003.94452173413991.916944116
1637047.28591571414183.3414342061637217.03970881414754.003121643
#Sta/Elev= 30
       0  975.22    48.6  954.28    84.7  943.18   112.8  927.08   221.1  892.16
   253.2  887.19   289.4  875.09   345.5  848.73   429.8  826.48     506  797.85
   608.6  792.01  618.38  788.43   629.1  787.03   653.7   788.6   711.3  799.81
   745.1  797.19   767.6  814.74   791.3  823.04   836.5  834.23     874  837.07
   911.6  848.21   924.1  860.32   932.5  864.41  1061.8  895.92  1103.6  913.08
  1132.8  934.16  1253.8   976.5  1270.5  987.18    1283 1000.72  1297.1 1007.74
#Mann= 7, -1 ,  0
       0     0.1       0  505.41    0.06       0  605.41    0.05       0
  618.38   0.045       0   653.7    0.05       0  711.68    0.06       0
  811.68     0.1       0
Bank Sta=618.38,653.7
XS Rating Curve= 0 ,0
Exp/Cntr(USF)=0,0
Exp/Cntr=0.3,0.1

Type RM Length L Ch R = 1 ,77506   ,491.4,505,501.3
BEGIN DESCRIPTION:
Structure 18 XS 1
END DESCRIPTION:
XS GIS Cut Line= 6
1636485.32663484413506.475122333 1636500.9161706413924.497252166
1636518.43122743414121.0267147571636547.78090626414191.072834507
1636840.62087175414658.503330082 1636934.8129406414835.700482249
#Sta/Elev= 30
       0 1020.67    57.5  999.81    90.1  979.52   130.2  964.24   158.2   948.7
   186.2  941.37   274.3  906.47   390.3  870.83   418.3  853.88   446.4   843.6
   518.5  828.34   615.2  792.01   724.9  787.23     753  785.52   762.7  787.48
   848.7  790.28   900.5  796.77   927.6  817.15     998  834.79  1038.7  850.35
  1065.3  866.09  1140.8  882.96  1178.9  897.13  1212.3  913.09  1231.4  932.93
  1250.4  943.75  1315.9   962.9  1359.2  981.63  1400.9 1005.42    1444 1018.87
#Mann= 9, -1 ,  0
       0     0.1       0   724.9   0.045       0   762.7     0.1       0
  801.68    0.05       0  886.68    0.06       0  926.68     0.1       0
 1253.29    0.05       0 1273.29     0.1       0 1383.23    0.05       0
Bank Sta=724.9,762.7
XS Rating Curve= 0 ,0
Exp/Cntr(USF)=0,0
Exp/Cntr=0.3,0.1

Type RM Length L Ch R = 1 ,77001   ,977.7,995,1014.7
XS GIS Cut Line= 6
1636096.20044459413505.0187604281636085.21523035413609.009694174
  1636096.875312   413708.2175011636213.70972401  414144.4036365
1636229.85437676414243.659343511 1636411.3446224414898.660169857
#Sta/Elev= 30
       0  1023.2    47.8 1007.37    67.9  995.33      96  983.87   136.3  973.09
   152.4  966.15   180.6  963.01   258.6  939.62   283.5  937.39   334.7  915.24
   507.1  870.65   552.6  847.88   656.2  825.96   664.3  821.08   680.5  805.46
     692   786.2   700.7  783.84   729.1  786.19   753.4  789.49   857.1  791.57
   952.6  788.75   969.2  793.16  1002.4  793.51  1023.1  810.97  1035.9  818.78
  1110.6  838.23    1156  858.52  1180.9  865.16  1334.4  882.01  1436.3   885.4
#Mann= 6, -1 ,  0
       0     0.1       0     692   0.045       0   729.1     0.1       0
  806.58    0.05       0  906.58    0.06       0 1006.58     0.1       0
Bank Sta=692,729.1
XS Rating Curve= 0 ,0
Exp/Cntr(USF)=0,0
Exp/Cntr=0.3,0.1

Type RM Length L Ch R = 1 ,76006   ,379.7,371.4,360.5
XS GIS Cut Line= 6
1635943.62266576413391.1922164261635546.21204326413809.255684748
1635299.01175025414039.0531254261635236.92558834414109.843994334
 1635179.5329866414189.1584682611635012.51691642414441.085129753
#Sta/Elev= 30
       0 1024.22    34.5 1018.44    68.5 1004.76   105.3  982.32   133.6  968.95
   156.3  963.33   249.7  914.39   307.9  896.47   407.5  874.24   465.9  853.39
     558  829.86   673.5  789.69  683.04781.9885   702.3  779.51   722.2  781.68
   734.1  785.43   869.6  785.69   903.4  792.13   934.5  791.24     960  813.98
   990.9  816.96  1054.1  831.66    1081  845.58  1117.2  873.03  1221.2   903.7
  1253.1  916.02    1282   935.9  1334.9  957.71    1374  965.24  1408.8  979.24
#Mann= 5, -1 ,  0
       0     0.1       0  683.04   0.045       0   722.2     0.1       0
  826.91    0.06       0  964.41     0.1       0
Bank Sta=683.04,722.2
XS Rating Curve= 0 ,0
Exp/Cntr(USF)=0,0
Exp/Cntr=0.3,0.1

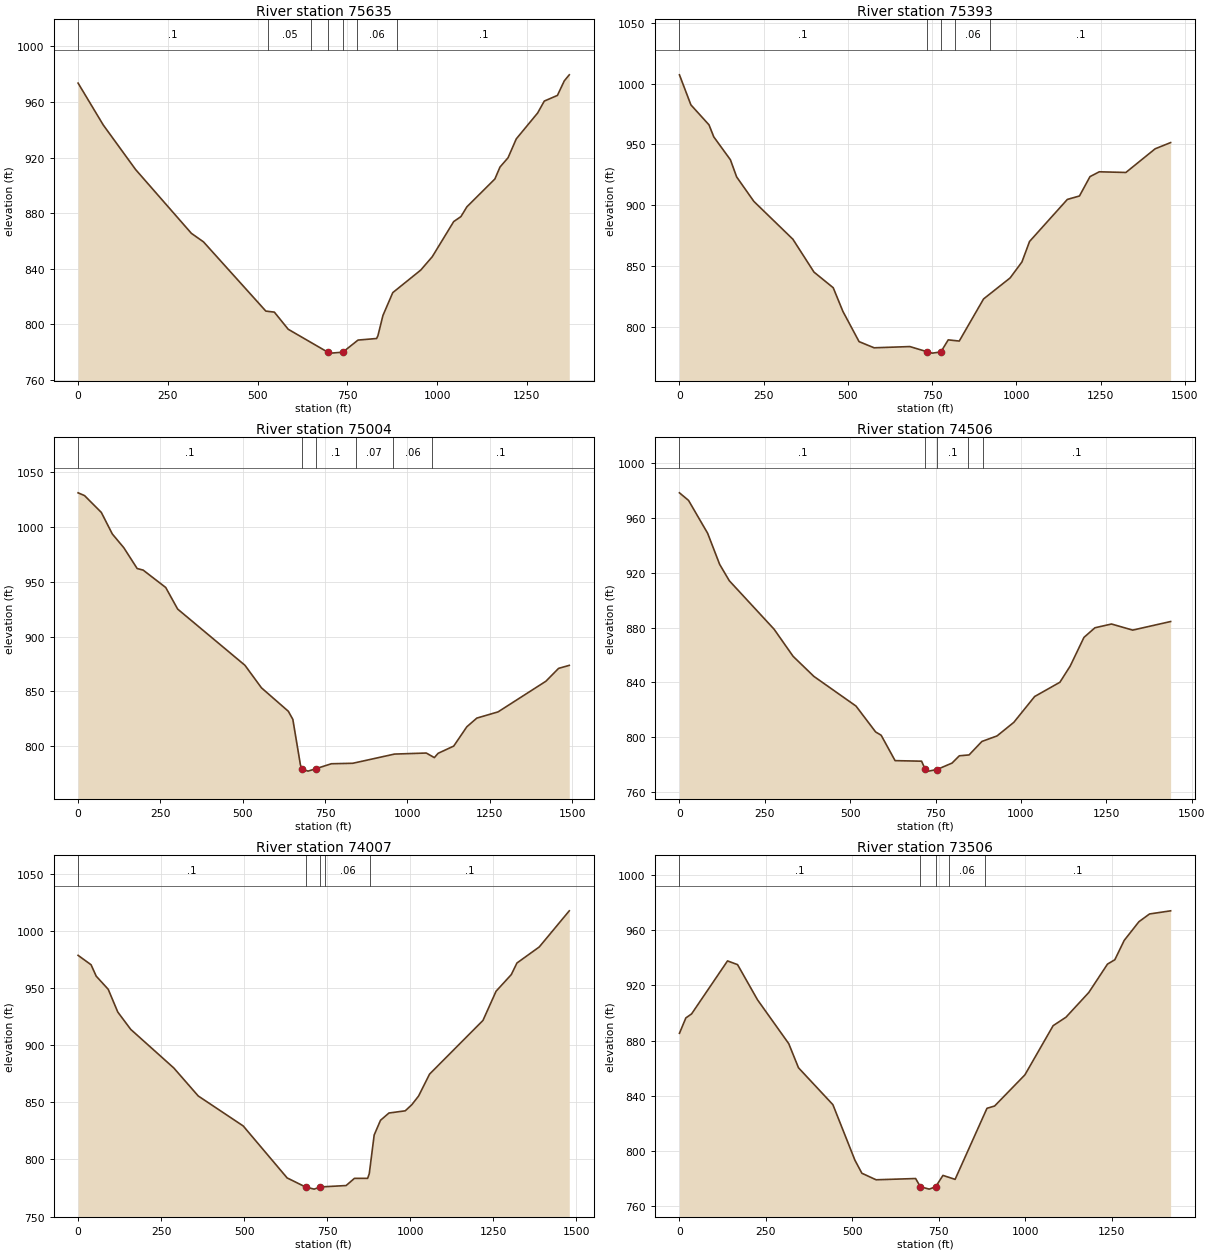
Type RM Length L Ch R = 1 ,75635   ,239.4,241.5,243.9
BEGIN DESCRIPTION:
Low water crossing
END DESCRIPTION:
XS GIS Cut Line= 6
1635679.48455978413285.0415451491635201.15810044413663.899505299
1635139.72167447 413706.319894661635113.39177763413783.846813146
1635107.54068944413826.2672025061634834.00231667414313.370294127
#Sta/Elev= 30
       0  973.58    70.1  943.43   160.2  911.35   315.6   865.4   349.4  859.24
   523.1  809.39   546.8  808.65   585.4  796.31   695.4  779.84   705.1  779.12
  737.53779.8098   779.9  788.52   831.7  789.65   835.4  791.67   849.3  806.21
   876.7  822.68   954.7  838.94   986.8  848.56  1046.5  873.87  1066.7  877.46
  1083.2  884.48  1161.2  904.53  1175.4  913.11  1197.9  919.82  1220.8  933.41
  1280.4  952.08  1298.8  960.63  1335.5  964.73  1354.6   975.2  1368.5  979.55
#Mann= 7, -1 ,  0
       0     0.1       0     530    0.05       0  650.19     0.1       0
   695.4   0.045       0  737.53     0.1       0  777.07    0.06       0
  889.89     0.1       0
Bank Sta=695.4,737.53
XS Rating Curve= 0 ,0
Exp/Cntr(USF)=0,0
Exp/Cntr=0.3,0.1

Type RM Length L Ch R = 1 ,75393   ,381.3,389.7,384.7
XS GIS Cut Line= 6
1635356.73852475413045.0544116581635128.15892943413284.845926815
1635057.06163067  413367.73191591635000.02335893413452.171707654
1634963.72061001413534.1439846541634604.25282501414277.873140239
#Sta/Elev= 30
       0 1007.23      34  982.53    87.8   966.1   101.9  956.24   151.3  937.39
   169.8  923.31   220.9   903.2   336.8  872.09   399.4  845.09   456.5  832.23
   485.1  812.88   533.2  787.95   577.8  782.87   683.9  783.88     735  779.64
   750.7  778.49     776779.4633   797.9  789.39   830.6  788.41   902.8  823.03
   981.6  840.29  1016.7  853.42  1039.3  870.26  1151.5  904.82  1187.5  907.65
  1218.7  923.56  1246.3  927.53  1325.3  926.98  1412.3  946.46  1458.1  951.54
#Mann= 5, -1 ,  0
       0     0.1       0     735   0.045       0     776     0.1       0
   817.7    0.06       0   922.7     0.1       0
Bank Sta=735,776
XS Rating Curve= 0 ,0
Exp/Cntr(USF)=0,0
Exp/Cntr=0.3,0.1

Type RM Length L Ch R = 1 ,75004   ,502.8,497.6,491.5
XS GIS Cut Line= 6
1635097.34876776412718.3202025891634739.88097876413377.959631339
1634678.10288709413432.1927905831634501.48513009413551.797210172
1634322.71481834413683.5856605021634163.19479617413839.997421175
#Sta/Elev= 30
       0 1031.37    19.5 1028.85    70.5 1013.46   103.9  993.75   138.8  981.18
   179.4  962.14   197.5  960.73     266  944.85   302.3  925.08   506.7  873.68
   556.7  853.09   638.4  831.64   652.1  824.22   675.1  782.67   679.7     779
   698.1  776.91   721.1  779.02     769  783.65   834.2  784.09   960.9   792.5
  1057.3  793.45  1081.8  789.28  1093.2  793.19  1140.6  799.81  1180.4  817.44
  1210.7  825.38  1275.3  831.08  1420.5   859.1  1459.1  870.87  1491.5  873.62
#Mann= 6, -1 ,  0
       0     0.1       0   679.7   0.045       0   721.1     0.1       0
   842.5    0.07       0   955.4    0.06       0  1075.8     0.1       0
Bank Sta=679.7,721.1
XS Rating Curve= 0 ,0
Exp/Cntr(USF)=0,0
Exp/Cntr=0.3,0.1

Type RM Length L Ch R = 1 ,74506   ,479.3,499,516.4
XS GIS Cut Line= 6
1634634.34247592412512.4593938441634487.39165434412675.640497923
1634377.72159809  412851.85110351634346.87487501412941.630123422
 1634176.4519875413736.8624568431634131.33921684413828.958729342
#Sta/Elev= 30
       0  978.22    26.6   972.7    82.6  948.71   117.7  926.07     146  914.12
   277.2  878.76   332.8  859.01   393.8  844.34   517.1  822.72   574.4  803.88
   590.7  801.45   631.5  782.93   709.1  782.53  719.92776.4706   729.5  775.28
   754.1  776.45   798.3  781.15   819.6  786.46   848.2   787.1   885.6   796.9
   930.1  800.96   979.2  810.85  1040.2  829.69  1114.1  840.08  1144.3   851.9
  1184.6   872.8  1216.7  879.81  1265.3  882.56  1327.3  878.11  1438.4  884.37
#Mann= 5, -1 ,  0
       0     0.1       0  719.92   0.045       0   754.1     0.1       0
  845.03    0.06       0  890.02     0.1       0
Bank Sta=719.92,754.1
XS Rating Curve= 0 ,0
Exp/Cntr(USF)=0,0
Exp/Cntr=0.3,0.1

Type RM Length L Ch R = 1 ,74007   ,510.4,500.8,482
XS GIS Cut Line= 6
1634626.56460434412499.4367820921634543.34987576412566.415650755
1634456.28016801412623.5507070871633939.46099168412817.313771009
1633699.39487076 413138.716999591633498.85721409413381.299191594
#Sta/Elev= 30
       0  978.81    39.1  970.56    54.5  960.59    90.7  949.07   119.4  929.18
   158.5  913.95   288.1  880.16   361.8   855.6   497.2  829.34   629.4  783.82
     685  775.85   710.7  774.01  729.37775.9146     807  777.15     832  783.43
   871.8  783.45   876.7  787.54   891.5  821.45   910.6  834.34     936  840.69
     985  842.61  1004.4  847.84  1025.1  855.54  1058.2  874.74    1219   921.8
  1258.5  947.38  1304.3  961.95  1321.3  972.09  1388.5  986.16  1478.9 1017.82
#Mann= 5, -1 ,  0
       0     0.1       0     685   0.045       0  729.37     0.1       0
  742.91    0.06       0  880.37     0.1       0
Bank Sta=685,729.37
XS Rating Curve= 0 ,0
Exp/Cntr(USF)=0,0
Exp/Cntr=0.3,0.1

Type RM Length L Ch R = 1 ,73506   ,537.9,535.2,527.2
BEGIN DESCRIPTION:
Structure 17 XS 4
END DESCRIPTION:
XS GIS Cut Line= 6
1633856.90374209411974.7796949151633827.66364309412076.233560249
1633800.53574459412178.1149181721633757.53025317   412375.594182
1633727.03293884412464.7019434271633350.11144859413296.146474749
#Sta/Elev= 30
       0  885.27    18.5  896.39    35.1  899.32     139   937.7     168  935.01
   225.8  909.49     316  877.77   344.2  860.29   443.7  833.54   507.3  793.38
   527.5  783.87   568.6  779.14   682.8  780.05   696.7  774.07   722.3  772.37
  740.91774.1144   761.9  782.32     797  779.44   889.2  830.92   911.2  832.57
   998.8  855.13  1080.5  890.79  1117.6  896.91  1183.5  914.79  1237.7   935.4
  1258.8  938.53    1286  952.55  1328.4  966.06  1359.1   971.7  1420.2  973.98
#Mann= 5, -1 ,  0
       0     0.1       0   696.7   0.045       0  740.91     0.1       0
  779.81    0.06       0  884.81     0.1       0
Bank Sta=696.7,740.91
XS Rating Curve= 0 ,0
Exp/Cntr(USF)=0,0
Exp/Cntr=0.3,0.1