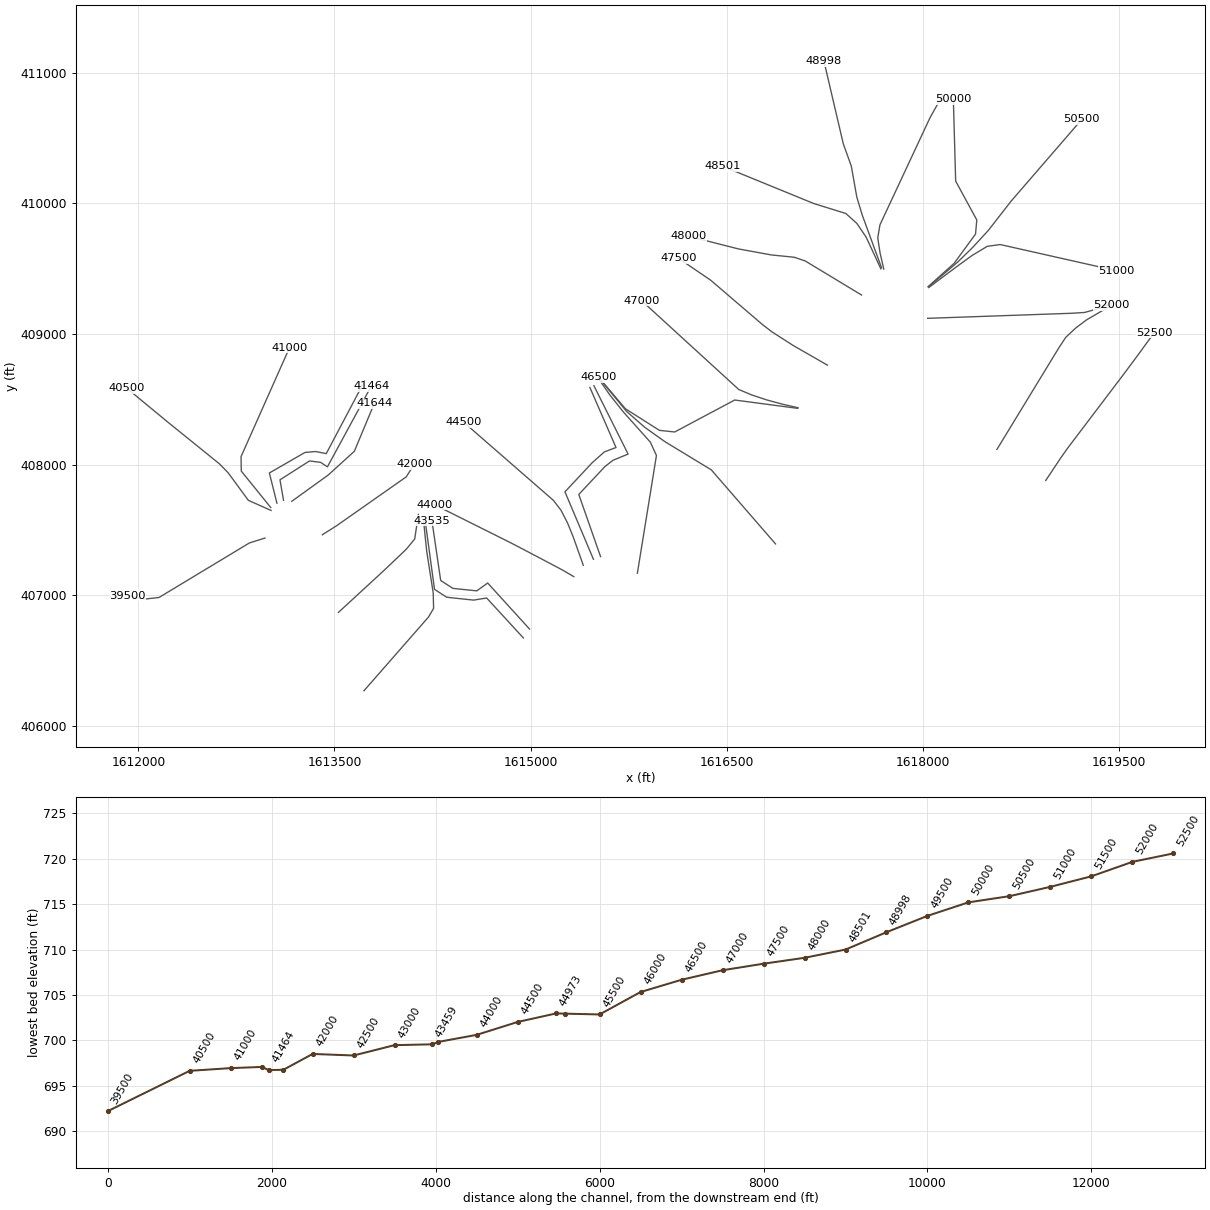
HEC-RAS study LTLFSHNGCK.prj: LTLFSHNGCK

--- LTLFSHNGCK.g01 (geometry) --- (continued)

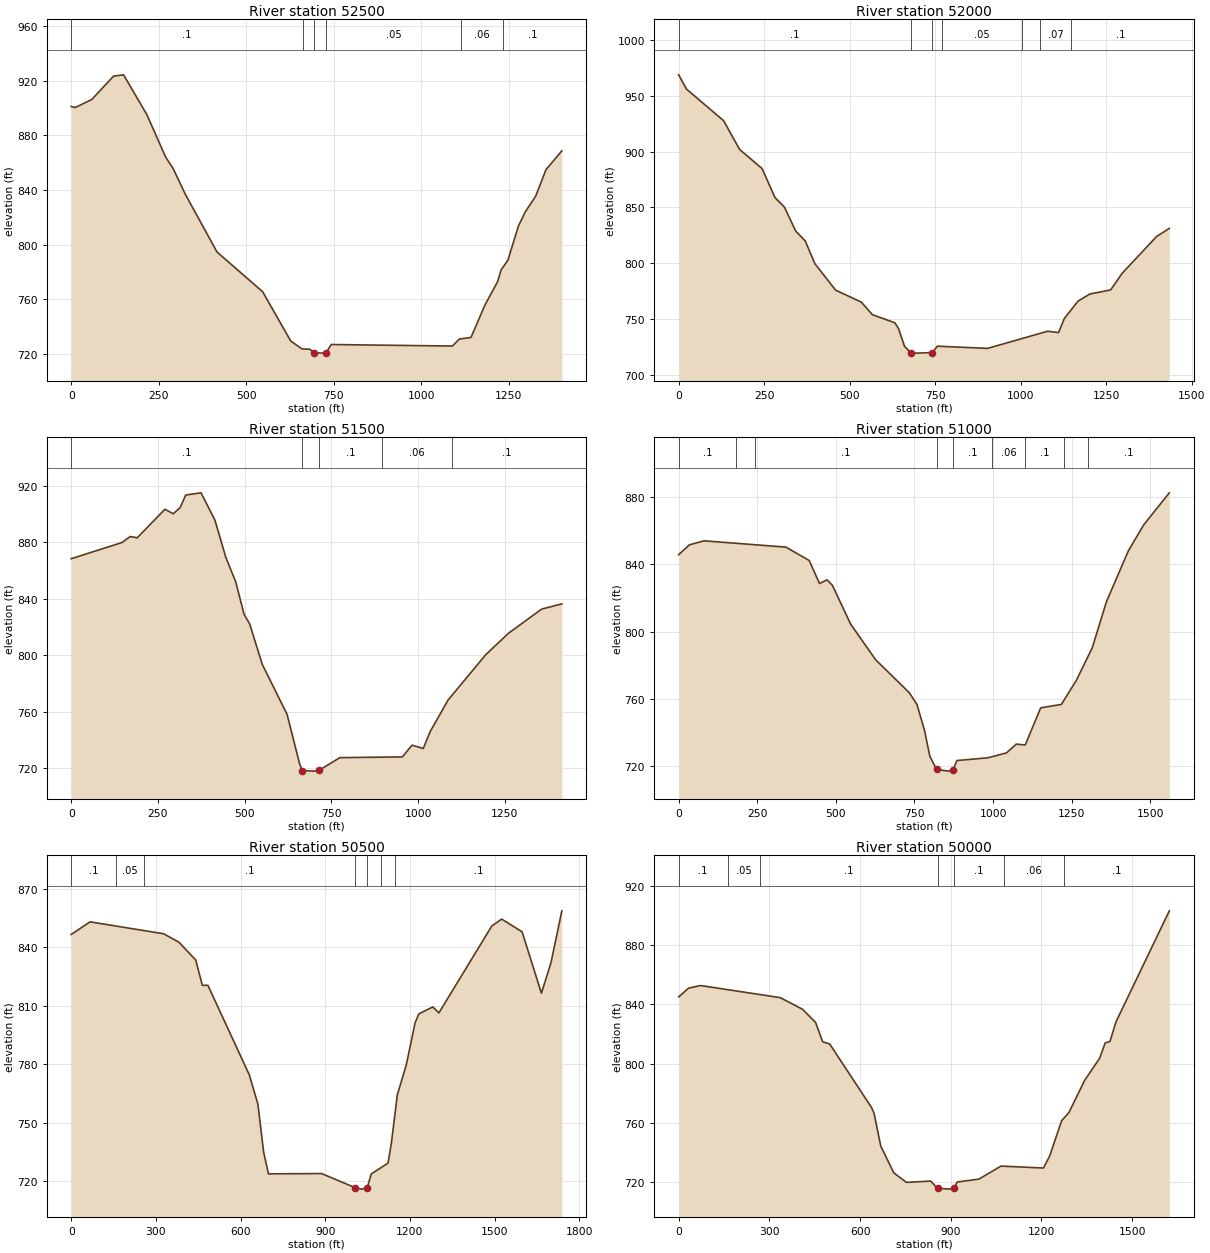
Type RM Length L Ch R = 1 ,52500   ,498.7,500,502.1
XS GIS Cut Line= 6
1618941.51067267407879.4781742541619051.67383817408045.370559007
1619108.28264885408125.9806340041619536.64465301408691.417495251
1619653.03582442408848.2738088371619770.00048551409009.105836257
#Sta/Elev= 30
       0  901.11      12  900.45    58.8   906.3   121.1  923.41   149.6  924.34
   216.1  895.19   269.5  864.22     291  855.77   325.9  836.91   416.4  794.63
   546.7  765.53     627  729.46   659.1  723.68   681.6  723.45   693.4  720.88
   719.1  720.59  728.45720.9791   742.5  726.89  1088.4  725.78  1108.3  730.85
  1141.8   732.1  1181.8  755.92  1217.5   772.8  1227.6  781.41  1247.2  788.67
  1276.9  813.44  1296.3  823.82  1326.4  835.47    1356  854.94  1401.2  868.72
#Mann= 6, -1 ,  0
       0     0.1       0  660.77    0.05       0   693.4   0.045       0
  728.45    0.05       0 1113.89    0.06       0 1232.34     0.1       0
Bank Sta=693.4,728.45
XS Rating Curve= 0 ,0
Exp/Cntr(USF)=0,0
Exp/Cntr=0.3,0.1

Type RM Length L Ch R = 1 ,52000   ,525.2,500,468.7
XS GIS Cut Line= 6
1618568.00584225408117.0505337571619042.80082442408896.651664838
 1619094.5769676408975.0140409171619168.40523201409044.693363503
1619252.93754326409108.3165958371619443.28197885409219.911517009
#Sta/Elev= 30
       0   968.7      23   955.9   131.3  927.68   178.3  901.89   243.8  884.86
   281.7  858.82   309.3  850.27   342.1  828.92   370.1  820.04   398.2  799.77
     459     776   533.9  765.31   566.6  754.05   632.1  746.81   642.8  741.71
   660.5  725.64   678.9  720.06   695.2  719.66   741.8  720.14   756.4  725.87
   903.3   723.9  1078.9  739.26  1110.8  738.03  1127.9  750.79  1167.9   766.2
  1202.2  772.54  1263.1  776.22  1297.4  791.32  1397.6  824.05  1434.7  831.31
#Mann= 7, -1 ,  0
       0     0.1       0   678.9   0.045       0   741.8     0.1       0
  770.27    0.05       0 1002.81    0.06       0 1056.73    0.07       0
 1148.25     0.1       0
Bank Sta=678.9,741.8
XS Rating Curve= 0 ,0
Exp/Cntr(USF)=0,0
Exp/Cntr=0.3,0.1

Type RM Length L Ch R = 1 ,51500   ,509,500,496.5
XS GIS Cut Line= 6
 1618038.0787525409120.6436709171618788.00802693409146.958907008
1619140.91578567409159.3430685851619239.19282009409165.641284332
 1619339.4071866409193.8466085051619439.84596209 409234.24285318
#Sta/Elev= 30
       0  868.45   146.1  879.88   170.1  884.17   190.2  883.26   270.2  903.46
   294.2  900.27   314.2   904.7   330.2  913.54   374.3   915.1   414.3  895.78
   446.3     869   474.3  852.11   498.3  829.13   514.4  822.34   550.9  793.62
   622.4   758.2   658.4  723.25   666.4  718.48   698.5  718.07   714.5   718.6
   774.5  727.62   954.6  728.14   982.6  736.46    1015  734.11  1034.7     746
  1086.7  768.48  1194.9  800.48  1261.1  815.79  1356.2  832.79  1414.4  836.48
#Mann= 5, -1 ,  0
       0     0.1       0   666.4   0.045       0   714.5     0.1       0
  895.39    0.06       0 1096.64     0.1       0
Bank Sta=666.4,714.5
XS Rating Curve= 0 ,0
Exp/Cntr(USF)=0,0
Exp/Cntr=0.3,0.1

Type RM Length L Ch R = 1 ,51000   ,461.7,500,511.5
XS GIS Cut Line= 6
1618046.33431342409356.2721366731618262.77777818409518.173715755
1618377.43634151409601.5662655091618493.64411435 409671.59630917
1618592.63768275409685.5847982621619483.20545542 409484.92771925
#Sta/Elev= 30
       0  845.79    33.9  851.65    80.8  854.05   341.2   850.3   415.2  842.32
   447.9  828.64   472.1   830.8     489  827.52   547.3  804.34     627  783.12
   733.3  763.65   757.9  756.64   782.5  740.74   798.7  725.89   820.3  717.88
     859  716.91   872.7  717.83     885  723.21   983.4  724.85  1042.6  727.75
  1073.6     733  1102.3  732.48  1151.5  754.59  1217.3  756.64  1264.9  770.96
  1315.5  790.38  1360.6  817.79  1430.3   848.1  1479.5  863.66  1560.6  882.63
#Mann= 9, -1 ,  0
       0     0.1       0  182.45    0.05       0  242.45     0.1       0
   820.3   0.045       0   872.7     0.1       0  995.23    0.06       0
 1102.73     0.1       0 1226.48    0.06       0 1303.36     0.1       0
Bank Sta=820.3,872.7
XS Rating Curve= 0 ,0
Exp/Cntr(USF)=0,0
Exp/Cntr=0.3,0.1

Type RM Length L Ch R = 1 ,50500   ,467.2,500.3,525
XS GIS Cut Line= 6
1618046.84743576 409363.88006109 1618264.8302675409548.605085343
 1618381.5409921409662.429004669 1618501.8534155409793.321787506
1618676.44230518410017.7540814281619217.20041001410643.503486082
#Sta/Elev= 30
       0  846.56    66.8  853.05   327.7  846.92   381.4  842.62   441.2  833.46
   464.4  820.48   484.3  820.46   630.7   774.6   661.3  759.56   681.8  734.79
   698.8  723.72     887  723.87  1006.1  716.62  1028.6  715.88  1048.6  716.51
  1062.8  723.65  1122.4  729.23  1134.2  739.46  1155.3  764.25  1186.9  779.54
  1218.4  801.35  1231.6  805.81  1280.9  809.37  1302.6  806.31  1490.2  850.96
  1525.2  854.44  1597.3  847.93  1665.7  816.42  1699.5  831.97  1738.1   858.7
#Mann= 7, -1 ,  0
       0     0.1       0  157.53    0.05       0  257.53     0.1       0
  1006.1   0.045       0  1048.6     0.1       0 1097.71    0.07       0
 1147.71     0.1       0
Bank Sta=1006.1,1048.6
XS Rating Curve= 0 ,0
Exp/Cntr(USF)=0,0
Exp/Cntr=0.3,0.1

Type RM Length L Ch R = 1 ,50000   ,511.4,499.8,458.4
XS GIS Cut Line= 6
1618040.74967892409362.1494214981618240.43989635409541.682855085
1618404.29291509409765.6331945961618413.93528426409873.658897176
1618252.34111926410171.2062023431618234.52750659410796.674439594
#Sta/Elev= 30
       0  844.96    32.5  850.83    71.9  852.66   335.7  844.49   409.9   836.6
     453  827.68   476.3  814.69   499.6  813.19   638.1  770.23   646.4  766.35
   668.4  744.31   711.6  726.17   753.4  719.76   833.5  720.64   856.4  715.72
   903.4   715.2  909.53715.7566   921.6  720.02   993.1  721.95  1066.1  730.74
  1206.7  729.46  1227.2  737.53  1266.7  761.35  1290.7  766.84  1342.7  788.55
  1392.4  803.53  1410.7  813.84  1426.7  814.92  1446.7  828.19    1623  903.08
#Mann= 7, -1 ,  0
       0     0.1       0  161.73    0.05       0  268.65     0.1       0
   856.4   0.045       0  909.53     0.1       0 1075.87    0.06       0
 1275.86     0.1       0
Bank Sta=856.4,909.53
XS Rating Curve= 0 ,0
Exp/Cntr(USF)=0,0
Exp/Cntr=0.3,0.1

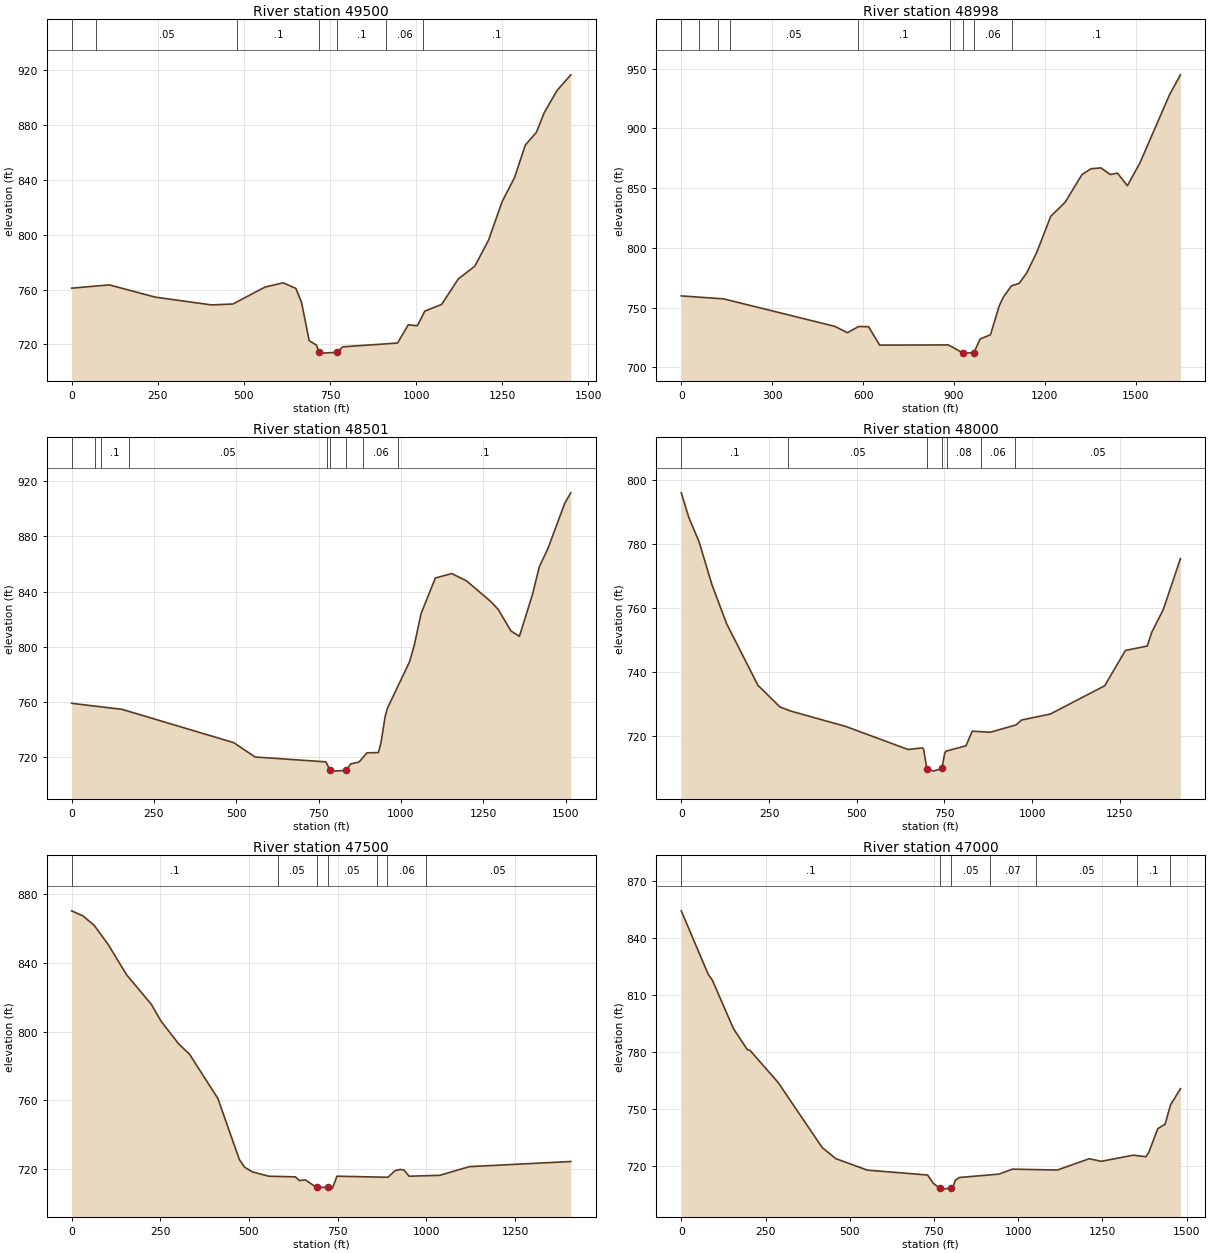
Type RM Length L Ch R = 1 ,49500   ,487.3,502.3,516.2
XS GIS Cut Line= 6
1617702.26807243409498.0799239281617673.99056992409621.032433927
1617656.33903043 409736.01612784 1617672.9774486409836.160612583
1618055.73586942410655.9007710071618153.40496543  410830.6307365
#Sta/Elev= 30
       0  760.99   109.2  763.41   242.5  754.49   406.4   748.8   468.3  749.48
   561.2  761.79     614   764.9   650.9  760.85   667.4  750.64   689.5  722.82
   710.2  719.59   719.2  714.31   728.2  713.71   770.2   714.3   786.9   718.3
   946.1  721.05   977.1   734.3  1003.5  733.69  1025.5  744.34  1074.1  749.18
  1122.2  767.66  1170.5  777.07  1210.2  795.95  1249.5  823.95  1285.7  841.54
  1316.9   865.2  1349.1  874.47  1372.3  889.01  1409.4  905.04    1449  916.35
#Mann= 7, -1 ,  0
       0     0.1       0      70    0.05       0  480.89     0.1       0
   719.2   0.045       0   770.2     0.1       0  912.14    0.06       0
 1019.64     0.1       0
Bank Sta=719.2,770.2
XS Rating Curve= 0 ,0
Exp/Cntr(USF)=0,0
Exp/Cntr=0.3,0.1

Type RM Length L Ch R = 1 ,48998   ,477.7,496.9,511.6
XS GIS Cut Line= 6
1617685.33569159409507.4791833461617537.51840192409911.355016008
1617496.01028284410049.2904356721617453.78398934410286.673163012
1617392.61317992410456.8158673351617244.39497243411090.973391667
#Sta/Elev= 30
       0  759.79   139.9  757.29   506.6   734.3   548.3     729   585.6  734.17
   618.1  734.02   654.6  718.62   881.3  718.77   928.1  712.32   935.9   711.9
   965.9  712.34   986.3  723.68  1020.5  727.32  1049.2   751.4  1062.9  758.78
  1089.5  768.19    1115  770.24  1139.5  778.82  1172.5   795.8  1219.4  826.41
    1267   838.2  1322.6  861.39  1352.6  866.17    1385  866.88  1415.8  861.34
  1439.5  862.51  1472.3  851.97  1513.4  870.93    1612  928.44  1647.4  944.76
#Mann= 9, -1 ,  0
       0     0.1       0      60    0.05       0     120     0.1       0
  159.86    0.05       0  584.18     0.1       0  885.29    0.06       0
   928.1   0.045       0   965.9    0.06       0 1091.69     0.1       0
Bank Sta=928.1,965.9
XS Rating Curve= 0 ,0
Exp/Cntr(USF)=0,0
Exp/Cntr=0.3,0.1

Type RM Length L Ch R = 1 ,48501   ,497.3,500.8,507.5
XS GIS Cut Line= 6
1617680.09029526409499.5999340121617567.62759367409742.096496254
1617495.55490318409848.3210213331617412.08328535409923.222446337
1617166.20910518409999.7646160871616471.73805317410284.014703751
#Sta/Elev= 30
       0  759.09   152.9  754.73     492  730.65   557.3  720.24   772.3  716.71
   785.2  710.48   789.4     710  833.06710.4565   848.1  715.27   872.8  716.54
   897.1  723.27   931.7  723.43   939.7  730.57   952.4  749.75   958.5  755.15
    1026  788.98  1039.9  800.33  1061.5   824.1  1104.7  849.82  1154.7  853.01
  1199.9  847.65  1273.5  832.67  1295.6  827.06    1334  811.53    1360  807.57
  1399.8  837.97  1420.5  857.95  1446.5  871.07  1497.8  903.95  1516.1  911.47
#Mann= 9, -1 ,  0
       0     0.1       0      70    0.05       0      90     0.1       0
  174.31    0.05       0  775.71     0.1       0   785.2   0.045       0
  833.06     0.1       0  885.72    0.06       0  990.72     0.1       0
Bank Sta=785.2,833.06
XS Rating Curve= 0 ,0
Exp/Cntr(USF)=0,0
Exp/Cntr=0.3,0.1

Type RM Length L Ch R = 1 ,48000   ,509.7,500,487.3
XS GIS Cut Line= 6
1617532.47051176409299.0340621771617101.00976051409559.995810583
 1617016.6241025409588.4363705071616842.49256101409605.849065334
1616589.60002217409652.2010067551616205.19921617409750.100089177
#Sta/Elev= 30
       0  795.95    21.6  788.24    50.5  780.73      88  767.09   129.3  755.08
   218.2  735.92   280.9  729.15   311.2  727.86   469.6     723   646.4  715.84
   686.6  716.34   690.6  715.98   698.7  710.56   701.3   709.8   718.8  709.09
   742.9  709.93   750.9  714.78   754.9  715.34   811.6     717   829.1  721.56
   880.5  721.23   953.8   723.5   970.1  725.05  1051.9  726.91  1206.7  735.74
  1265.8  746.76    1328  748.13  1340.5  752.35  1373.8  759.56  1422.6  775.44
#Mann= 7, -1 ,  0
       0     0.1       0  305.31    0.05       0   701.3   0.045       0
   742.9    0.05       0  758.64    0.08       0  853.76    0.06       0
  951.54    0.05       0
Bank Sta=701.3,742.9
XS Rating Curve= 0 ,0
Exp/Cntr(USF)=0,0
Exp/Cntr=0.3,0.1

Type RM Length L Ch R = 1 ,47500   ,499.9,500,498.8
XS GIS Cut Line= 6
1617271.52352709408762.1401228461617011.00698775408911.662461594
1616849.03880775409015.6235397611616779.24826492409068.720874503
1616378.26711151409412.4213025871616131.50152892409580.467882499
#Sta/Elev= 30
       0  870.13    31.4  867.25    63.5  861.74   103.1  850.54   155.4  832.86
   224.3  815.93   252.6   805.9   302.1  792.76   332.2   786.9   412.2  761.18
   472.9  725.64   487.3  721.26   509.1  718.48     556  715.93   630.9  715.58
   642.2  713.37   658.5  713.85   690.5  709.48   721.8  709.47   732.2  708.44
   735.9  709.19     748  715.95   891.9  715.33   912.2  719.21   927.1  719.88
   937.3   719.5   951.5  715.94  1037.8  716.45  1121.3   721.5  1407.4  724.48
#Mann= 7, -1 ,  0
       0     0.1       0  580.58    0.05       0   690.5   0.045       0
   721.8    0.05       0  860.58    0.07       0  890.58    0.06       0
  998.08    0.05       0
Bank Sta=690.5,721.8
XS Rating Curve= 0 ,0
Exp/Cntr(USF)=0,0
Exp/Cntr=0.3,0.1

Type RM Length L Ch R = 1 ,47000   ,476.1,500.1,530.9
XS GIS Cut Line= 6
1617046.18113001408436.3048164991616925.47795933408463.785076499
1616805.14683518408496.4943286781616690.22810176408534.839396343
1616593.03439851408575.7471229291615850.33050334409255.244123504
#Sta/Elev= 30
       0  854.42    80.1  820.89    92.4  817.83   154.8  792.34   195.7  781.34
     204  780.86   287.5  763.94   418.4  729.61   458.7  723.79   552.2  717.74
   731.1  715.16   747.4  710.93   766.6  708.22   774.5  707.72   801.6  708.32
     807   709.2     814  712.55   825.9  713.87   942.6  715.61   983.1  718.26
  1116.1  717.78  1211.1  723.75  1246.6  722.39  1341.4   725.6  1379.5   724.8
    1388  727.23  1414.3  739.59  1436.1  741.93  1452.2  752.11  1481.7  760.67
#Mann= 7, -1 ,  0
       0     0.1       0   766.6   0.045       0   801.6    0.05       0
  916.34    0.07       0 1053.84    0.05       0  1352.9     0.1       0
 1452.12    0.05       0
Bank Sta=766.6,801.6
XS Rating Curve= 0 ,0
Exp/Cntr(USF)=0,0
Exp/Cntr=0.3,0.1

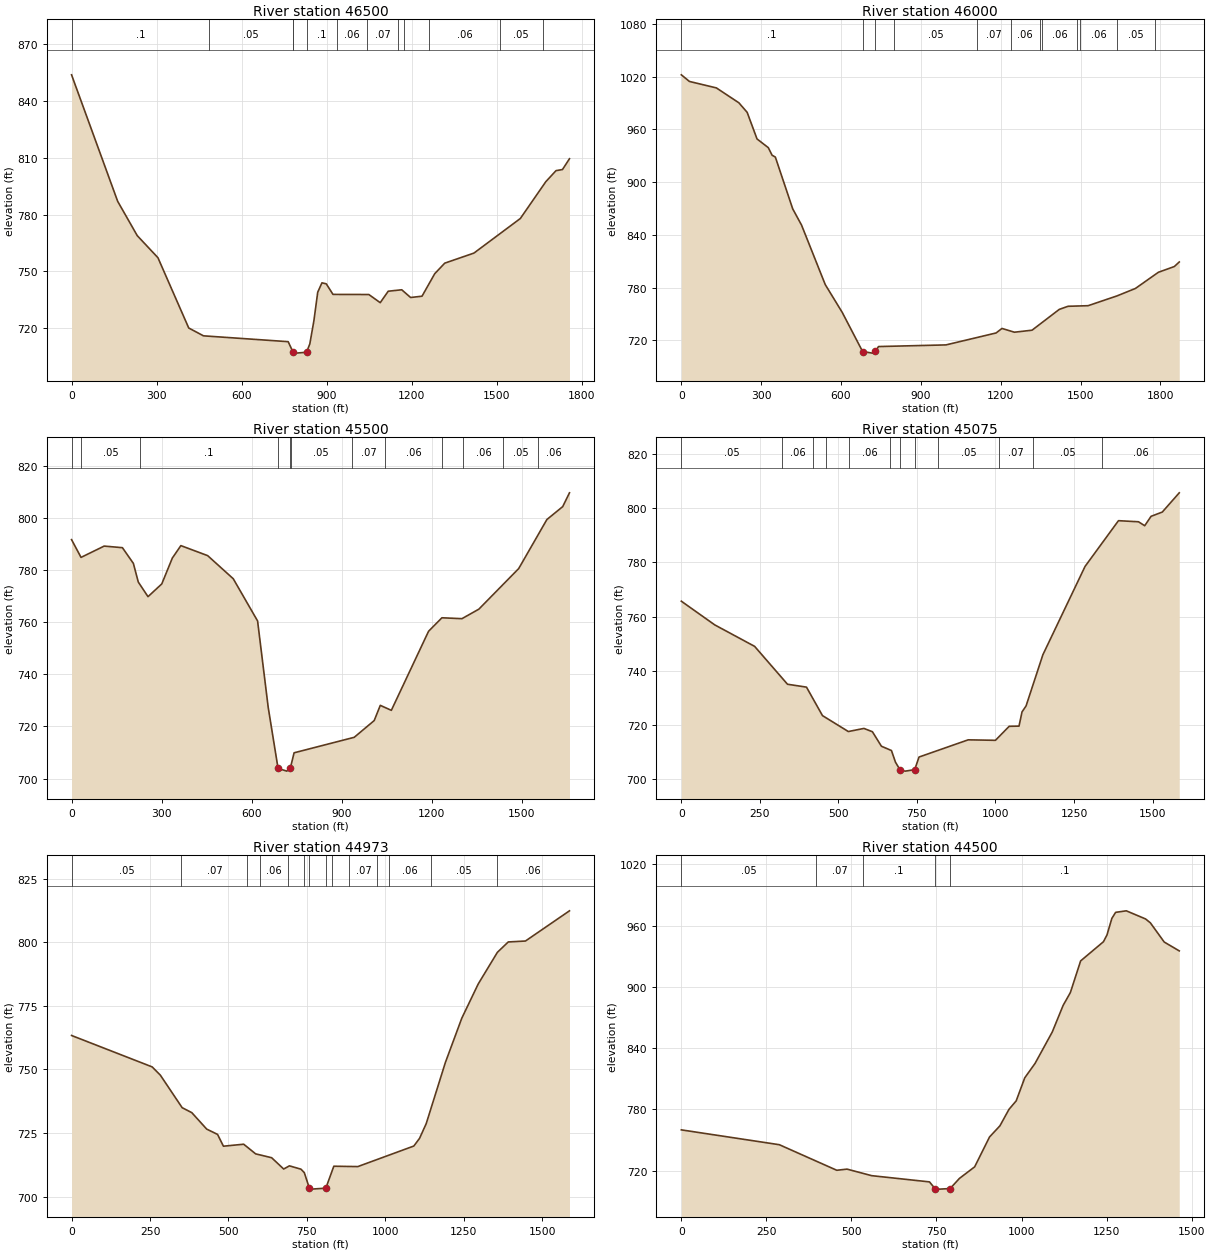
Type RM Length L Ch R = 1 ,46500   ,526,499.9,457.3
XS GIS Cut Line= 6
1617044.24117325408431.2667688431616561.99837135408495.138032168
1616102.92842335408250.4974453451615986.16553351408262.914743334
1615725.90457109408428.2982708361615521.70386401408668.690506592
#Sta/Elev= 30
       0  853.92   162.8  786.97   231.9  768.82   304.8  757.17   413.6  719.96
   465.6  715.82   764.5  712.73   782.3  707.01   791.7  706.67   829.3  707.12
   840.9  711.55   855.4  723.91   868.8   738.9   883.7  743.87     899  743.33
   922.7  737.74  1049.2  737.68  1089.4  733.36  1117.6  739.42  1165.3  740.19
  1196.6   736.1  1236.9  736.79  1281.7  748.68  1317.1  754.28  1420.1   759.6
  1583.9   777.9  1673.9   797.4  1709.8  803.22  1732.6  803.81  1757.3  809.52
#Mann= 12, -1 ,  0
       0     0.1       0  484.95    0.05       0  781.71     0.1       0
   782.3   0.045       0   829.3     0.1       0   936.7    0.06       0
  1044.2    0.07       0 1151.62    0.06       0 1171.62    0.05       0
 1261.62    0.06       0 1511.43    0.05       0 1663.18    0.06       0
Bank Sta=782.3,829.3
XS Rating Curve= 0 ,0
Exp/Cntr(USF)=0,0
Exp/Cntr=0.3,0.1

Type RM Length L Ch R = 1 ,46000   ,514.7,500,474.1
XS GIS Cut Line= 6
1616874.30024017407393.5874137581616382.84649867407960.649927929
  1616026.730413408177.2636679261615872.48892359 408287.48359184
1615736.04562692408406.8852559181615524.23929201408663.337498918
#Sta/Elev= 30
       0 1022.25    30.4 1014.71   131.6 1007.36   216.3  990.38   247.4  979.51
   284.4  949.23   326.8  939.31   341.1  930.67   353.3  928.56   418.6  869.57
   451.7  851.16   540.8  783.37   604.8  751.61   681.3  707.08   718.5  705.32
   729.1  707.24   740.9   712.8   994.4  714.68  1182.9  728.29  1204.9  733.44
  1251.7  729.14  1317.9  731.43  1420.2  755.12    1453  758.66  1528.5  759.33
  1637.4  770.51  1706.3  778.95  1792.7  797.39  1852.6  803.93  1871.1  809.12
#Mann= 12, -1 ,  0
       0     0.1       0   681.3   0.045       0   729.1     0.1       0
  800.39    0.05       0 1111.84    0.07       0 1237.24    0.06       0
 1347.24    0.05       0 1356.81    0.06       0 1486.81    0.05       0
 1496.81    0.06       0 1638.12    0.05       0 1781.18    0.06       0
Bank Sta=681.3,729.1
XS Rating Curve= 0 ,0
Exp/Cntr(USF)=0,0
Exp/Cntr=0.3,0.1

Type RM Length L Ch R = 1 ,45500   ,435.5,424.8,409.5
BEGIN DESCRIPTION:
Structure 13 XS 4
END DESCRIPTION:
XS GIS Cut Line= 6
1615817.44835126407169.3979015051615963.29943751408070.572280258
1615916.35104059408172.9523248371615708.45086583408405.807502165
1615606.18040109408534.7088191661615517.34068376408663.067814425
#Sta/Elev= 30
       0  791.64    31.6  784.83   108.6  789.17   169.4  788.56   205.9  782.53
   222.2  775.39   254.6  769.77   300.5  774.66   335.7  784.59   364.1  789.35
   453.3  785.51   538.5  776.65   619.6  760.45     655  727.28  687.79 703.904
   716.9  702.85   729.1  704.21   741.2  709.88   941.5  715.82    1008  722.24
  1028.3  728.08  1065.1  726.17  1189.1   756.5  1233.6  761.67  1300.3  761.33
  1356.6  764.98  1489.3  780.55  1583.2  799.36  1635.9  804.31  1658.4   809.6
#Mann= 12, -1 ,  0
       0     0.1       0      30    0.05       0  228.83     0.1       0
  687.79   0.045       0   729.1     0.1       0  730.39    0.05       0
  932.95    0.07       0 1045.58    0.06       0 1235.38    0.05       0
 1305.38    0.06       0 1437.75    0.05       0 1552.29    0.06       0
Bank Sta=687.79,729.1
XS Rating Curve= 0 ,0
Exp/Cntr(USF)=0,0
Exp/Cntr=0.3,0.1

Type RM Length L Ch R = 1 ,45075   ,105.2,102.3,102.5
BEGIN DESCRIPTION:
Structure 13 XS 3
END DESCRIPTION:
XS GIS Cut Line= 6
1615535.78560173407296.4539844961615369.27854002407772.188446517
1615569.76663473407986.2689544271615630.93249413408033.842400629
1615746.46800634408081.4158468311615484.81405223408604.723755055
#Sta/Elev= 30
       0  765.65   106.5   756.9   233.2  748.99     338     735   398.4  733.94
   449.3  723.43   531.6  717.55   581.2   718.7   608.2  717.48   636.9  712.13
   668.9  710.54   681.7  706.22   696.3  703.41   712.8  702.94  742.79703.4653
   756.6  708.14   913.1  714.49   999.9  714.31  1043.6  719.48  1074.9  719.55
  1084.5   724.8  1097.3  726.98  1150.9  745.89  1285.1  778.48  1391.5  795.37
  1455.1  794.97    1475  793.51  1495.3  796.98  1531.1  798.56    1585  805.65
#Mann= 12, -1 ,  0
       0    0.05       0     320    0.06       0     420    0.05       0
     460    0.07       0  534.03    0.06       0  664.03    0.07       0
   696.3   0.045       0  742.79    0.07       0  817.33    0.05       0
 1009.88    0.07       0 1119.88    0.05       0 1339.88    0.06       0
Bank Sta=696.3,742.79
XS Rating Curve= 0 ,0
Exp/Cntr(USF)=0,0
Exp/Cntr=0.3,0.1

Type RM Length L Ch R = 1 ,44973   ,437.6,472.9,512.9
BEGIN DESCRIPTION:
Structure 13 XS 2
END DESCRIPTION:
XS GIS Cut Line= 6
1615481.39246942407275.8559137631615263.43943444407792.214446322
 1615471.1530651408014.555797452 1615564.7704761408097.933804125
1615653.99957096408131.5775612041615454.23112252408591.131341854
#Sta/Elev= 30
       0  763.35   256.9     751     283  747.75   352.4  734.98   383.1  733.03
   430.6  726.56   465.3  724.47   483.9  719.84   548.5  720.62   586.6  716.83
   637.6  715.31   675.9  710.87   694.2  712.12     731  710.81   741.6  709.46
     758  703.29   763.5  702.97   810.2  703.34   835.7  711.97   912.2  711.83
  1090.7  719.91  1108.9  722.93  1130.2  728.74  1191.2  752.75  1243.5  770.15
  1295.9  783.61  1356.9  796.03  1391.6  800.11  1446.3  800.47  1586.6  812.34
#Mann= 14, -1 ,  0
       0    0.05       0     350    0.07       0     560     0.1       0
  600.47    0.06       0  690.47     0.1       0  740.47    0.07       0
     758   0.045       0   810.2    0.07       0  830.47    0.05       0
  884.74    0.07       0  974.74    0.05       0 1010.11    0.06       0
 1145.47    0.05       0 1355.47    0.06       0
Bank Sta=758,810.2
XS Rating Curve= 0 ,0
Exp/Cntr(USF)=0,0
Exp/Cntr=0.3,0.1

Type RM Length L Ch R = 1 ,44500   ,497.4,500,508.8
BEGIN DESCRIPTION:
Structure 13 XS 1
END DESCRIPTION:
XS GIS Cut Line= 6
1615403.76118651407230.0365597611615325.83581743407449.187368169
1615282.82409242407554.6920784261615233.59289168 407650.82443209
1615174.88795659407727.1645025011614486.77712809408327.058315843
#Sta/Elev= 30
       0  760.01     288   745.5     457  720.47     487   721.6   559.4   715.2
   729.5   709.1   745.6  702.59   759.9  702.02   790.3  702.61   817.4  712.48
   862.3  723.85     906  753.06   936.6     764   963.1  780.08   984.4  788.42
  1009.5  810.94  1039.9   825.1  1090.5  855.87  1122.3  881.81  1143.6  894.39
  1173.8  925.38  1240.8  944.12  1251.2  950.74  1265.6     967  1276.7  972.91
  1308.1  974.39  1364.6  966.46  1378.8  962.63  1419.5  943.85  1463.7  935.18
#Mann= 5, -1 ,  0
       0    0.05       0  396.53    0.07       0  534.54     0.1       0
   745.6   0.045       0   790.3     0.1       0
Bank Sta=745.6,790.3
XS Rating Curve= 0 ,0
Exp/Cntr(USF)=0,0
Exp/Cntr=0.3,0.1

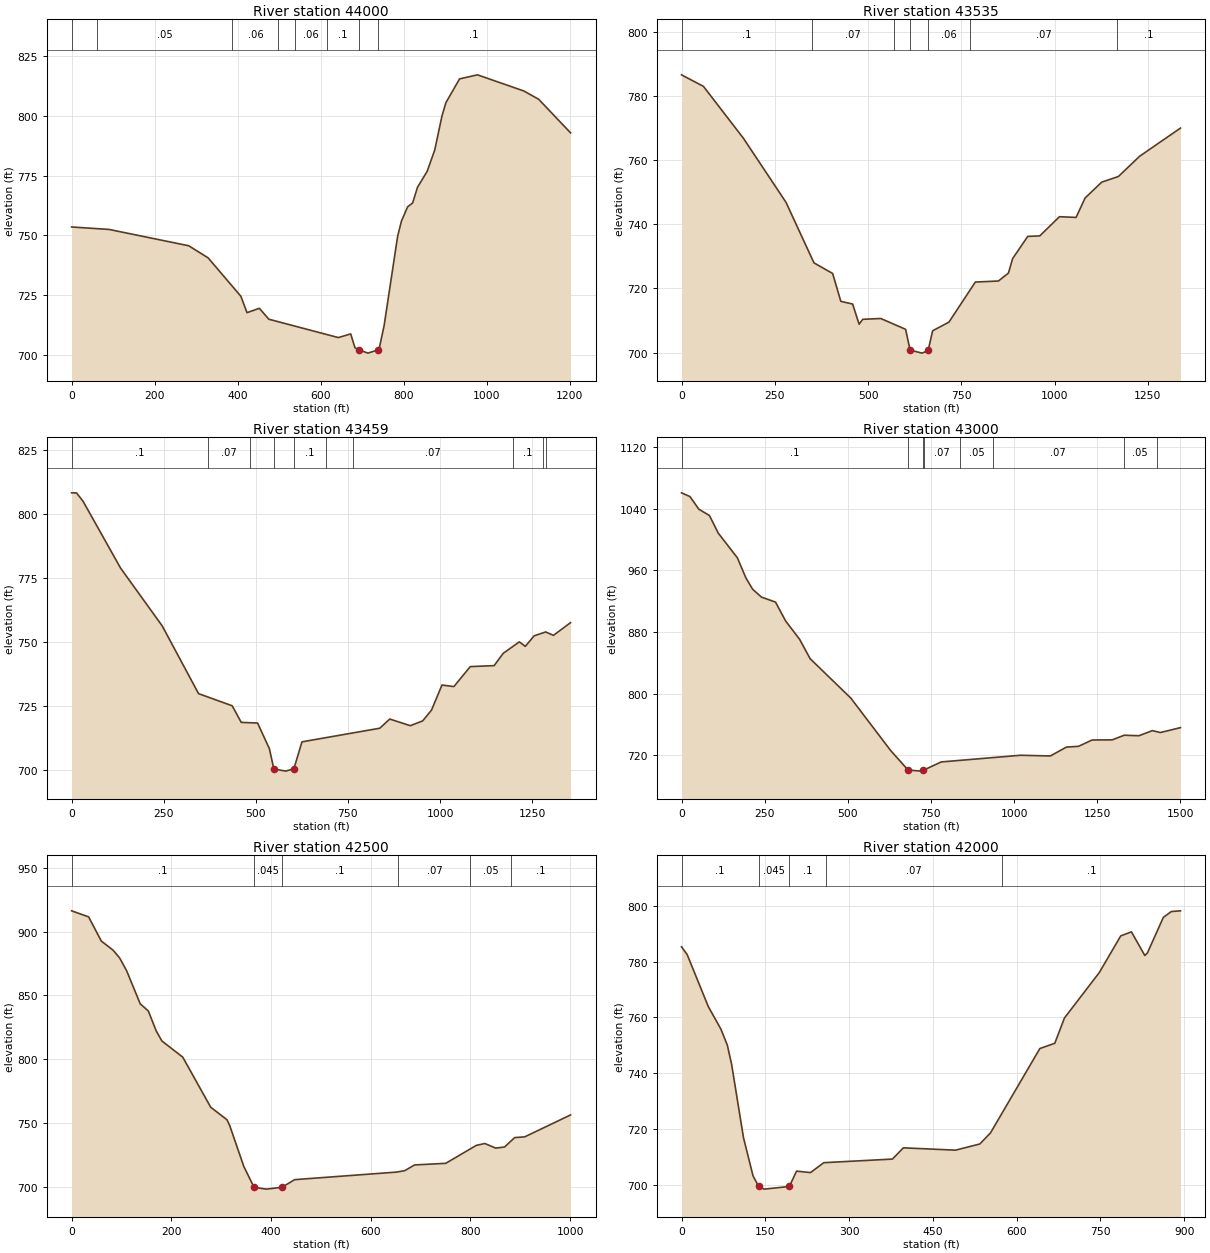
Type RM Length L Ch R = 1 ,44000   ,459.4,465.1,475.8
BEGIN DESCRIPTION:
Structure 12 XS 4
END DESCRIPTION:
XS GIS Cut Line= 6
1615331.34663318407142.8201987591615245.22574243 407193.31156759
1615070.52432017407285.8819205021614901.71888351 407374.52150701
1614823.86700509407414.4735268351614263.45244351407694.680971667
#Sta/Elev= 30
       0  753.49    90.4  752.45   282.2  745.61     329  740.53   407.9  724.43
   422.7  717.56   452.4  719.39   475.3  714.81   642.7  707.12   672.5  708.66
   682.8  702.88  692.28701.9941   714.2   700.6   738.1  701.97     741  702.37
     753   712.1   785.6  749.58   794.7  755.91   809.6   761.9   821.8  763.58
   833.5  770.13   856.8  776.83   875.1   785.8   892.5  800.08     902  805.62
   934.8  815.56   977.9  817.27  1089.7   810.5  1125.5  807.02  1202.3  792.95
#Mann= 8, -1 ,  0
       0    0.06       0      60    0.05       0  387.54    0.06       0
  498.21    0.05       0  538.21    0.06       0  615.71     0.1       0
  692.28   0.045       0   738.1     0.1       0
Bank Sta=692.28,738.1
XS Rating Curve= 0 ,0
Exp/Cntr(USF)=0,0
Exp/Cntr=0.3,0.1

Type RM Length L Ch R = 1 ,43535   ,75.9,76.4,79
BEGIN DESCRIPTION:
Structure 12 XS 3
END DESCRIPTION:
XS GIS Cut Line= 6
1614992.47378803406741.7748771961614672.41877665407094.111576836
1614589.04076998407034.1379229131614406.19426412407053.153959522
1614312.93323913407113.5052254931614245.99547652407569.591835238
#Sta/Elev= 30
       0  786.53    58.8  782.93   165.8  766.78   280.1   746.8     355  727.95
   405.1  724.64     427  715.96   458.6  715.12     476  708.85   485.8  710.37
   534.1  710.62   600.6  707.25   612.7  700.76   644.9  699.83     661  700.66
   673.1  706.79   716.8  709.49   787.5  721.97   849.5   722.3   876.3  724.78
   887.5  729.28     928   736.2   960.2  736.35  1012.9  742.33  1057.5  742.11
  1081.7  748.16  1126.3   753.1    1171  754.86  1227.7  761.15  1337.3  769.94
#Mann= 7, -1 ,  0
       0     0.1       0     350    0.07       0  569.83    0.06       0
   612.7   0.045       0     661    0.06       0  773.41    0.07       0
 1166.34     0.1       0
Bank Sta=612.7,661
XS Rating Curve= 0 ,0
Exp/Cntr(USF)=0,0
Exp/Cntr=0.3,0.1

Type RM Length L Ch R = 1 ,43459   ,498.7,458.5,388.7
BEGIN DESCRIPTION:
Structure 12 XS 2
END DESCRIPTION:
XS GIS Cut Line= 6
1614945.14073183406673.8913304251614664.58056573406979.419324564
1614563.64929449406963.3288320481614358.86120792406985.270412752
1614265.60018294407045.6216787231614195.73687623407558.756398297
#Sta/Elev= 30
       0  808.22    13.3  808.19    31.1  804.92   132.8  778.86   246.1  756.22
   344.5  729.82   435.8  725.08   460.4  718.59   504.8  718.34   536.9  708.28
   548.9  700.39   581.2  699.56  603.33700.4988   625.2  710.99   836.3  716.31
   863.5   719.9   919.2   717.3   952.7  719.16   976.8  723.38  1005.2  733.17
  1037.5  732.57    1082  740.37  1146.8  740.75  1171.2  745.53  1215.2  750.03
  1231.3  748.27  1255.4  752.39  1286.7   753.9  1307.7  752.57  1354.2  757.54
#Mann= 10, -1 ,  0
       0     0.1       0     370    0.07       0  484.78     0.1       0
   548.9   0.045       0  603.33     0.1       0  689.14    0.05       0
  763.33    0.07       0 1198.37     0.1       0 1278.37    0.05       0
 1288.37     0.1       0
Bank Sta=548.9,603.33
XS Rating Curve= 0 ,0
Exp/Cntr(USF)=0,0
Exp/Cntr=0.3,0.1

Type RM Length L Ch R = 1 ,43000   ,503.4,500,497.6
BEGIN DESCRIPTION:
Structure 12 XS
END DESCRIPTION:
XS GIS Cut Line= 6
1613725.89446351406269.4016700091614220.02733351406834.130855501
1614258.58368684406899.9850545081614255.64406018 407018.18462126
1614205.62677176407338.860161006 1614182.0588805407568.674355984
#Sta/Elev= 30
       0 1060.43    25.4 1055.58      52 1039.25    83.9 1031.06   110.5 1008.19
   168.2  976.04   193.7  949.99   213.6  935.55   240.3  925.22   282.8  918.66
   313.2  894.12     355  870.59   386.8   845.3   509.1  794.21     629  726.17
   681.3   700.9   720.2  699.47  727.55700.6831     781  711.39  1020.1  720.06
  1109.2  719.13  1157.8  730.66  1194.2  731.67  1234.7  739.85  1295.3  740.03
  1331.5  746.04  1375.7  745.36  1415.9     752  1440.2  749.53  1500.5  755.88
#Mann= 8, -1 ,  0
       0     0.1       0   681.3   0.045       0  727.55     0.1       0
  730.39    0.07       0   836.7    0.05       0   936.7    0.07       0
 1329.49    0.05       0 1429.49     0.1       0
Bank Sta=681.3,727.55
XS Rating Curve= 0 ,0
Exp/Cntr(USF)=0,0
Exp/Cntr=0.3,0.1

Type RM Length L Ch R = 1 ,42500   ,504.2,500,497.1
XS GIS Cut Line= 6
1613530.88435484 406869.552372591613864.17666726407176.535354421
1613918.77071817407227.9666820021614049.92006217407353.112757176
1614114.24900176407431.6522982571614142.22108368 407619.45890479
#Sta/Elev= 30
       0  916.29    34.1  911.55    59.6  892.61    83.2  885.48    96.4  879.37
   110.6  869.17   137.6  843.48   153.9  837.86   169.7  822.23   181.1  814.36
   222.9  801.72     279  762.48   311.6  752.69   317.1  748.16   345.5     716
     366  699.71   390.8  698.33   421.9  699.79   447.4  705.75   651.1  711.65
   668.1  712.77   687.9  717.27   750.4  718.54   811.8   732.6   828.8  734.06
   850.7  730.46   868.4  731.32   888.7  738.68   908.9  739.28  1000.8  756.44
#Mann= 6, -1 ,  0
       0     0.1       0     366   0.045       0   421.9     0.1       0
  655.64    0.07       0  799.41    0.05       0  880.93     0.1       0
Bank Sta=366,421.9
XS Rating Curve= 0 ,0
Exp/Cntr(USF)=0,0
Exp/Cntr=0.3,0.1

Type RM Length L Ch R = 1 ,42000   ,357.7,355.7,356.4
XS GIS Cut Line= 6
1613407.61440154 407463.967472271613515.94868918407532.346978754
1613659.17149983407632.9064889251613886.79309183407792.725066915
1614048.55753209407906.3042360841614110.64927143408002.267298758
#Sta/Elev= 30
       0  785.27    10.1   782.5    47.9  763.89    70.4  755.84      82  750.06
    89.6  743.29     111  716.86   128.1  703.21   138.1  699.46   147.9   698.5
  193.09699.4547   205.9  704.94   230.9  704.43   254.7  707.97   377.6  709.26
   397.1  713.29   490.4  712.45     534  714.66   553.1  718.63   641.5  748.84
   668.2  750.72   685.5  759.77     748  776.08   786.3  789.18   805.4  790.63
   829.4  782.15     834  783.06   862.5  795.79   876.8   797.9   893.2  798.15
#Mann= 5, -1 ,  0
       0     0.1       0   138.1   0.045       0  193.09     0.1       0
  258.11    0.07       0  574.36     0.1       0
Bank Sta=138.1,193.09
XS Rating Curve= 0 ,0
Exp/Cntr(USF)=0,0
Exp/Cntr=0.3,0.1

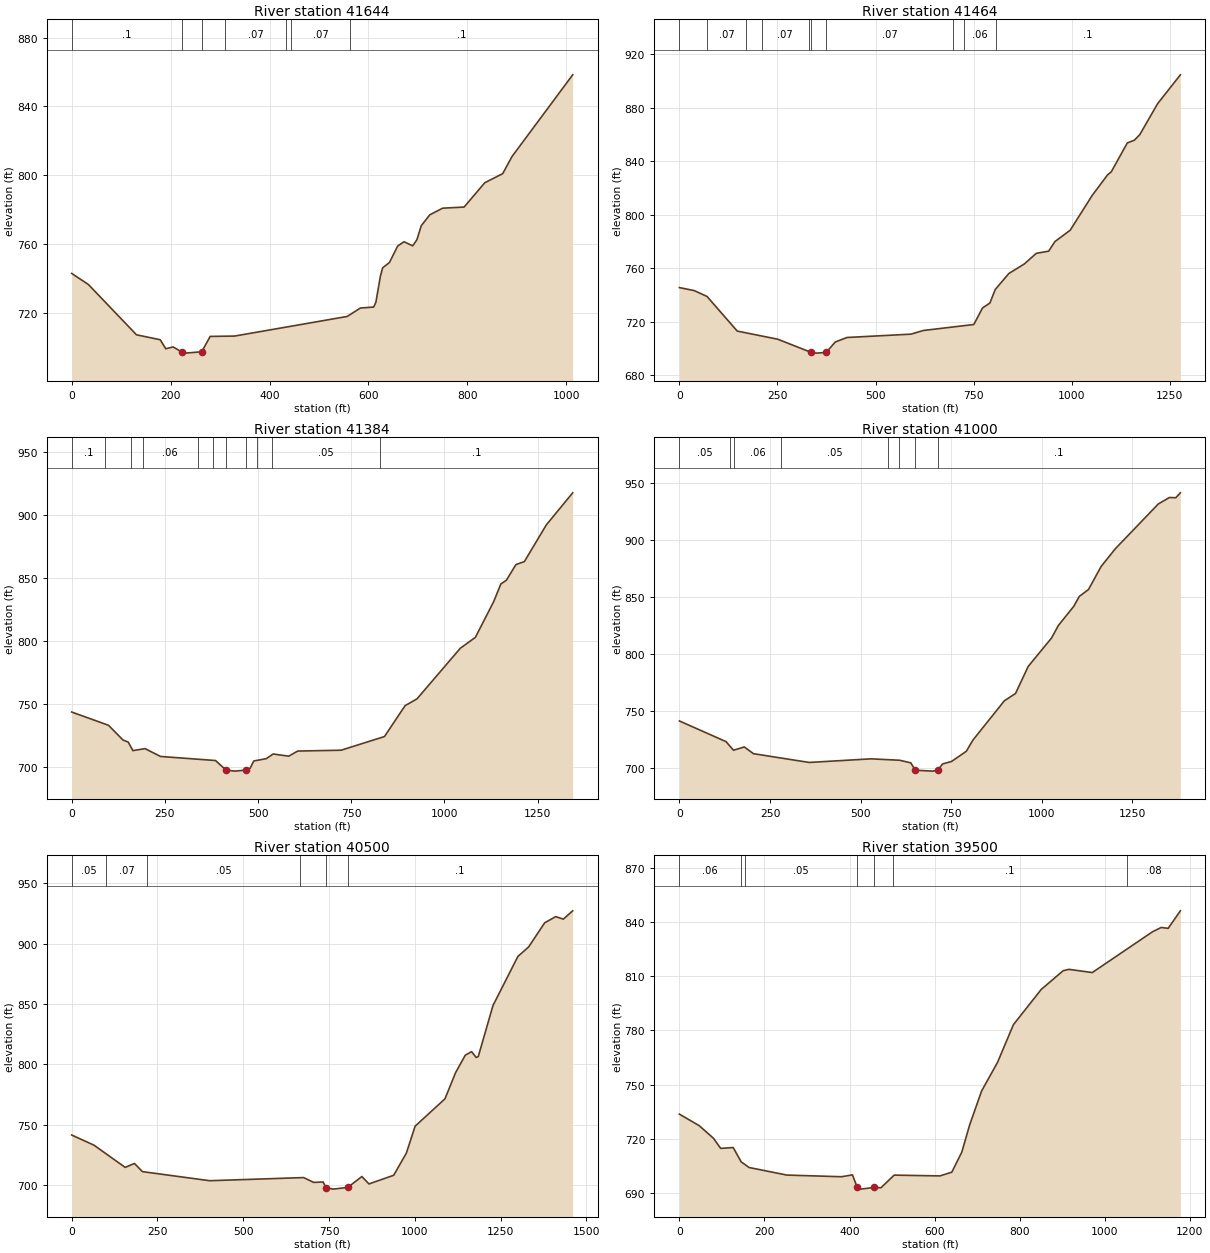
Type RM Length L Ch R = 1 ,41644   ,179,180.1,177.1
BEGIN DESCRIPTION:
Structure 11 XS 4
END DESCRIPTION:
XS GIS Cut Line= 4
1613173.81819511 407719.958113171613451.92547317407920.412060339
1613652.37942033408102.8070933481613805.88019069408471.208942199
#Sta/Elev= 30
       0  743.03    33.6  736.66     131   707.4   178.9  704.54   190.2  699.29
     205  700.35   222.7  697.43   229.6  696.76   262.8  697.54     280  706.47
   329.4  706.67     557  718.06   583.7  722.96   610.5  723.52     615  726.26
   624.1   741.4   628.7  746.32   642.5  749.41     659  758.95     672  761.45
   689.4  759.07     698  762.63   706.7  770.76     724  777.09     750  780.94
   793.4   781.6   835.2  795.73   871.4  800.99   890.3  810.97  1012.9  858.39
#Mann= 7, -1 ,  0
       0     0.1       0   222.7   0.045       0   262.8     0.1       0
     310    0.07       0  432.82    0.06       0  442.82    0.07       0
  562.82     0.1       0
Bank Sta=222.7,262.8
XS Rating Curve= 0 ,0
Exp/Cntr(USF)=0,0
Exp/Cntr=0.3,0.1

Type RM Length L Ch R = 1 ,41464   ,90.3,80.4,81.9
BEGIN DESCRIPTION:
Structure 11 XS 3
END DESCRIPTION:
XS GIS Cut Line= 6
1613110.61199555407727.1816788341613083.52362431 407884.29423202
1613309.26005131408028.7655452951613394.13694786408017.930196799
1613446.50779892407983.6182598961613780.59771087408599.427232731
#Sta/Elev= 30
       0  745.71    37.8  743.47    70.4  739.09   147.5   713.2   250.4  707.15
   336.7  697.19   350.1  696.72   374.3  697.27   397.6  705.09   427.4  708.41
   590.3   710.9     622  713.64   750.6  718.12   772.9  730.51   791.6  734.15
   805.2  744.28     840  756.24   879.4  763.38   909.9  771.31   941.4  772.94
   957.5  780.11   996.4  788.63  1052.4  814.59  1091.8  830.03    1101  832.21
  1141.9  853.79  1160.2  855.95  1173.8  860.05  1219.3  883.22  1277.2  904.74
#Mann= 10, -1 ,  0
       0     0.1       0      70    0.07       0  169.43    0.06       0
  209.43    0.07       0  329.43     0.1       0   336.7   0.045       0
   374.3    0.07       0  696.64    0.05       0  726.64    0.06       0
  806.64     0.1       0
Bank Sta=336.7,374.3
XS Rating Curve= 0 ,0
Exp/Cntr(USF)=0,0
Exp/Cntr=0.3,0.1

Type RM Length L Ch R = 1 ,41384   ,363.1,383.9,397.8
BEGIN DESCRIPTION:
Structure 11 XS 2
END DESCRIPTION:
XS GIS Cut Line= 6
1613060.04703591407705.510981842 1613002.2585106407936.665083082
 1613274.9481144408093.7776362691613356.21322812408101.001201932
1613437.47834184408084.7481791891613730.03275122408639.156843881
#Sta/Elev= 30
       0  743.91    98.7  733.42   137.7  721.71   151.6  720.13   164.1  713.32
   196.9   714.9   238.3   708.7     386  705.47   414.3  697.85   438.9  697.07
   466.6   697.9   478.4  699.17   488.5   705.1     522  706.95   540.5  710.65
   582.4  708.93   606.4  712.97   723.1  713.66   839.3  724.48   894.5  748.95
   926.5  754.34  1042.8   794.5  1083.1  803.09    1132  831.25  1151.6  845.46
  1166.3  848.38  1192.1  860.83  1214.7   863.2  1273.5  892.25  1344.3   917.7
#Mann= 11, -1 ,  0
       0     0.1       0      90    0.07       0     160    0.05       0
     190    0.06       0  338.27     0.1       0  378.27    0.06       0
   414.3   0.045       0   466.6    0.06       0  498.27    0.07       0
  538.27    0.05       0  827.44     0.1       0
Bank Sta=414.3,466.6
XS Rating Curve= 0 ,0
Exp/Cntr(USF)=0,0
Exp/Cntr=0.3,0.1

Type RM Length L Ch R = 1 ,41000   ,465.7,500,547.2
BEGIN DESCRIPTION:
Structure 11 XS 1
END DESCRIPTION:
XS GIS Cut Line= 6
1613012.61724374407672.418223795 1612787.3574321 407951.11221441
1612785.69063526408061.9417200831612892.30295484408301.816896498
1613035.72031893408624.5065398371613156.45203283408896.151009679
#Sta/Elev= 30
       0     741   128.7  722.83   149.3  715.26     179  718.17   204.4  712.25
   358.3  704.56   528.9  707.73   607.7  706.49   638.4  704.22650.7529697.7201
   699.6  696.94713.3629697.8723   725.9  703.21   750.9  705.45   791.6  714.37
     810  724.27   896.6  758.71   927.3   765.1   962.3  788.84  1026.7  813.83
  1045.7  824.88  1088.2  841.71  1103.3  850.35  1128.6  856.37  1163.6  876.69
    1203   892.3  1321.2  931.48  1351.8  937.17  1369.4  936.97  1382.1  941.28
#Mann= 8, -1 ,  0
       0    0.05       0     140    0.07       0     150    0.06       0
     280    0.05       0  576.69    0.06       0  606.69     0.1       0
650.7529   0.045       0713.3629     0.1       0
Bank Sta=650.7529,713.3629
XS Rating Curve= 0 ,0
Exp/Cntr(USF)=0,0
Exp/Cntr=0.3,0.1

Type RM Length L Ch R = 1 ,40500   ,978.7,1000,1047.4
XS GIS Cut Line= 6
 1613015.2185552407649.8245206791612841.53417458407727.181678834
1612686.13506009407939.0666377541612620.31727834408006.517290249
  1612217.092363408332.8781860921611913.32755059408584.060098425
#Sta/Elev= 30
       0  741.46    64.7  733.09   155.9  714.65   182.9   717.9   206.1  711.13
   402.2  703.61     676  706.21   705.2  702.22   732.6  702.54741.2029697.9289
     762  696.64 804.403698.0582   845.7  707.07   866.3  700.94   938.4  708.12
   975.4  726.54  1000.9  748.79  1087.9  771.47  1118.9   793.2  1147.2  807.63
  1165.6  810.53  1178.7  805.72  1184.9  806.46  1227.8  848.75  1300.5  889.45
  1331.7  897.28  1378.5  917.27  1410.7  922.41  1432.8  920.31  1460.1   927.2
#Mann= 6, -1 ,  0
       0    0.05       0     100    0.07       0  220.13    0.05       0
  664.64     0.1       0741.2029   0.045       0 804.403     0.1       0
Bank Sta=741.2029,804.403
XS Rating Curve= 0 ,0
Exp/Cntr(USF)=0,0
Exp/Cntr=0.3,0.1

Type RM Length L Ch R = 1 ,39500   ,512.2,500,479.2
XS GIS Cut Line= 6
1612968.63264735407438.5207363951612849.39949735407400.881690502
1612325.06032293 407084.298662261612157.86019801406983.347748667
1612048.71474701406971.1689672621611915.98404133406996.846081257
#Sta/Elev= 30
       0   733.7    46.6  727.32    80.2  720.33      97  714.75   126.5   715.2
   145.2  707.31   163.9  704.16   252.7  699.97   381.3  699.05   406.9  700.08
418.1123693.1796   425.6  692.19458.4023693.1406   473.9  692.95     505  699.94
   612.5   699.5   640.5  701.57   663.9  712.62   682.7  727.89   710.6  746.53
     748  762.35   785.4  783.24   850.8  802.74   902.2  813.07   915.8  813.85
   970.8  812.07  1112.6  834.68  1132.9  837.02  1149.2  836.54  1177.9  846.24
#Mann= 7, -1 ,  0
       0    0.06       0  145.03    0.08       0  155.03    0.05       0
418.1123   0.045       0458.4023    0.05       0  501.28     0.1       0
 1052.67    0.08       0
Bank Sta=418.1123,458.4023
XS Rating Curve= 0 ,0
Exp/Cntr(USF)=0,0
Exp/Cntr=0.3,0.1