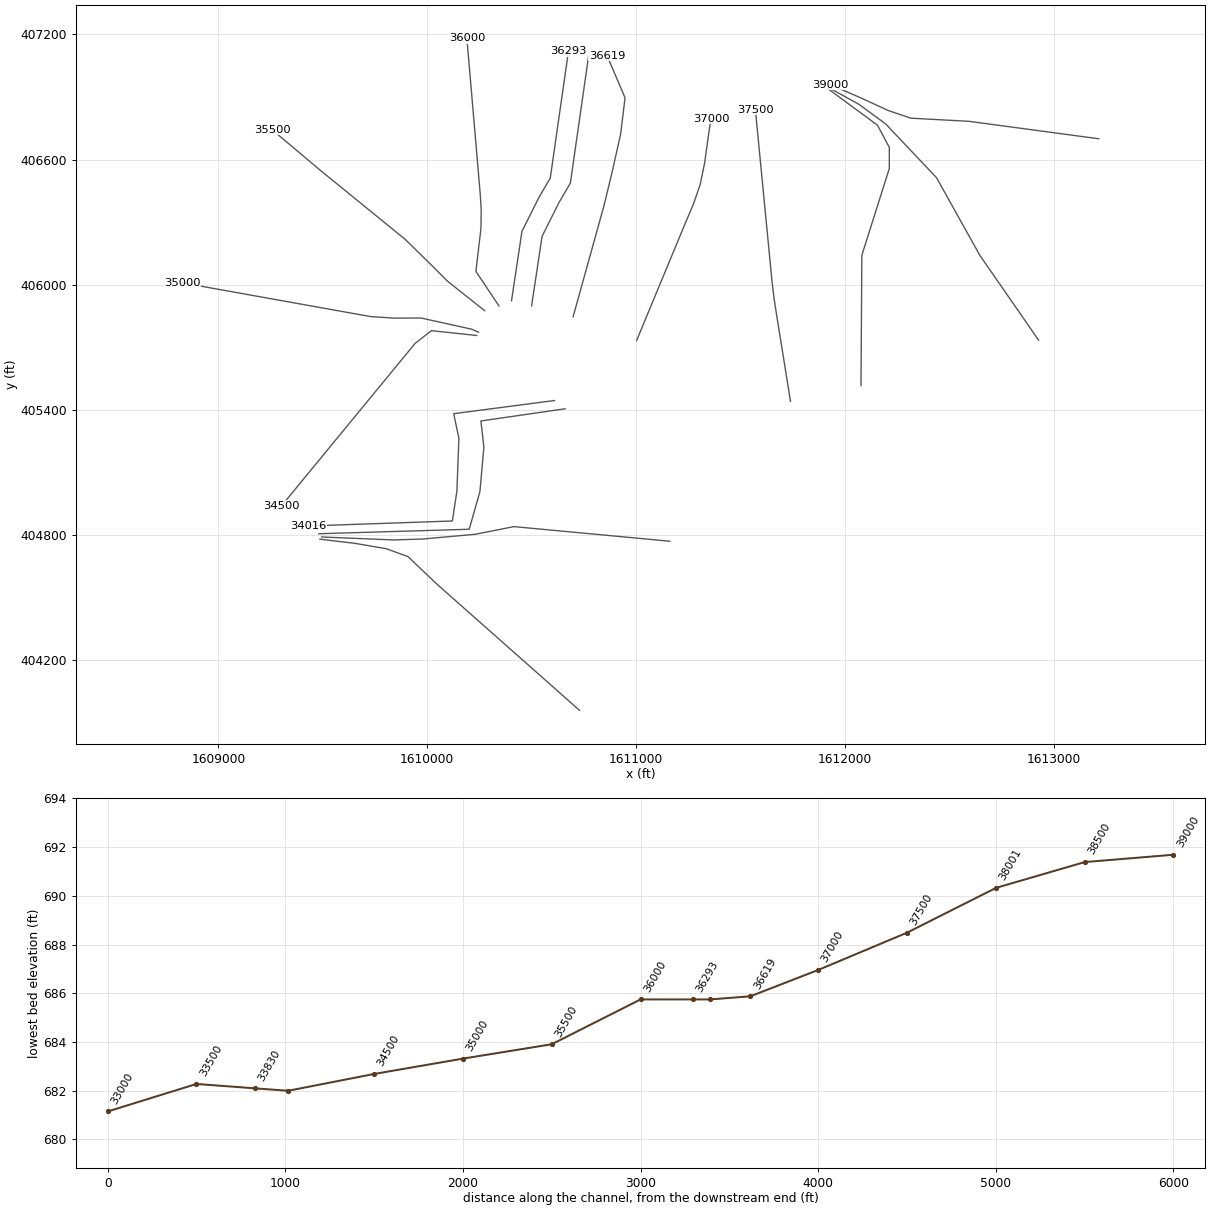
HEC-RAS study LTLFSHNGCK.prj: LTLFSHNGCK

--- LTLFSHNGCK.g01 (geometry) --- (continued)

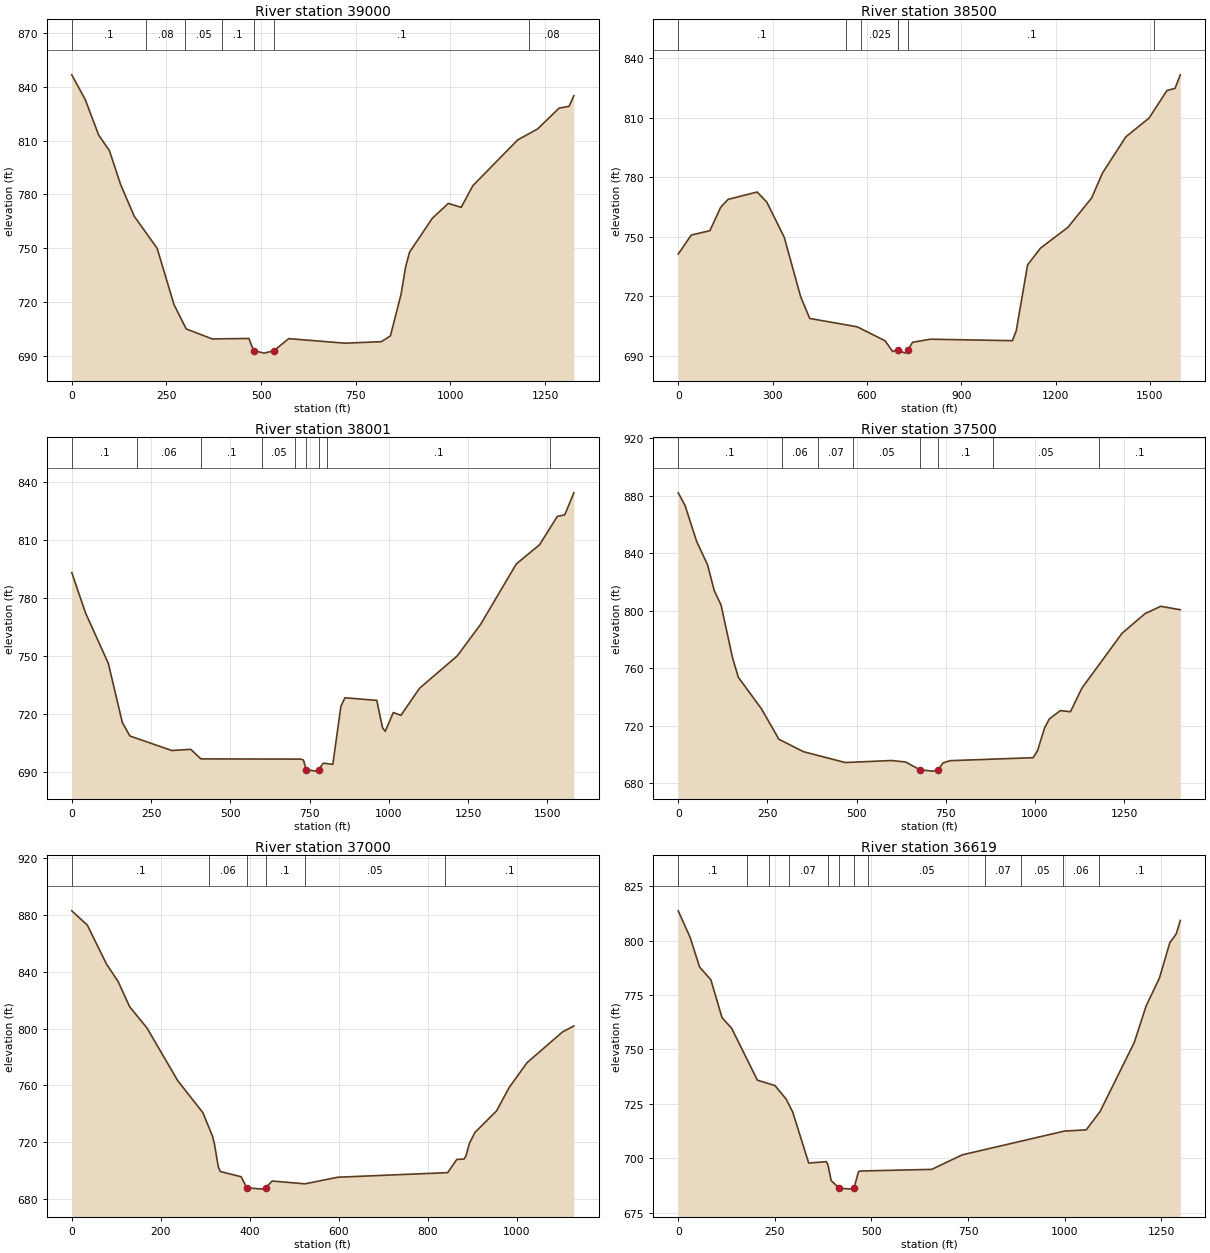
Type RM Length L Ch R = 1 ,39000   ,510.7,499.6,474.6
XS GIS Cut Line= 6
1613215.56608784406699.9926723391612594.59029567406783.484631345
1612315.95601043406798.6263333411612207.73706676406835.344107673
1612073.65334542406897.1671467571611928.45317651406959.845171005
#Sta/Elev= 30
       0  846.56    35.5  832.85      71  813.07    99.5  804.31   128.6  785.72
     165  767.85   225.5  749.98   269.9  718.73   302.2  705.14   370.9   699.6
   467.7  699.84480.1856693.0443     508  691.69533.6556693.0158   572.7  699.75
   721.3  697.22   817.4  698.06   841.4   701.3   869.5  724.48   881.5  739.67
   891.9  747.86   951.9  766.71   994.2  774.99  1028.3  772.83  1059.1   784.9
  1177.4  810.34  1230.2  816.47  1286.9  828.05    1313  829.01  1325.7  834.92
#Mann= 7, -1 ,  0
       0     0.1       0  195.31    0.08       0  299.06    0.05       0
  396.56     0.1       0480.1856   0.045       0533.6556     0.1       0
 1207.57    0.08       0
Bank Sta=480.1856,533.6556
XS Rating Curve= 0 ,0
Exp/Cntr(USF)=0,0
Exp/Cntr=0.3,0.1

Type RM Length L Ch R = 1 ,38500   ,509.1,499.2,479.4
XS GIS Cut Line= 6
1612928.17722693405734.6445374191612646.92549284 406140.70015575
1612439.26252234406513.3099748341612195.61471568406770.927897915
1612067.59200583406864.9592059251611925.42234267406943.741200596
#Sta/Elev= 30
       0  741.32    41.4  750.89   100.7  753.11     135  764.88   158.5  768.89
     251   772.6   281.9  767.46   337.2   749.8   389.3  719.87   418.3  708.87
   569.2  704.66   658.1   697.6   681.8  692.23   698.5  693.12   721.1  691.39
   731.8693.2104   745.3  696.86   802.5  698.41  1062.9  697.66    1075  702.58
  1111.3  735.92  1152.9   744.4  1239.2  754.76  1314.7  769.53  1349.4  782.18
  1423.9  800.44  1497.9  809.91  1554.4  823.76  1580.2  824.85    1597  831.67
#Mann= 7, -1 ,  0
       0     0.1       0  534.01    0.07       0  582.62   0.025       0
  698.06     0.1       0   698.5   0.045       0   731.8     0.1       0
 1514.46    0.08       0
Bank Sta=698.5,731.8
XS Rating Curve= 0 ,0
Exp/Cntr(USF)=0,0
Exp/Cntr=0.3,0.1

Type RM Length L Ch R = 1 ,38001   ,496.6,501.2,509.6
XS GIS Cut Line= 6
1612077.42663184405517.2975311731612081.46008834406141.481322169
1612213.10385393406557.595975503  1612213.064812406658.325432837
1612156.29163159406765.1936574281611915.59165367406942.307476416
#Sta/Elev= 30
       0   793.3    43.3   772.4   115.4  746.17   159.4   715.6   183.4  708.55
   315.4  701.03   375.4  701.62   407.4  696.67   722.6  696.56     731  696.05
   739.4  691.11   768.8  690.33  778.56691.0951   793.5  694.46   823.6  693.86
     849  723.92   861.7  728.35   962.2  727.02   980.4  712.79   988.9  710.96
  1014.3   720.7  1038.5  719.27    1097  733.28    1216  750.07  1289.4  766.33
  1402.4  797.75  1475.7  807.71  1531.8  822.41  1555.2   823.2  1583.9  834.63
#Mann= 9, -1 ,  0
       0     0.1       0  205.33    0.06       0  407.76     0.1       0
  598.73    0.05       0  705.05   0.025       0   739.4   0.045       0
  778.56   0.025       0  805.36     0.1       0 1509.16    0.08       0
Bank Sta=739.4,778.56
XS Rating Curve= 0 ,0
Exp/Cntr(USF)=0,0
Exp/Cntr=0.3,0.1

Type RM Length L Ch R = 1 ,37500   ,504.5,500,483.2
XS GIS Cut Line= 6
1611739.73734659405441.9108709251611707.91949683405640.909488678
1611676.41496667405836.9386241731611661.68336885 405930.71435526
1611651.23391467406017.6400344221611571.72915243406839.192853257
#Sta/Elev= 30
       0  881.88    18.9   873.2    51.8  848.02    82.3  831.83   100.9  814.02
   120.1  803.88   152.5  767.01   168.7  753.63   233.6  731.72   282.2  710.66
   351.1     702   468.5  694.46   597.5  695.86   637.7  694.85   677.9  689.38
   714.1  688.49  728.81689.2943   742.2  694.15   762.3  695.76   995.4  697.83
  1007.4  702.63  1027.2  718.42  1040.6  724.74  1071.7  730.56  1099.9  729.77
    1132  746.19  1244.5  784.27  1308.8  797.91    1353  803.02  1407.9  800.64
#Mann= 8, -1 ,  0
       0     0.1       0  291.53    0.06       0  391.61    0.07       0
  490.07    0.05       0   677.9   0.045       0  728.81     0.1       0
  882.55    0.05       0 1180.67     0.1       0
Bank Sta=677.9,728.81
XS Rating Curve= 0 ,0
Exp/Cntr(USF)=0,0
Exp/Cntr=0.3,0.1

Type RM Length L Ch R = 1 ,37000   ,378.3,381.3,382.7
XS GIS Cut Line= 6
 1611002.6502381405732.4020878371611238.44733867406301.079428166
1611275.22712076406387.318428919 1611307.3425421406480.738189593
1611328.37005909406582.687788844 1611358.3404716406796.536114424
#Sta/Elev= 30
       0  882.97    34.9  872.97    78.1   845.4   104.1  833.26   130.1   815.4
     169  800.47   238.3  763.26   294.6  740.84   316.3  724.19   320.6   718.8
   329.2  702.76   333.6  699.38   380.8  695.66393.0317687.9178   428.8  686.96
435.9316688.0936   450.5  692.67   524.1  690.69   597.7  695.34   844.7  698.57
   865.1  707.85   881.5  708.15   885.6  710.18   893.7   719.3     906   726.9
   954.6  742.08   982.9  758.55    1023  776.01  1102.8   797.7  1128.2  801.86
#Mann= 6, -1 ,  0
       0     0.1       0  308.13    0.06       0393.0317   0.045       0
435.9316     0.1       0  523.12    0.05       0  838.17     0.1       0
Bank Sta=393.0317,435.9316
XS Rating Curve= 0 ,0
Exp/Cntr(USF)=0,0
Exp/Cntr=0.3,0.1

Type RM Length L Ch R = 1 ,36619   ,231.3,228.3,223.5
BEGIN DESCRIPTION:
Structure 10 XS 4
END DESCRIPTION:
XS GIS Cut Line= 6
1610698.87841162405847.2395400411610846.50016361406378.680078209
1610884.86360394406536.6761532881610926.52854686406722.945465789
1610947.48772283 406896.450469331610861.44617267407098.131088345
#Sta/Elev= 30
       0  813.66    30.4  801.65    55.3  787.85    84.4  782.02   113.4  764.59
   138.3  759.72   204.8   735.9   250.4  733.42   279.5  727.16   296.1  721.33
   337.6  697.86   383.3  698.48   387.4  697.04   395.7  689.82   416.5  686.32
   449.7  685.88  455.19686.6186   466.3  693.82   470.5   694.2     656  694.95
   734.5   701.6   999.3  712.54  1055.7  713.09  1091.6  721.54    1180  753.24
  1210.7  769.99  1245.1  782.81  1271.9  799.01  1288.6  803.07  1299.1  809.23
#Mann= 12, -1 ,  0
       0     0.1       0  178.44    0.07       0  235.31     0.1       0
  285.31    0.07       0  386.56     0.1       0   416.5   0.045       0
  455.19     0.1       0  491.56    0.05       0  794.16    0.07       0
  888.02    0.05       0  995.03    0.06       0  1089.8     0.1       0
Bank Sta=416.5,455.19
XS Rating Curve= 0 ,0
Exp/Cntr(USF)=0,0
Exp/Cntr=0.3,0.1

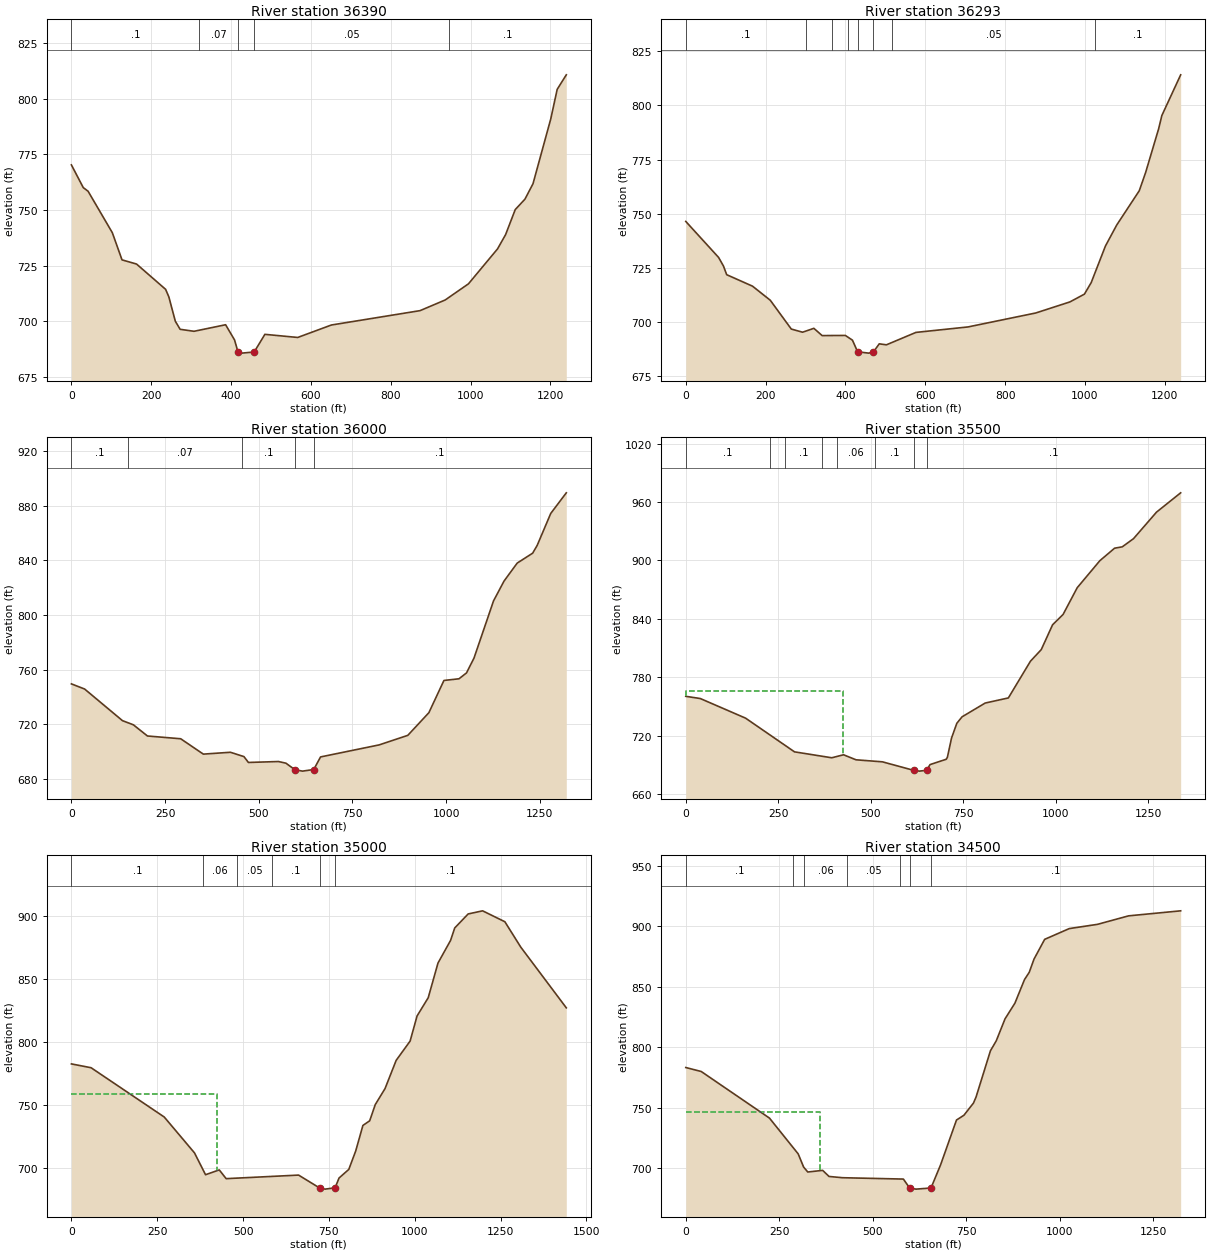
Type RM Length L Ch R = 1 ,36390   ,97.3,97.3,97.5
BEGIN DESCRIPTION:
Structure 10 XS 3
END DESCRIPTION:
XS GIS Cut Line= 5
 1610500.0886589405899.166197721 1610550.1154629406232.239392802
1610630.42164827406392.8517635531610685.71443165406487.639392192
1610772.85752127407095.129425892
#Sta/Elev= 30
       0  770.23    29.7  760.03    41.8   758.4   102.5   739.8   126.8   727.6
   163.2  725.73     236  714.38   244.1     711   260.3  700.08   272.4  696.44
   307.2  695.55   386.3  698.49   408.7  691.67   417.6   686.1   426.6  685.75
   457.9  686.25   484.7  694.18     567  692.78   651.3  698.37   873.5  704.82
   936.5  709.61   994.7  716.85  1067.5  732.52  1087.7  738.92  1111.9  750.17
  1136.2  754.85  1156.4  761.78  1200.8  790.81    1217  804.14  1239.8  810.65
#Mann= 5, -1 ,  0
       0     0.1       0     320    0.07       0   417.6   0.045       0
   457.9    0.05       0  946.12     0.1       0
Bank Sta=417.6,457.9
XS Rating Curve= 0 ,0
Exp/Cntr(USF)=0,0
Exp/Cntr=0.3,0.1

Type RM Length L Ch R = 1 ,36293   ,279.7,293.1,307.6
BEGIN DESCRIPTION:
Structure 10 XS 2
END DESCRIPTION:
XS GIS Cut Line= 5
1610403.83514806405923.2138491251610453.86195207406256.287044206
1610534.16813744406416.8994149561610589.46092082406511.687043596
1610676.60401044407119.177077295
#Sta/Elev= 30
       0   746.5    82.2   729.9    94.4  725.94   102.5  721.93   167.2  716.64
   211.7  710.14   264.3  696.86   292.6   695.4   320.9  697.19   341.6  693.84
   399.7  693.91   417.6  691.72  430.43686.3746   458.1  685.75   469.9  686.26
   484.7  690.04   502.6  689.58   576.6  695.31     707  697.83   876.6  704.26
   962.4  709.38   998.7  712.97  1015.6  718.26  1051.3  735.15  1079.6  744.85
  1136.1  760.67  1151.9  769.01  1184.6  789.24  1192.7  795.38  1239.8  814.14
#Mann= 8, -1 ,  0
       0     0.1       0     300    0.06       0  366.81    0.07       0
  406.81     0.1       0  430.43   0.045       0   469.9     0.1       0
  516.38    0.05       0 1026.12     0.1       0
Bank Sta=430.43,469.9
XS Rating Curve= 0 ,0
Exp/Cntr(USF)=0,0
Exp/Cntr=0.3,0.1

Type RM Length L Ch R = 1 ,36000   ,481.2,500,513.9
BEGIN DESCRIPTION:
Structure 10 XS 1
END DESCRIPTION:
XS GIS Cut Line= 6
1610343.72963992405899.1960455921610233.36667167406064.242959589
1610257.41091493406269.8924826681610258.77639775406359.344075426
1610254.16321801406434.223846927  1610190.080669407181.872942179
#Sta/Elev= 30
       0  749.56    35.3  745.78   136.3  722.65   165.2  719.65   202.9  711.45
   291.6  709.42     352  698.19   424.3  699.54   460.3  696.39   472.3  692.09
   552.4  692.77   572.4  691.56596.4736686.7499   616.6  685.75646.6435686.9354
   664.8  696.13   821.3  704.94   897.6  711.91   953.8  728.48     994  752.06
  1034.1  753.28  1054.2  757.57  1074.3  768.48  1126.4   810.3  1154.4  824.76
  1189.5   837.9  1230.8  845.17  1242.9   850.9    1279  874.21  1320.5  889.29
#Mann= 5, -1 ,  0
       0     0.1       0     150    0.07       0  455.62     0.1       0
596.4736   0.045       0646.6435     0.1       0
Bank Sta=596.4736,646.6435
XS Rating Curve= 0 ,0
Exp/Cntr(USF)=0,0
Exp/Cntr=0.3,0.1

Type RM Length L Ch R = 1 ,35500   ,489.7,500,512.6
XS GIS Cut Line= 6
1610275.34854309405876.093729585  1610096.604478406018.037999511
1610025.96682401 406089.113316671609895.28303026406217.436550841
1609485.76777317406550.9240728321609258.34926476406742.431563839
#Sta/Elev= 30
       0  760.66    39.3  758.37   161.5  738.27   293.8  703.68   394.4  697.61
   426.2  700.68   459.9  695.53   531.2  693.45615.5723  684.73   630.7  683.91
650.3422684.7033     660  690.63   703.7  696.09   706.8  698.17     718  717.86
   732.2  732.93   746.4  739.62   808.9  753.76   871.5     759   931.2   796.7
   960.4  808.57   990.9  834.01  1019.3  844.62  1057.5  872.07  1118.7  899.81
  1158.5  912.62  1179.2  914.01  1209.6  922.39  1271.8  949.63    1337  969.42
#Mann= 8, -1 ,  0
       0     0.1       0  228.25    0.05       0  268.25     0.1       0
  368.46    0.07       0  408.46    0.06       0  511.61     0.1       0
615.5723   0.045       0650.3422     0.1       0
#XS Ineff= 2 , 0
          425.74  765.86
Permanent Ineff=
       F       F
Bank Sta=615.5723,650.3422
XS Rating Curve= 0 ,0
Exp/Cntr(USF)=0,0
Exp/Cntr=0.3,0.1

Type RM Length L Ch R = 1 ,35000   ,478,500,529.2
XS GIS Cut Line= 6
1610245.96575495405773.1200995621610212.57537468405787.588985339
1609971.05814117405841.0291671751609843.76672909405840.457646012
1609730.22692992405847.7128808351608827.92460068406009.511441752
#Sta/Elev= 30
       0  782.55    57.3  779.52   270.4  740.47   358.5  712.05   390.7  694.75
   430.7  698.54   450.8  691.62   661.7  694.44722.7706684.2854     739  683.32
768.1306684.3852   779.6  692.12     808  698.93   828.2  713.57   849.1  733.78
   868.9  737.48   885.1  750.29   913.6  763.01     946  785.35   986.6  800.62
  1006.9  820.54  1039.4     835  1067.8  862.46  1104.4  880.36  1116.6  890.28
  1155.7  901.38  1197.8  903.86  1262.7   895.2  1309.1  875.04  1441.6     827
#Mann= 6, -1 ,  0
       0     0.1       0  383.75    0.06       0  481.04    0.05       0
  584.81     0.1       0722.7706   0.045       0768.1306     0.1       0
#XS Ineff= 2 , 0
          423.29  758.62
Permanent Ineff=
       F       F
Bank Sta=722.7706,768.1306
XS Rating Curve= 0 ,0
Exp/Cntr(USF)=0,0
Exp/Cntr=0.3,0.1

Type RM Length L Ch R = 1 ,34500   ,471.7,483.8,502.6
BEGIN DESCRIPTION:
Structure 9 XS 4
END DESCRIPTION:
XS GIS Cut Line= 6
1610237.14848825405757.2901614161610020.20436834405780.430863172
1609942.05983959405719.2616941781609826.97214326405579.238680258
1609779.34986317 405521.297851251609302.87739092 404941.59100543
#Sta/Elev= 30
       0   783.3    41.3  780.02   223.9  741.46   300.8  711.84   315.3  700.93
   326.4  696.86   366.2  698.21   383.3  693.17   419.3  692.13   582.2  691.01
599.2245683.5153   616.3  682.69656.1245683.6395   681.7  702.74   724.3  739.86
   744.2  743.81   769.8  753.94   776.6  758.87   815.2   797.2   830.7  805.39
   854.2  823.58   880.6  836.54   906.3  856.08   918.9  862.05   931.7  872.99
   960.2  889.35    1026  898.25  1101.6  901.77  1184.7  908.79  1324.1  912.95
#Mann= 7, -1 ,  0
       0     0.1       0  288.17    0.07       0  317.41    0.06       0
  431.16    0.05       0  573.66     0.1       0599.2245   0.045       0
656.1245     0.1       0
#XS Ineff= 2 , 0
          359.31  746.21
Permanent Ineff=
       F       F
Bank Sta=599.2245,656.1245
XS Rating Curve= 0 ,0
Exp/Cntr(USF)=0,0
Exp/Cntr=0.3,0.1

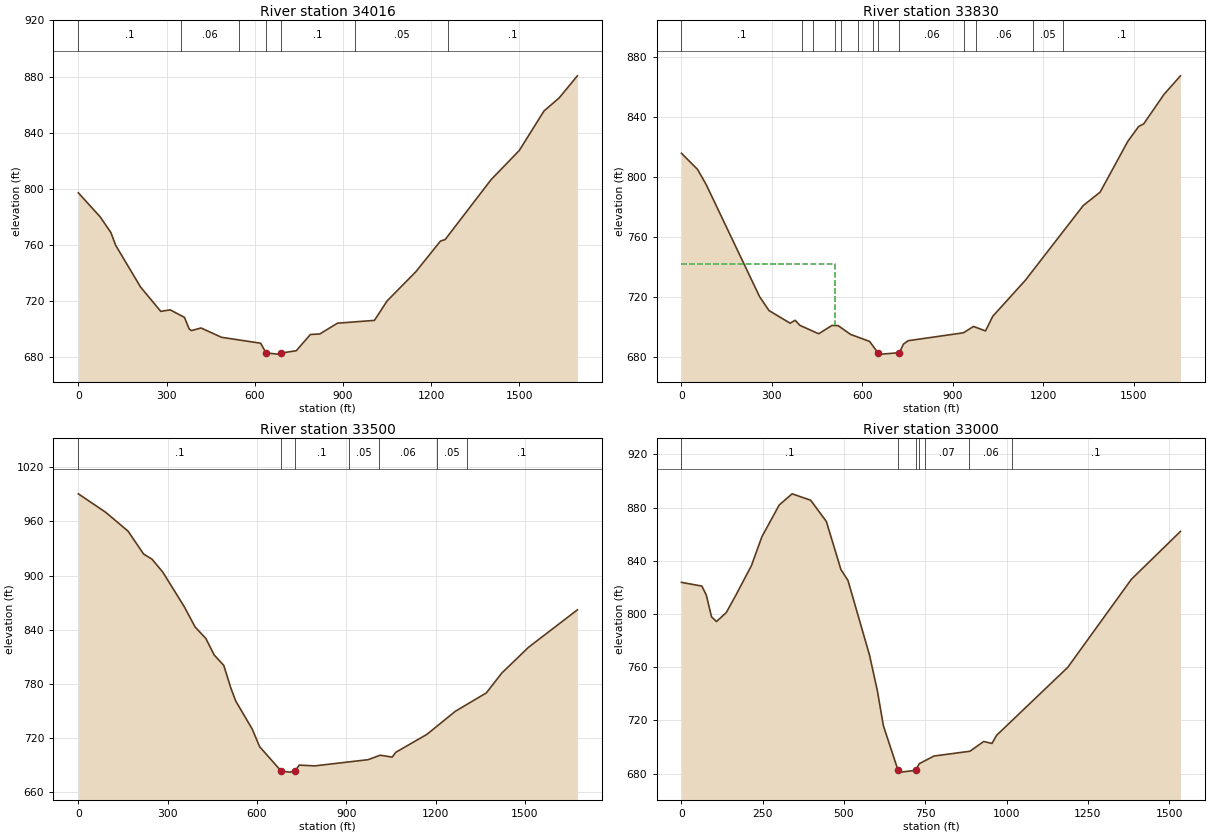
Type RM Length L Ch R = 1 ,34016   ,171.7,186.7,186.4
BEGIN DESCRIPTION:
Structure 9 XS 3
END DESCRIPTION:
XS GIS Cut Line= 6
1610609.95501455405445.7200004771610126.94481484405382.603634833
1610151.82656736405265.3039443921610142.36262033405011.259301011
1610120.53656969 404868.440247261609430.69208237404844.573652451
#Sta/Elev= 30
       0  797.05    74.1  779.93   110.8  768.67   126.9  759.62   211.6  729.87
   280.2  712.52   312.5  713.57   360.9  708.22     377  699.95   384.5   698.8
   417.4  700.65   487.1     694   620.1  689.79  638.36682.9019   677.2     682
   689.2  682.74   741.3  684.43   789.4     696   821.4  696.38   881.5  704.08
  1007.3  706.07  1050.1  719.91  1147.8  740.71  1231.8  762.63  1247.8  763.73
  1403.9  806.41    1500  827.27    1584  855.42  1635.4   864.7  1697.6  880.51
#Mann= 7, -1 ,  0
       0     0.1       0     350    0.06       0  547.12    0.05       0
  638.36   0.045       0   689.2     0.1       0  942.68    0.05       0
 1257.26     0.1       0
Bank Sta=638.36,689.2
XS Rating Curve= 0 ,0
Exp/Cntr(USF)=0,0
Exp/Cntr=0.3,0.1

Type RM Length L Ch R = 1 ,33830   ,368.8,329.6,281.7
BEGIN DESCRIPTION:
Structure 9 XS 2
END DESCRIPTION:
XS GIS Cut Line= 6
1610660.91818078405406.1323668931610257.29262006405347.755382681
1610271.51076435405222.1617747341610252.55323862405008.889610295
1610201.12086987404828.852613676 1609481.6552486404807.355709583
#Sta/Elev= 30
       0  815.76    53.4  805.04    81.6  795.13   259.5  720.25   290.6  711.08
   360.5  702.69   377.1  704.62   392.8  701.28   455.3  695.65   499.6   701.2
   519.8  701.08     561  695.24   624.2  690.57   652.3  682.89   664.2   682.1
   723.2  683.06   736.6  688.78   752.8  691.05   935.9  696.31   968.9  700.53
  1008.9  697.54    1033   707.3    1141  731.25  1333.3  781.02  1389.1   789.9
  1481.1  823.75  1517.1  833.62  1533.8  835.37  1601.2  854.99  1655.7  867.32
#Mann= 13, -1 ,  0
       0     0.1       0     400    0.06       0  437.83    0.07       0
  507.83    0.06       0  527.83    0.05       0  584.22    0.07       0
  634.22    0.06       0   652.3   0.045       0   723.2    0.06       0
   935.9    0.05       0   975.9    0.06       0  1165.9    0.05       0
  1265.9     0.1       0
#XS Ineff= 2 , 0
          508.55  741.81
Permanent Ineff=
       F       F
Bank Sta=652.3,723.2
XS Rating Curve= 0 ,0
Exp/Cntr(USF)=0,0
Exp/Cntr=0.3,0.1

Type RM Length L Ch R = 1 ,33500   ,513.7,500,483
BEGIN DESCRIPTION:
Structure 9 XS
END DESCRIPTION:
XS GIS Cut Line= 6
  1611162.385811404771.4207420951610415.27083543404841.461284429
 1610230.5549975404804.7526964251609976.21659543404781.771115094
1609838.22868243404777.6330000011609494.82713826404791.752066255
#Sta/Elev= 30
       0  990.56    91.3  970.23     167  949.19   219.2  923.84   247.4  918.16
   283.5  903.88   355.8  865.48     392  843.12   428.1  830.35   456.3  811.98
   488.4  800.52   512.5  775.08   528.8  760.86   583.5  730.29   608.9  710.41
   681.2  683.46   709.4  682.28   728.3  683.53   741.5  690.06   794.3  689.21
   973.4  696.09  1013.7  701.01    1054  698.94  1066.1  704.25  1170.3  724.04
  1266.3  749.72  1370.4  770.08    1422  791.97    1512   820.6    1676  862.02
#Mann= 7, -1 ,  0
       0     0.1       0   681.2   0.045       0   728.3     0.1       0
  909.36    0.05       0 1008.73    0.06       0 1204.21    0.05       0
 1304.21     0.1       0
Bank Sta=681.2,728.3
XS Rating Curve= 0 ,0
Exp/Cntr(USF)=0,0
Exp/Cntr=0.3,0.1

Type RM Length L Ch R = 1 ,33000   ,511.7,500,491.7
XS GIS Cut Line= 6
  1610729.429984 403961.168425591610046.04716443404566.443461761
1609907.84337258 404697.91662401  1609804.042071404735.705590427
1609654.07124235404761.3157754241609486.28056742404781.270131841
#Sta/Elev= 30
       0  823.79    62.8  821.01    76.5  814.21    92.5  797.91   107.7  794.34
   137.9  801.09   167.3  814.11   215.4  836.47   247.4  858.06   300.8  881.98
   340.5  890.35   397.5  885.54   445.8  869.57   490.7  833.36   512.2  825.32
   578.6  769.08   602.8  742.23   621.3     716   666.4  682.51   675.2  681.15
   720.3  682.47   731.6  687.49   776.9  693.25   887.4  696.85   929.9  704.18
   955.4  702.73   969.5  708.82  1188.5  759.92  1384.3  826.13  1535.2   862.1
#Mann= 7, -1 ,  0
       0     0.1       0   666.4   0.045       0   720.3     0.1       0
  730.39    0.05       0  750.39    0.07       0  885.39    0.06       0
 1016.69     0.1       0
Bank Sta=666.4,720.3
XS Rating Curve= 0 ,0
Exp/Cntr(USF)=0,0
Exp/Cntr=0.3,0.1