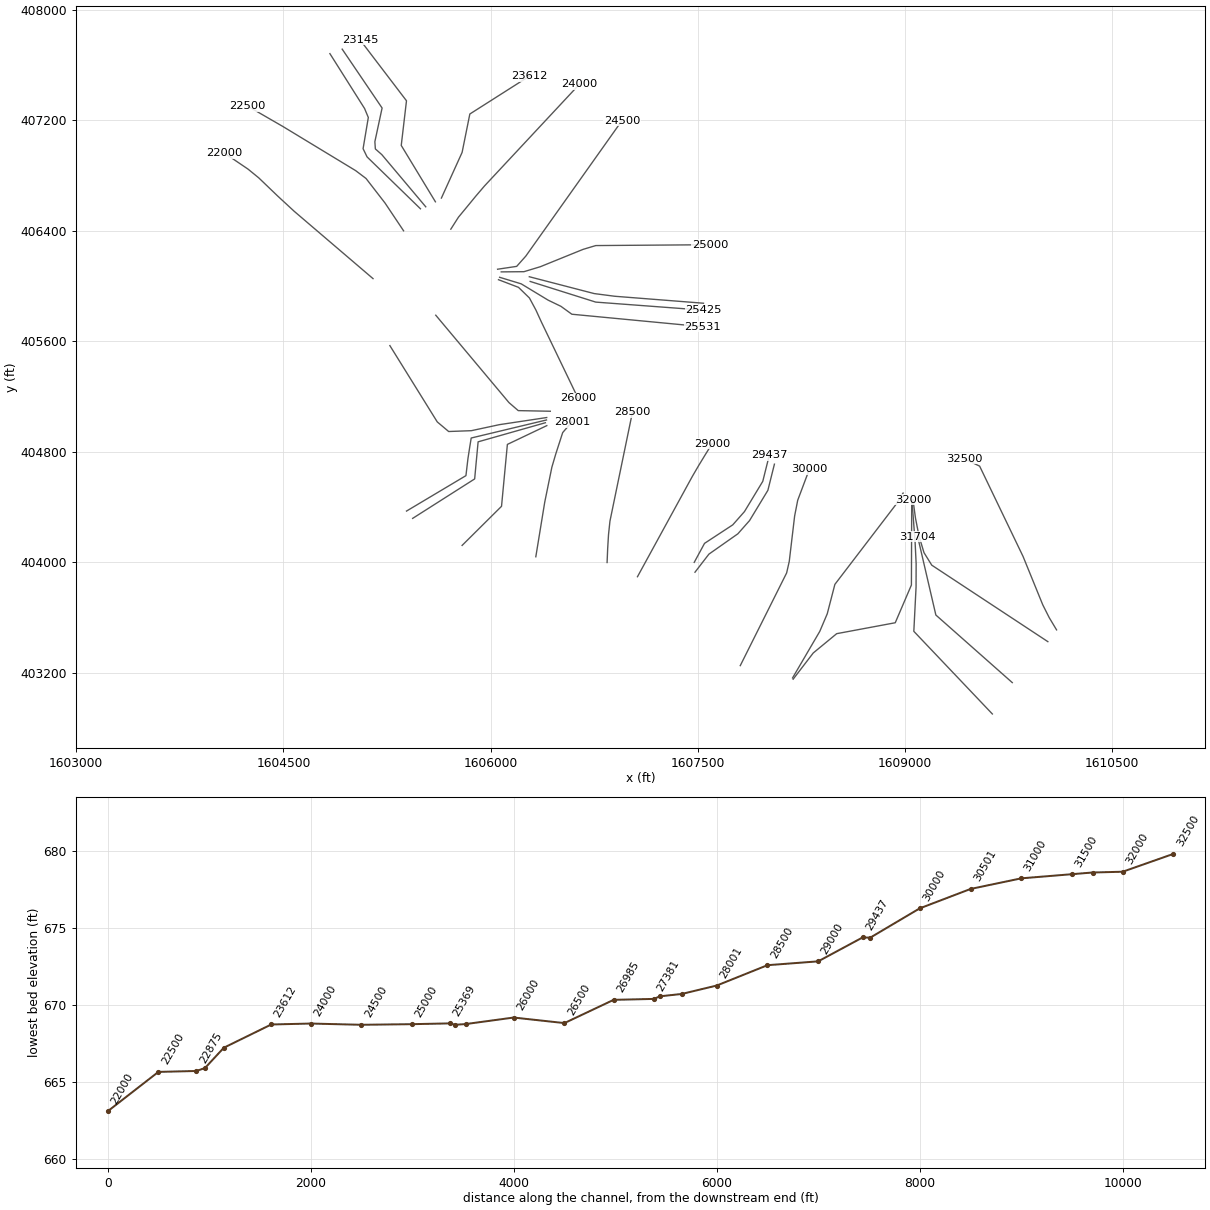
HEC-RAS study LTLFSHNGCK.prj: LTLFSHNGCK

--- LTLFSHNGCK.g01 (geometry) --- (continued)

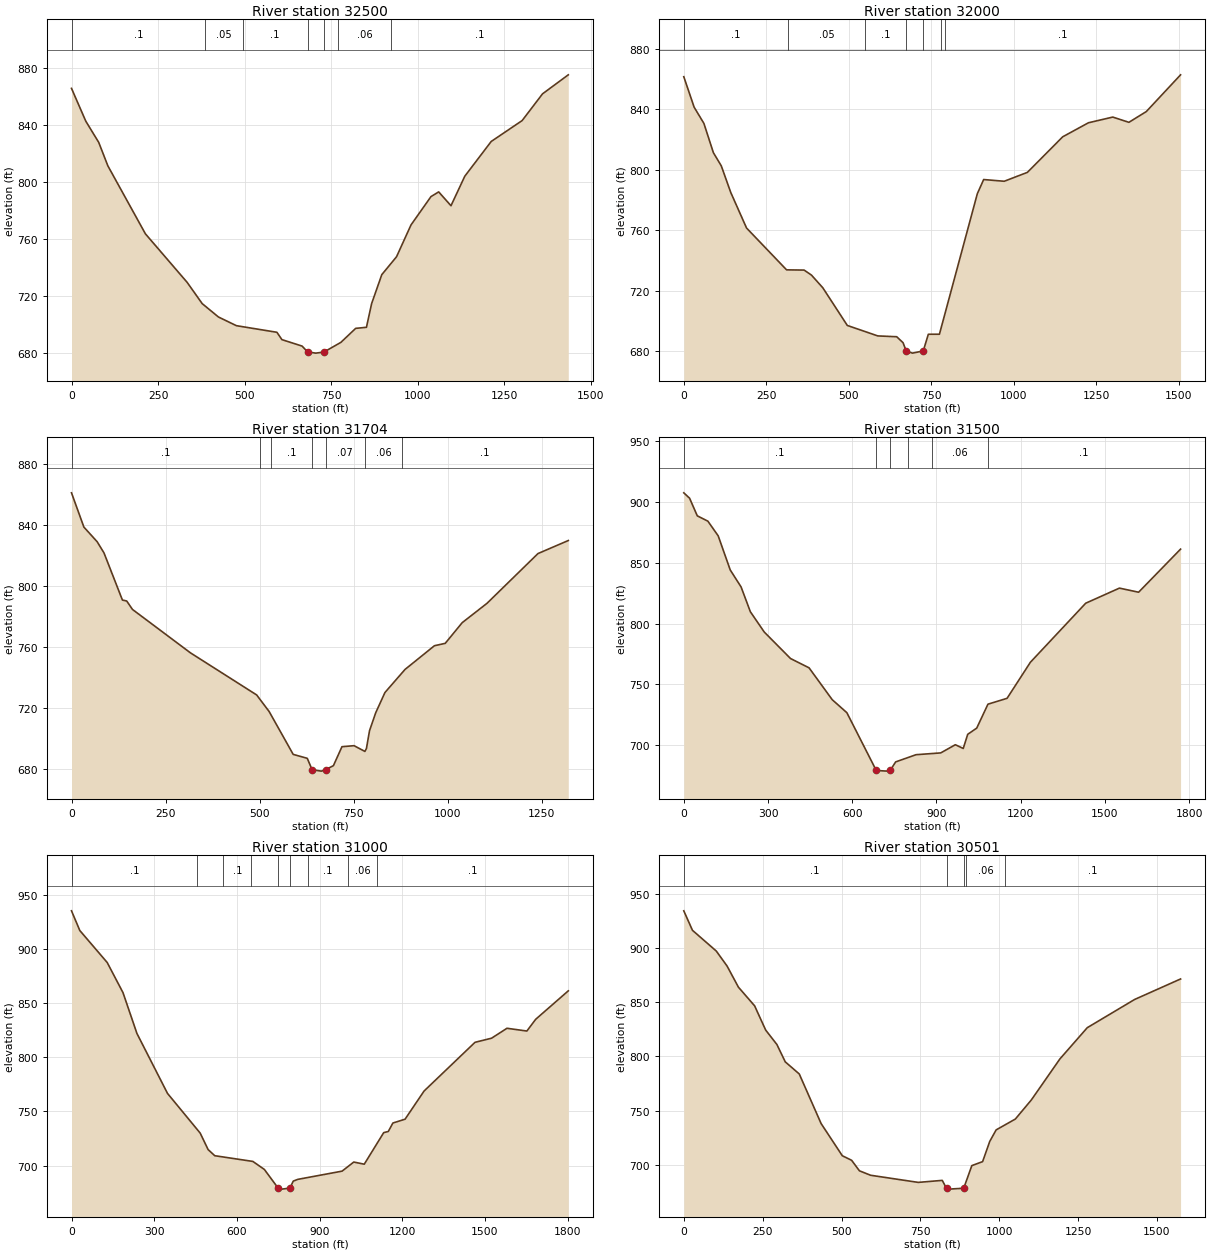
Type RM Length L Ch R = 1 ,32500   ,484.8,500,511.2
XS GIS Cut Line= 6
1610098.03000009403509.1122430861610044.48122267403598.477549925
1609998.38124926403689.9379969241609855.54951392 404040.49897559
1609541.07310876404694.6115125121609429.78166467404747.917836338
#Sta/Elev= 30
       0  865.47    41.3  842.44    78.6  827.59     105  811.13   213.4  763.47
   334.1  729.38   377.3  714.55   424.2  705.17     476  699.07   593.1  694.43
   607.5  689.29   665.8  684.75  681.66680.6795   705.1  679.82   728.7  680.55
   777.8  687.37   820.5  697.18   851.6  697.93   866.6  714.58   895.9  734.84
   938.5   747.4   980.3  769.72    1038  789.59  1060.2  792.87  1095.7  783.17
  1135.6  803.88  1211.8  828.22  1301.2  842.89    1360  861.62  1434.4  874.96
#Mann= 7, -1 ,  0
       0     0.1       0  386.41    0.05       0  493.75     0.1       0
  681.66   0.045       0   728.7     0.1       0  770.22    0.06       0
  922.72     0.1       0
Bank Sta=681.66,728.7
XS Rating Curve= 0 ,0
Exp/Cntr(USF)=0,0
Exp/Cntr=0.3,0.1

Type RM Length L Ch R = 1 ,32000   ,299.7,296.4,294.6
XS GIS Cut Line= 6
1610035.01798701403423.8811143341609194.41205667403977.692342669
1609138.19596176404068.2679489261609102.05856684404188.675188422
1609076.49661009404318.9406759291609058.47236793404451.546381846
#Sta/Elev= 30
       0  861.46    31.4   841.3      61  830.56    89.7  811.22   113.6  802.53
   142.4  784.88   190.2  761.39   311.5  733.73   364.7  733.58     387  730.24
   421.3  721.88   495.6  696.96   587.9  690.04   645.3   689.5   664.5  685.53
   674.1  680.07   693.2  678.66  725.76680.1099   741.1  691.13   774.7  691.16
   889.6  784.11   908.8  793.46   971.1  792.32  1041.3   798.2  1148.3  821.72
  1226.3     831    1300  834.77  1348.9   831.3  1401.6   838.4  1505.5  862.71
#Mann= 7, -1 ,  0
       0     0.1       0  317.27    0.05       0  547.89     0.1       0
   674.1   0.045       0  725.76     0.1       0  780.39    0.06       0
  790.39     0.1       0
Bank Sta=674.1,725.76
XS Rating Curve= 0 ,0
Exp/Cntr(USF)=0,0
Exp/Cntr=0.3,0.1

Type RM Length L Ch R = 1 ,31704   ,204.8,203.6,201.1
XS GIS Cut Line= 3
1609777.43025007403127.3551817981609224.10746788 403616.69631465
1609092.58963315404183.052395772
#Sta/Elev= 30
       0  860.83    32.9  838.41    68.2   828.8    86.3  821.51   135.3  790.62
   146.7     790     162  784.48   316.3  756.02     492  728.49   525.1  717.67
   589.1  689.57   626.5  686.99   639.4  679.52   663.9  678.61  675.14679.5297
     696   682.2   718.7  694.61   750.8  695.27   779.6  691.52   783.7  693.42
   791.9  705.05   808.3  716.78   832.9  730.08   886.3   745.2   964.4  760.71
   993.1  762.28  1038.3  775.84    1104  788.46  1239.5  821.05  1320.1   829.6
#Mann= 7, -1 ,  0
       0     0.1       0     500    0.06       0     530     0.1       0
   639.4   0.045       0  675.14    0.07       0  778.66    0.06       0
  878.66     0.1       0
Bank Sta=639.4,675.14
XS Rating Curve= 0 ,0
Exp/Cntr(USF)=0,0
Exp/Cntr=0.3,0.1

Type RM Length L Ch R = 1 ,31500   ,532.7,500,432.1
XS GIS Cut Line= 6
1609633.16708468402900.2896418421609064.61638451403498.640151173
 1609080.7859716403818.4413488361609081.38308325403988.642780095
 1609073.6517995404148.8622759281609051.37067609404441.593317762
#Sta/Elev= 30
       0  907.61    20.7  903.16    48.1  888.67    85.8  884.28   122.6  872.19
   165.5  844.11   204.1  830.14   237.1  809.75   286.7     793   380.3  771.19
   446.3  763.54   528.9  737.29     581   726.6   685.7  679.03   725.3   678.5
  735.12679.0303   754.8  686.09   827.3  692.02   915.4   693.5   967.4  700.24
   995.6  697.15  1011.5  708.81  1043.6  713.91  1083.6  733.61  1151.7  738.44
  1234.7   768.1  1431.9  816.74    1552  829.16  1620.3  825.78  1769.8  861.26
#Mann= 6, -1 ,  0
       0     0.1       0   685.7   0.045       0  735.12     0.1       0
  800.39    0.08       0  885.41    0.06       0 1083.02     0.1       0
Bank Sta=685.7,735.12
XS Rating Curve= 0 ,0
Exp/Cntr(USF)=0,0
Exp/Cntr=0.3,0.1

Type RM Length L Ch R = 1 ,31000   ,477.4,499.2,513.1
XS GIS Cut Line= 6
1608190.89733142403152.195962176 1608336.3071456403341.814349338
1608506.15195026403481.6828360111608930.09664042403560.722704172
1609047.15611759403833.9623151721609049.26897426404442.563132092
#Sta/Elev= 30
       0  935.42    30.1  917.24   129.5  887.66   186.8  859.81   237.4  822.07
   348.3  766.68   466.8  730.03   495.7  714.75   519.7  709.12     658  703.83
   699.7  696.41  749.78679.1242   763.2  678.23   792.3  679.18   804.5  685.62
   820.8  687.24   981.6  694.85  1024.1  703.26  1062.1  701.27  1132.7  730.45
  1149.3   731.5  1165.9  739.31  1210.1  742.85  1279.1  768.89  1463.9  813.91
  1523.9   817.7  1579.9  826.88    1652  824.33  1684.1  835.19  1802.3  861.47
#Mann= 9, -1 ,  0
       0     0.1       0  456.76    0.06       0   550.7     0.1       0
  651.95    0.06       0  749.78   0.045       0   792.3   0.025       0
  856.95     0.1       0 1001.95    0.06       0 1109.56     0.1       0
Bank Sta=749.78,792.3
XS Rating Curve= 0 ,0
Exp/Cntr(USF)=0,0
Exp/Cntr=0.3,0.1

Type RM Length L Ch R = 1 ,30501   ,478.8,500.7,501.9
XS GIS Cut Line= 6
1608186.62863918403161.2051305031608383.86348093403498.655899167
1608437.85353042403625.8318259271608493.01483743403838.612240255
1608933.88403443 404415.178016261608987.16608009404499.665052012
#Sta/Elev= 30
       0  934.47    27.5  916.49     103  897.34   137.1  883.56   173.2  863.99
   224.6  846.74   259.6  824.38   295.1  811.09   321.7  795.04   366.1  783.84
   435.4  738.03   502.5  708.37     532  704.17   556.8  694.45   592.3  690.34
   743.3  683.76   819.3  685.61   833.1  678.13   839.2  677.54   887.4  678.35
   913.1  699.25   947.3  702.93   969.9  721.58   990.2  732.24    1051  742.23
  1101.7  759.86  1192.4  797.78    1279  826.57    1429  852.61  1574.8  871.56
#Mann= 5, -1 ,  0
       0     0.1       0   833.1   0.045       0   887.4     0.1       0
  894.13    0.06       0 1019.14     0.1       0
Bank Sta=833.1,887.4
XS Rating Curve= 0 ,0
Exp/Cntr(USF)=0,0
Exp/Cntr=0.3,0.1

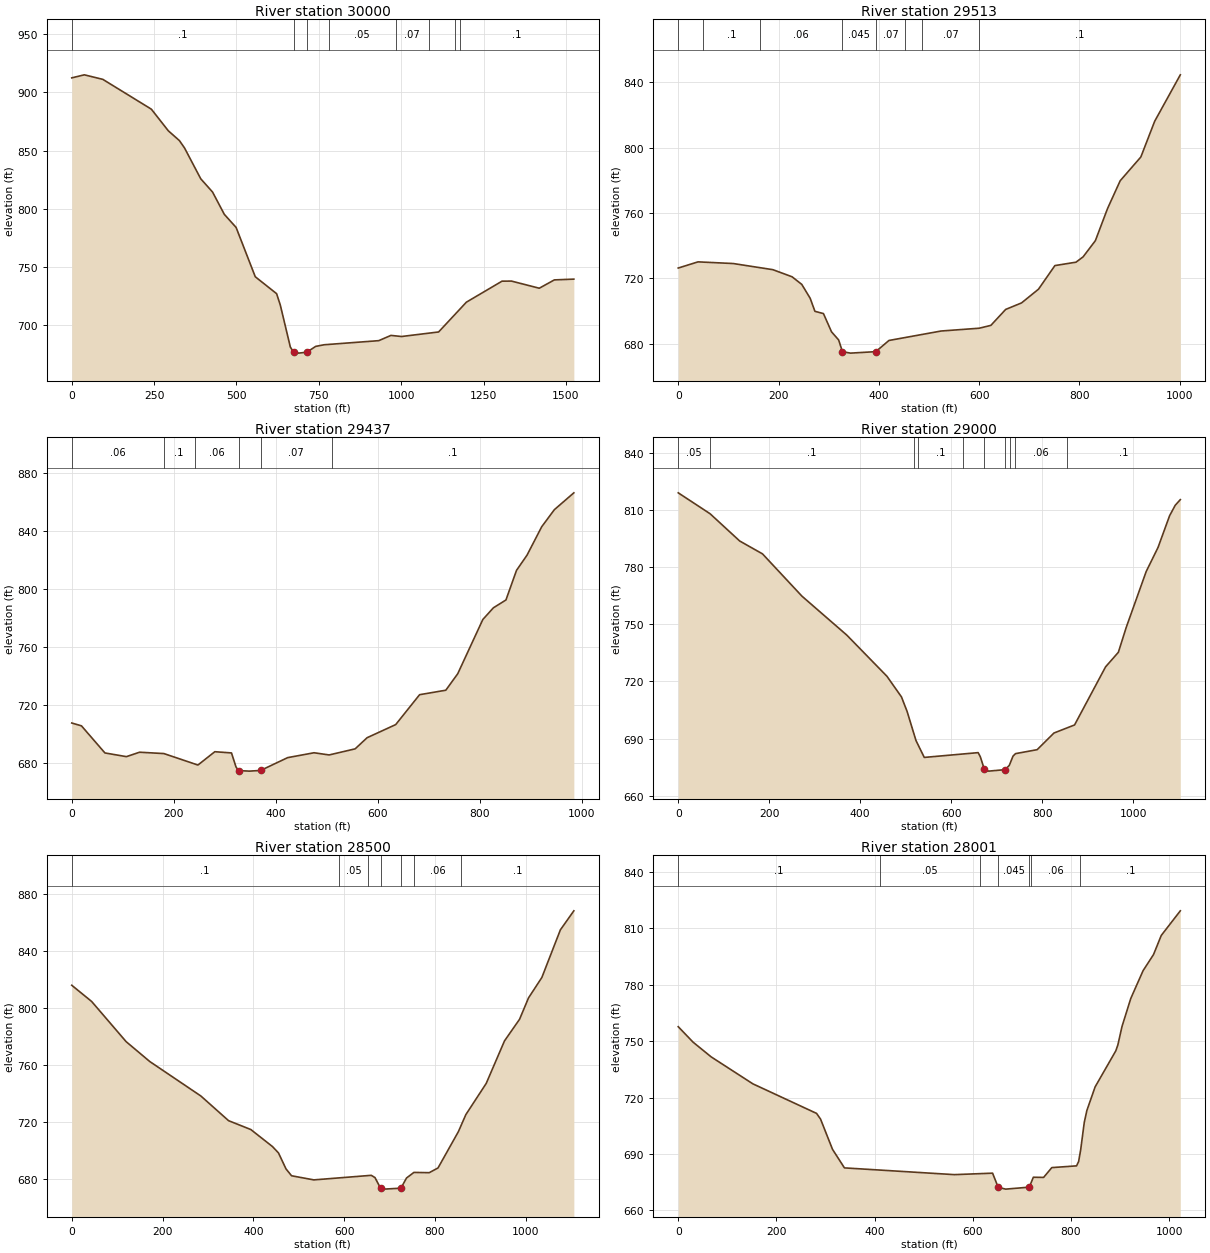
Type RM Length L Ch R = 1 ,30000   ,503.2,486.7,474
XS GIS Cut Line= 6
1607808.07526243403250.3407790061608143.77045718403921.455250427
1608162.66871335404004.7119736671608201.66141751404333.691302583
1608223.83361726404447.322965086 1608308.6615316404673.012802422
#Sta/Elev= 30
       0  912.37    38.2  914.98    94.3  911.09   241.6  885.52   293.1  866.97
   326.8  858.56   342.3  852.26   391.5  825.82   427.3  814.48   463.1  795.31
   498.9  784.07     557   741.8   621.8  727.27     633  717.55   663.5  681.52
   673.3  677.12   688.7  676.28   713.6  677.08   740.4  682.06   765.9  683.45
     932  686.98   968.9  691.48  1000.9  690.53  1113.6  694.43  1197.9  719.98
  1306.1     738  1334.8  738.07  1419.1  731.95    1465  739.09  1524.1  739.75
#Mann= 8, -1 ,  0
       0     0.1       0   673.3   0.045       0   713.6     0.1       0
  780.39    0.05       0  982.97    0.07       0 1084.47     0.1       0
 1164.47    0.06       0 1177.07     0.1       0
Bank Sta=673.3,713.6
XS Rating Curve= 0 ,0
Exp/Cntr(USF)=0,0
Exp/Cntr=0.3,0.1

Type RM Length L Ch R = 1 ,29513   ,78,76.2,75.4
BEGIN DESCRIPTION:
Structure 8 XS 3
END DESCRIPTION:
XS GIS Cut Line= 6
1607480.11021813403926.6126976811607581.07908365404057.576624492
1607790.65166772404204.7233324571607875.37249958404300.591642192
1608008.05087082404519.771321817 1608055.2636712404708.863674667
#Sta/Elev= 30
       0  726.38    39.5  730.15   109.7  729.13   188.7  725.38     227  721.04
   246.4  716.38   263.2  707.86   272.6  699.93   289.6  698.55   305.7   687.4
   319.9  682.44327.4987675.2794   343.5  674.38     394  675.28   420.2  682.11
   524.2  687.89   600.2   689.6   623.5  691.34     653  701.08   684.7  705.07
   718.5  713.46   751.2  727.88   793.3  729.96   807.4   733.2   831.9   743.1
   856.2  762.76   881.4  779.72   922.6  794.25   950.2  816.08  1001.3  844.45
#Mann= 8, -1 ,  0
       0    0.06       0      50     0.1       0  162.21    0.06       0
327.4987   0.045       0     394    0.07       0  452.13    0.05       0
  486.27    0.07       0   600.2     0.1       0
Bank Sta=327.4987,394
XS Rating Curve= 0 ,0
Exp/Cntr(USF)=0,0
Exp/Cntr=0.3,0.1

Type RM Length L Ch R = 1 ,29437   ,421.2,437.1,444.2
BEGIN DESCRIPTION:
Structure 8 XS 2
END DESCRIPTION:
XS GIS Cut Line= 6
1607474.64696638403997.9482337721607549.28593506404135.494634794
1607753.59253977404269.4763943371607838.31337162404365.344704072
1607970.99174287404584.5243836981608018.20454324404773.616736548
#Sta/Elev= 30
       0  707.55      19   705.6      65  686.92   107.1  684.37   132.9  687.42
   180.6  686.49   247.3  678.59   280.4  687.77   313.1  686.93     322  677.22
   326.9  674.76   348.1  674.39   370.2  674.84   423.1  683.68   474.9  687.05
   504.5  685.54   555.5  689.74   578.9  697.41     635  706.46   681.8  727.06
   733.2  730.15   756.6  741.51   805.8  778.89   826.5  786.95   851.1  792.34
   871.8  812.75   892.4  823.22   921.2   842.8     946  854.57   984.2  866.19
#Mann= 6, -1 ,  0
       0    0.06       0   180.6     0.1       0   240.6    0.06       0
   326.9   0.045       0   370.2    0.07       0  509.15     0.1       0
Bank Sta=326.9,370.2
XS Rating Curve= 0 ,0
Exp/Cntr(USF)=0,0
Exp/Cntr=0.3,0.1

Type RM Length L Ch R = 1 ,29000   ,492.1,500,505.6
BEGIN DESCRIPTION:
Structure 8 XS 1
END DESCRIPTION:
XS GIS Cut Line= 6
 1607063.7624466403893.9493999181607423.80864251404552.320786595
1607459.79479101404618.1234765051607503.79404683404693.790976092
1607552.51770267404773.9988209161607603.60323042404856.476346254
#Sta/Elev= 30
       0  819.26      70  808.26   135.2   793.9   185.3  787.14   271.9  764.91
   370.6   744.4   458.9  722.73   490.8  711.88   503.2  704.21   522.7  688.93
   540.9  680.05   659.3  682.57     664  680.48   673.1  673.73   682.3  672.84
   718.7  673.62   727.8  675.85     736  680.73   741.5  682.04   789.1  684.13
     826  692.89   871.3  697.13   939.5   727.7   967.6  735.36     985  748.53
  1028.8  777.86  1054.8  790.51  1080.3  807.24  1092.6   812.7  1103.8  815.68
#Mann= 10, -1 ,  0
       0    0.05       0      70     0.1       0  517.89    0.05       0
  527.89     0.1       0  625.39    0.05       0   673.1   0.045       0
   718.7    0.05       0  730.39    0.08       0  740.39    0.06       0
  855.39     0.1       0
Bank Sta=673.1,718.7
XS Rating Curve= 0 ,0
Exp/Cntr(USF)=0,0
Exp/Cntr=0.3,0.1

Type RM Length L Ch R = 1 ,28500   ,508.3,498.7,500.8
XS GIS Cut Line= 6
1606843.78519626403996.818616763 1606847.9971301404097.654373094
1606854.02041201404197.717165083 1606864.4518216404296.072283342
1606902.94354251404482.7566212561607027.54926443405085.653381333
#Sta/Elev= 30
       0  816.03    43.8  804.63   119.8  776.36   171.9  762.37   284.5  738.11
   345.5  720.76   394.5  714.53   442.4   702.5   455.5  698.05   472.1   686.8
   484.3  681.99   533.4  679.09     660   682.3   668.1  680.73   680.4  673.24
   688.6  672.59   725.3  673.27   737.6  680.41   753.9  684.35   787.6  684.16
     807  687.48     852   713.1   868.3  724.99   913.2  746.96   953.5  776.89
   986.7  792.11  1006.4  807.13  1035.8   821.5  1076.6     855  1106.3  868.41
#Mann= 7, -1 ,  0
       0     0.1       0  588.19    0.05       0  653.19     0.1       0
   680.4   0.045       0   725.3     0.1       0  753.19    0.06       0
  858.19     0.1       0
Bank Sta=680.4,725.3
XS Rating Curve= 0 ,0
Exp/Cntr(USF)=0,0
Exp/Cntr=0.3,0.1

Type RM Length L Ch R = 1 ,28001   ,335.6,347.2,347.5
XS GIS Cut Line= 6
1606327.70420742404038.4290978461606392.34515426 404433.88532792
1606443.98186201404686.9720920921606472.28167418404782.919734836
1606522.30224343404937.5293337551606588.34148142405013.843485594
#Sta/Elev= 30
       0   757.7    30.1   749.5      67  741.65     152  727.29   281.7  711.57
   289.8  708.55   314.2  692.44   338.5  682.57   562.4  678.98   640.2  679.76
  651.55672.2397   666.8  671.27   714.9  672.32   723.2  677.59   744.1   677.5
   760.8  682.72   811.2  683.65   815.4  685.94   819.6   692.2   826.9  706.75
   832.2  713.11     849  725.67   891.1  744.84   895.3  747.97   903.7  757.75
   921.6   772.7   946.7  787.52   967.9  796.06   983.7  806.25  1022.5  819.35
#Mann= 7, -1 ,  0
       0     0.1       0  410.71    0.05       0  613.67     0.1       0
  651.55   0.045       0   714.9     0.1       0  719.02    0.06       0
  819.06     0.1       0
Bank Sta=651.55,714.9
XS Rating Curve= 0 ,0
Exp/Cntr(USF)=0,0
Exp/Cntr=0.3,0.1

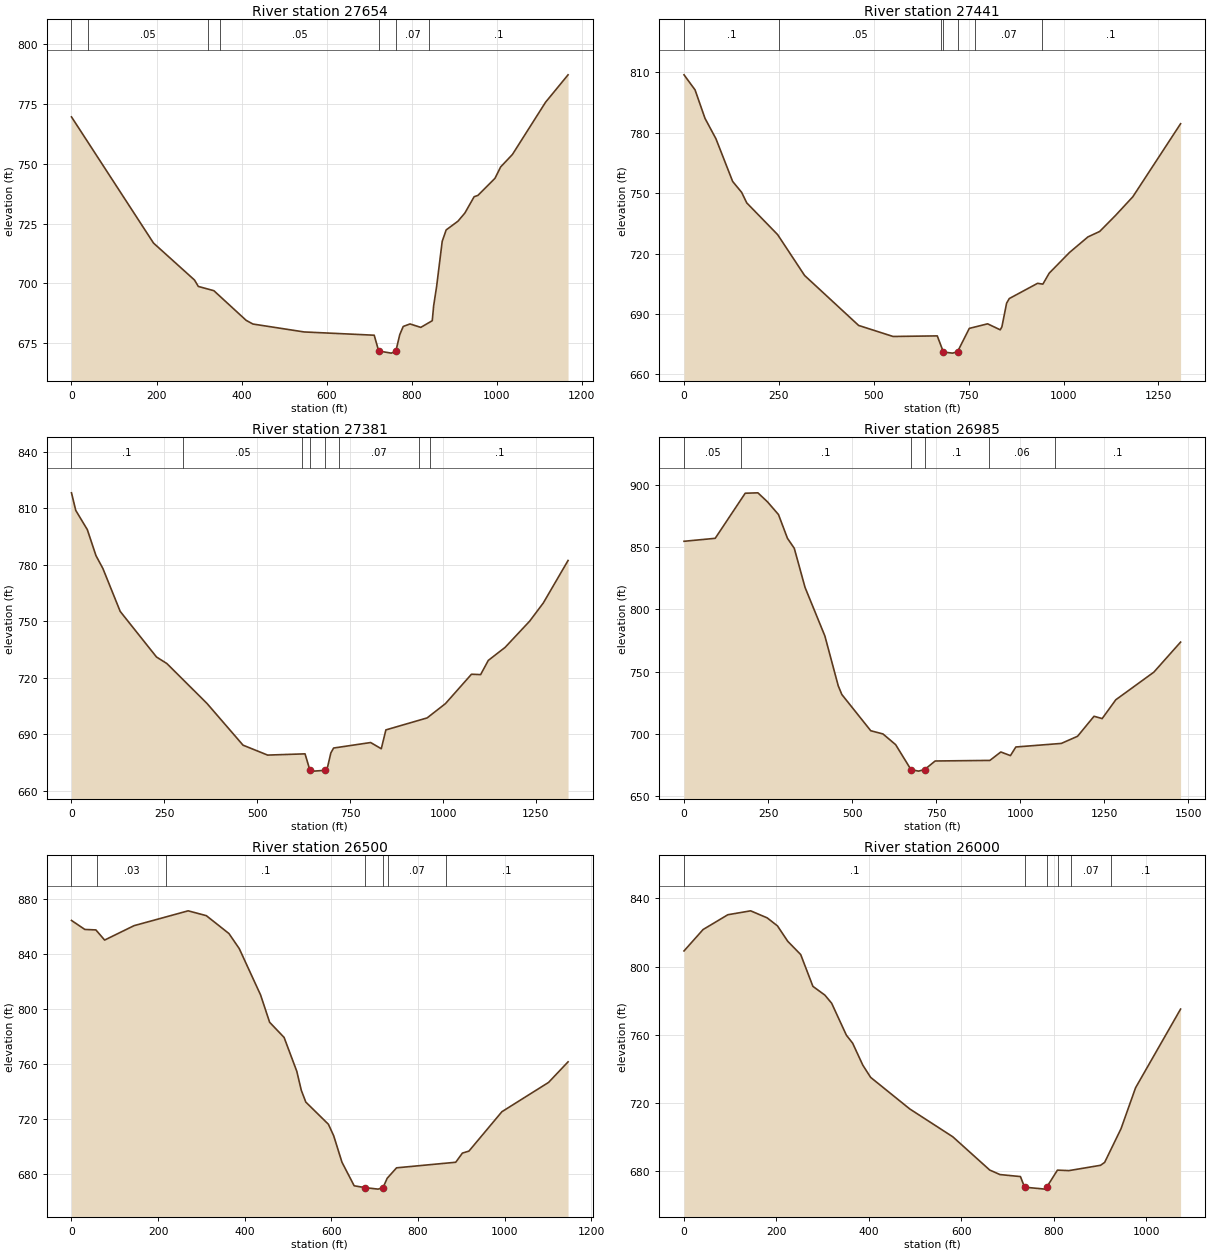
Type RM Length L Ch R = 1 ,27654   ,212.9,212.8,212.8
BEGIN DESCRIPTION:
Structure 7 XS 4
END DESCRIPTION:
XS GIS Cut Line= 4
1605794.11517775404120.6187086511606079.49061137404403.764646705
 1606121.8510273404851.8932573251606407.22646093404987.892487414
#Sta/Elev= 30
       0  769.64     193   716.8   289.5  701.32   298.3  698.66     335  696.86
     411  684.44   426.9   682.9   547.4  679.59   712.2  678.22  722.81671.5994
   752.3  670.72     763  671.48   772.4  678.49   780.5  681.89   796.5  682.94
   821.8   681.5   848.8   684.3   852.1  690.59   859.1   698.7   872.2  717.52
   881.5   722.3   909.4  725.99   925.5  729.38   947.3  736.21   956.3  736.78
   996.4  743.94  1009.7  748.69  1037.4  753.91  1115.4  775.79  1168.3  787.26
#Mann= 7, -1 ,  0
       0     0.1       0      40    0.05       0     320    0.07       0
     350    0.05       0  722.81   0.045       0     763    0.07       0
  842.01     0.1       0
Bank Sta=722.81,763
XS Rating Curve= 0 ,0
Exp/Cntr(USF)=0,0
Exp/Cntr=0.3,0.1

Type RM Length L Ch R = 1 ,27441   ,61.4,60.6,59.3
BEGIN DESCRIPTION:
Structure 7 XS 3
END DESCRIPTION:
XS GIS Cut Line= 5
1605436.06193531404316.3635986061605884.98667651404602.042979367
1605895.51863524 404716.578030641605910.00007851404870.607927179
1606397.10317013405008.839885612
#Sta/Elev= 30
       0  808.77    29.1  801.28    55.2  787.19    84.2  776.98   128.1  755.83
   151.8  750.41   165.3  745.17   246.6  729.42   317.7  709.12     460  684.32
   550.7  678.84   667.2  679.13   683.3  671.11   707.4  670.57  720.51671.2451
   751.6  682.86   799.8  685.12   833.1  682.15   837.5  683.65   849.8  695.36
   856.9  697.67   931.4  705.23   945.4  704.84     962  710.26  1015.6  720.56
  1064.2  728.29  1095.1  730.99  1136.7  738.92  1182.4  748.22  1308.2  784.48
#Mann= 7, -1 ,  0
       0     0.1       0     250    0.05       0  677.13     0.1       0
   683.3   0.045       0  720.51     0.1       0  767.13    0.07       0
  941.84     0.1       0
Bank Sta=683.3,720.51
XS Rating Curve= 0 ,0
Exp/Cntr(USF)=0,0
Exp/Cntr=0.3,0.1

Type RM Length L Ch R = 1 ,27381   ,446.7,395.7,368.7
BEGIN DESCRIPTION:
Structure 7 XS 2
END DESCRIPTION:
XS GIS Cut Line= 6
1605391.54461717404369.2821003451605821.79492408404625.739886527
1605836.27636734404748.1739068531605849.44131577404833.746071597
 1605859.9732745404898.2543188661606404.92129667405028.813064778
#Sta/Elev= 30
       0  818.25    11.5   808.9    42.6  798.71    65.9  784.88    84.5  778.06
   131.1  755.25   228.8  731.03   256.8  727.54   364.6  706.38   461.7  684.19
   527.9  678.92   628.6  679.58   641.9  670.77   652.4   670.4   681.2  670.81
   689.3  672.63     698  680.04   705.5  682.67   805.1  685.59   833.8  682.29
   846.2   692.3   957.2  698.67  1006.6  706.28  1076.5  721.87  1101.2  721.68
  1121.8  729.22    1167  736.13    1233  750.04  1269.8  759.71  1336.5  782.31
#Mann= 8, -1 ,  0
       0     0.1       0     300    0.05       0  620.89     0.1       0
   641.9   0.045       0   681.2     0.1       0  720.75    0.07       0
  936.11    0.06       0  966.11     0.1       0
Bank Sta=641.9,681.2
XS Rating Curve= 0 ,0
Exp/Cntr(USF)=0,0
Exp/Cntr=0.3,0.1

Type RM Length L Ch R = 1 ,26985   ,490.4,485,483.5
BEGIN DESCRIPTION:
Structure 7 XS 1
END DESCRIPTION:
XS GIS Cut Line= 6
1605271.12134685405567.1327333451605614.14165817 405014.85824734
1605696.77338268404945.2429010121605860.96399917404951.283899426
1606064.27953742404994.9435890021606406.72394274405046.499933705
#Sta/Elev= 30
       0  854.64    92.7  857.02     182  893.18   219.7   893.5   247.9  886.36
   280.9   876.1   307.6  857.03   327.9  849.02   359.9  817.66   418.9   778.7
   458.6  738.78   469.2  731.83   555.3  702.73   591.6  700.16   629.3  691.58
  674.88671.5895   697.2  670.34   715.6  671.59   746.8  678.47   909.6  678.93
   942.1   685.7   970.7  682.78   986.8  689.69  1122.1  692.56  1170.4  698.31
  1219.3  714.33  1243.5  712.48    1284  727.55  1397.2  749.71  1476.7   773.8
#Mann= 6, -1 ,  0
       0    0.05       0  169.56     0.1       0  674.88   0.045       0
   715.6     0.1       0  908.18    0.06       0 1102.48     0.1       0
Bank Sta=674.88,715.6
XS Rating Curve= 0 ,0
Exp/Cntr(USF)=0,0
Exp/Cntr=0.3,0.1

Type RM Length L Ch R = 1 ,26500   ,505.1,500,495.1
XS GIS Cut Line= 6
1605603.38905501405787.1762565081606021.08408576405288.639852002
1606085.30672634  405211.98843051606133.47296859405154.499372259
1606200.53418617405096.5513254261606432.72326813405092.037986587
#Sta/Elev= 30
       0  864.21    30.8  857.66    56.3  857.31    76.5  849.94   144.4  860.41
   269.3   871.2   311.3  867.68   363.5  854.67   387.3  843.72   436.6  809.96
   457.4  790.16   490.8  779.13   520.1  754.52   530.5   740.7   540.9  732.13
   593.1  715.99   605.3  707.62   624.4  688.37   652.6  671.25   678.2  669.89
   707.9  668.83  719.27670.0123   728.8  676.74   750.4  684.32     887  688.37
   902.4  695.03   917.5  696.48   993.6  725.13  1101.3  746.42  1146.3  761.39
#Mann= 7, -1 ,  0
       0    0.05       0      60    0.03       0  218.83     0.1       0
   678.2   0.045       0  719.27     0.1       0  730.39    0.07       0
  865.39     0.1       0
Bank Sta=678.2,719.27
XS Rating Curve= 0 ,0
Exp/Cntr(USF)=0,0
Exp/Cntr=0.3,0.1

Type RM Length L Ch R = 1 ,26000   ,441.2,469.4,489
XS GIS Cut Line= 6
  1606057.498383406044.3450335121606202.25203051405989.095800176
1606281.62555942405911.9207576661606328.53228976405824.499016508
1606368.87210409405736.402736008  1606634.335812405184.421556503
#Sta/Elev= 30
       0  809.18    41.3  821.77    94.8  830.45   144.1  832.75   179.9  828.61
   202.2  823.89   224.5  814.81   252.4  807.05   278.8  788.37   304.8   783.2
   319.4  778.43   351.2  759.68   364.8  754.96   386.8  742.04   403.7  734.87
   488.2  716.34   581.4  699.96   661.3  680.41   683.5  677.75   727.8  676.56
   736.7  670.33   781.2  669.19   784.8  670.43   807.8  680.35   832.7  680.07
     901  683.19   909.9  684.89   945.4  704.73   976.8  728.75  1074.2  775.01
#Mann= 6, -1 ,  0
       0     0.1       0   736.7   0.045       0   784.8     0.1       0
  808.01    0.08       0  837.99    0.07       0     923     0.1       0
Bank Sta=736.7,784.8
XS Rating Curve= 0 ,0
Exp/Cntr(USF)=0,0
Exp/Cntr=0.3,0.1

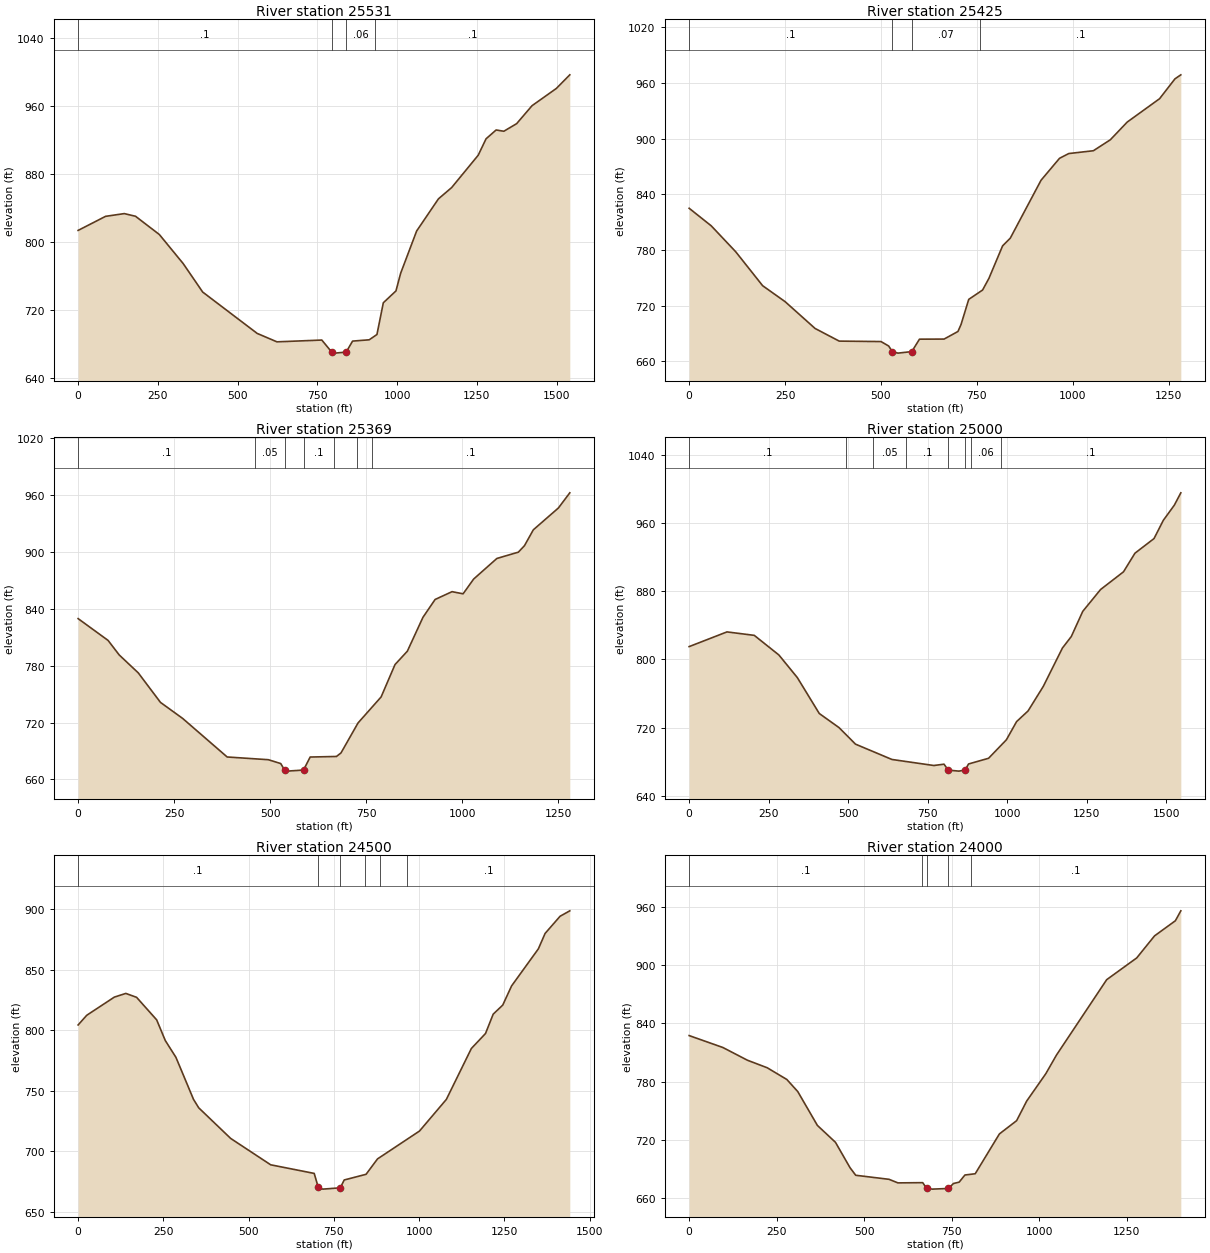
Type RM Length L Ch R = 1 ,25531   ,104.8,105.2,105.6
BEGIN DESCRIPTION:
Structure 6 XS 4
END DESCRIPTION:
XS GIS Cut Line= 6
1606065.69624638406061.8638919851606221.89868987406014.381703492
1606416.87041279405896.3871888181606509.63892805405851.590690489
1606588.66421293405794.3546850281607534.06801635405704.243156819
#Sta/Elev= 30
       0  813.23    86.1  829.79   144.7  833.01   179.9  829.89   254.6   808.4
   329.3  774.21   390.5  740.67   561.4  691.96   623.3  682.06     764  684.16
  794.86670.0618   804.2  668.77   840.3  669.96   860.4  682.92   912.6  684.46
   936.8  690.68   956.8  728.05   996.4     742  1011.1  762.77  1061.3  812.55
  1129.6  850.38    1171  863.65  1254.2   901.7  1278.9  921.08  1310.4  931.44
  1334.6  929.95  1374.7  938.87    1423  960.03  1499.3  980.36  1541.4  996.37
#Mann= 4, -1 ,  0
       0     0.1       0  794.86   0.045       0   840.3    0.06       0
  931.75     0.1       0
Bank Sta=794.86,840.3
XS Rating Curve= 0 ,0
Exp/Cntr(USF)=0,0
Exp/Cntr=0.3,0.1

Type RM Length L Ch R = 1 ,25425   ,58,56.4,55.2
BEGIN DESCRIPTION:
Structure 6 XS 3
END DESCRIPTION:
XS GIS Cut Line= 3
1606287.06819961406031.7136385831606761.65646372405882.185829344
1607543.42685767405823.674947468
#Sta/Elev= 30
       0  824.83    57.6  805.89   121.4  777.95   191.5   741.4   250.2  724.15
   328.2  695.31   391.1  681.67   500.1  681.18   520.1  676.35  529.42670.4286
   544.2  668.72   580.3  670.37   600.3  683.76   664.5  683.86   700.6  692.05
   708.6  699.54   728.7  726.64   764.8  736.72   781.3  749.27   816.9  784.27
     837  792.62   917.2  855.04   965.3  878.66   989.4  883.79  1053.6  886.83
  1097.7  898.61  1141.8  917.73  1226.1  942.89  1266.2  964.28  1281.5  968.63
#Mann= 4, -1 ,  0
       0     0.1       0  529.42   0.045       0   580.3    0.07       0
  757.59     0.1       0
Bank Sta=529.42,580.3
XS Rating Curve= 0 ,0
Exp/Cntr(USF)=0,0
Exp/Cntr=0.3,0.1

Type RM Length L Ch R = 1 ,25369   ,364.9,369,371.9
BEGIN DESCRIPTION:
Structure 6 XS 2
END DESCRIPTION:
XS GIS Cut Line= 4
1606280.56699051406065.844986344 1606750.2793478405943.947315769
1606899.80715704405924.443688477 1607541.8015554405874.059317972
#Sta/Elev= 30
       0  829.49      78  806.53     107   791.2   156.6  772.33   214.4  741.23
   272.3  724.28     388  683.71   495.2  680.84   527.5  676.78   537.3670.0827
   543.6  668.81  586.75669.9236   604.1  683.66   672.5  684.25   684.4  688.02
   728.7  719.56   788.8  746.98     825  781.11   857.1  795.19   897.7  830.85
   929.3  849.66   973.4   857.9  1002.2  855.63  1029.6  871.15  1090.1  892.87
  1146.1  899.53    1162  906.35  1185.1  923.09  1250.3  946.06    1280  962.04
#Mann= 7, -1 ,  0
       0     0.1       0     460    0.05       0   537.3   0.045       0
  586.75     0.1       0  666.07    0.06       0  726.07    0.07       0
  766.07     0.1       0
Bank Sta=537.3,586.75
XS Rating Curve= 0 ,0
Exp/Cntr(USF)=0,0
Exp/Cntr=0.3,0.1

Type RM Length L Ch R = 1 ,25000   ,468,500,520.5
BEGIN DESCRIPTION:
Structure 6 XS 1
END DESCRIPTION:
XS GIS Cut Line= 6
1606077.29033817406100.9991196691606241.83594084406102.403972507
  1606360.793052406138.5367742631606670.32228859406264.113622844
1606761.88083251406291.4970982521607588.36966509406297.619461343
#Sta/Elev= 30
       0  815.03   118.8  832.29   204.6  828.25     282   805.2   339.9  778.69
   408.9  736.47   470.9  719.92   522.8  700.45   637.3  682.45   768.9  675.36
     801  676.92   814.1  669.96   847.9  668.76   867.3670.1067   878.1  677.17
     941  683.86     997  705.57    1029  726.91    1065  739.41    1113  768.32
    1173   813.3    1201  826.88    1237  856.44    1293  882.09    1365  902.87
    1401  924.75    1461  941.95  1490.1  963.33    1525  981.32  1545.2  995.67
#Mann= 8, -1 ,  0
       0     0.1       0  494.41    0.07       0  576.45    0.05       0
  682.92     0.1       0   814.1   0.045       0   867.3     0.1       0
  884.83    0.06       0  979.83     0.1       0
Bank Sta=814.1,867.3
XS Rating Curve= 0 ,0
Exp/Cntr(USF)=0,0
Exp/Cntr=0.3,0.1

Type RM Length L Ch R = 1 ,24500   ,504.4,500,495.9
XS GIS Cut Line= 6
1606050.96624383406120.2359578461606189.18840834406140.877648845
1606255.49765892406215.4844550041606422.79227184406451.216923177
1606574.71322784406665.2873611751606951.12586084407195.684922427
#Sta/Elev= 30
       0  804.46    25.4   812.5   106.3  827.51   139.8  830.55   171.4  827.32
   230.3  808.68   255.6  791.56   286.7  777.72   338.3  742.94   353.7  735.92
   447.3  710.63   564.6  688.83   692.1  681.72   704.1670.1545   717.5  668.72
   768.6  669.79   780.1  676.28   844.2  680.98   877.7  693.69  1000.9  716.76
  1079.6  742.91  1152.9     785  1194.4  797.41  1216.9   813.4  1244.9   820.9
  1270.9  836.78  1349.4  867.43    1369  880.12  1413.1  894.37  1441.5  898.84
#Mann= 6, -1 ,  0
       0     0.1       0   704.1   0.045       0   768.6     0.1       0
  841.13    0.07       0  886.13    0.06       0  963.63     0.1       0
Bank Sta=704.1,768.6
XS Rating Curve= 0 ,0
Exp/Cntr(USF)=0,0
Exp/Cntr=0.3,0.1

Type RM Length L Ch R = 1 ,24000   ,371.1,388,404.7
XS GIS Cut Line= 6
1605712.35799718406410.283934176 1605767.4536875406496.771622092
1605830.96471535406573.5336076771605893.53480017406649.786407918
1605956.56321742406723.4735964981606643.39189626407459.402898923
#Sta/Elev= 30
       0  827.51    96.3   815.2   166.3  802.06   222.9  794.26     279  782.14
   310.3  769.62   366.3  734.66     418  717.16   459.4  691.01   475.8  683.12
   570.9  678.94   596.3  675.25   667.1  675.49   678.5  669.56   694.7   668.8
   740.7  669.48   754.8  674.58   771.3  676.04   787.7  683.39   817.1   684.7
   886.2  725.86   935.4  739.57   964.2  759.88  1018.6  788.03  1049.1  807.31
  1192.6  885.28  1278.4  907.78  1329.3  930.56  1388.8  946.19  1404.4  956.46
#Mann= 5, -1 ,  0
       0     0.1       0  664.03    0.06       0   678.5   0.045       0
   740.7    0.06       0  804.03     0.1       0
Bank Sta=678.5,740.7
XS Rating Curve= 0 ,0
Exp/Cntr(USF)=0,0
Exp/Cntr=0.3,0.1

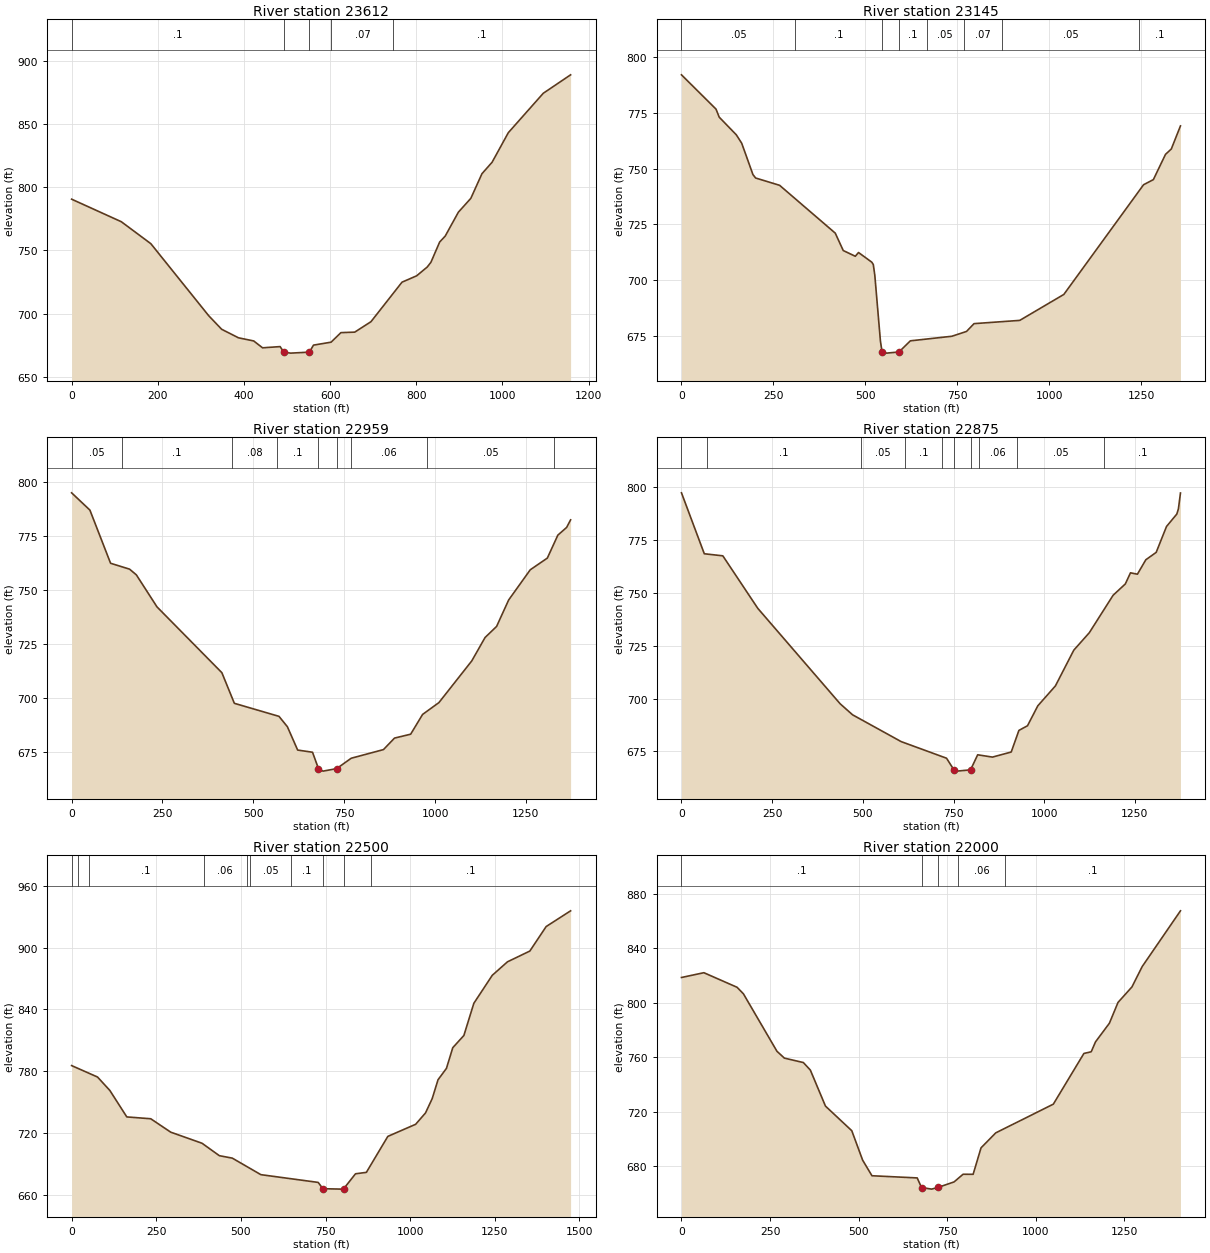
Type RM Length L Ch R = 1 ,23612   ,460.9,467.3,468.1
XS GIS Cut Line= 4
1605644.17085554 406635.423138931605794.05984306406965.901268046
1605850.04247695407244.0085460991606281.65052536407518.504041321
#Sta/Elev= 30
       0  790.48   115.4  772.64   183.9  755.28   318.1  698.36   348.2  687.61
   387.2  680.87   422.7  678.36   443.1  672.94   483.9   673.9   492.5  669.49
   508.4  668.74  551.78669.5195   561.4  675.07   602.2   677.4     625  684.94
   657.1  685.34   694.8   693.6   766.8  724.84   800.7  729.86   825.2  736.77
   833.9  740.56   854.2  756.58   867.1   761.3   897.6  780.17   926.6  791.17
   952.4  810.63   975.9  819.68  1013.5  843.03  1094.6   874.2  1158.1  888.81
#Mann= 5, -1 ,  0
       0     0.1       0   492.5   0.045       0  551.78     0.1       0
  602.88    0.07       0  746.57     0.1       0
Bank Sta=492.5,551.78
XS Rating Curve= 0 ,0
Exp/Cntr(USF)=0,0
Exp/Cntr=0.3,0.1

Type RM Length L Ch R = 1 ,23145   ,187.7,186,183.2
BEGIN DESCRIPTION:
Structure 5 XS 4
END DESCRIPTION:
XS GIS Cut Line= 4
1605600.82946155406608.3347676911605353.42233757407016.466227692
1605391.34605731407339.7207911441605055.45025394407780.358296632
#Sta/Elev= 30
       0  792.02    93.9  776.65   102.6  773.04   149.2   765.1   163.8  761.34
   194.3   747.3   201.6  745.76   266.9  742.47   418.1  721.04   439.9  713.23
   472.7  710.66   481.4  712.35   517.6  707.99   521.6  706.94   525.7  702.16
     541  672.57  545.33667.8882   557.9  667.23  591.51667.7544   622.3  672.74
   735.1  674.79     775  676.95   795.5  680.45   919.8  681.91  1039.7  693.55
  1256.4  742.73  1283.1  745.03  1316.1  756.35  1331.9  758.76  1356.8  769.12
#Mann= 8, -1 ,  0
       0    0.05       0     310     0.1       0  545.33   0.045       0
  591.51     0.1       0  667.26    0.05       0  767.26    0.07       0
  872.74    0.05       0 1242.74     0.1       0
Bank Sta=545.33,591.51
XS Rating Curve= 0 ,0
Exp/Cntr(USF)=0,0
Exp/Cntr=0.3,0.1

Type RM Length L Ch R = 1 ,22959   ,84.5,84.1,83.7
BEGIN DESCRIPTION:
Structure 5 XS 3
END DESCRIPTION:
XS GIS Cut Line= 6
 1605530.8218631406572.216939372 1605212.9849739406949.648245302
1605166.03179708406991.1837478691605162.42001425407043.554598931
1605214.79086531407287.3499400821604925.84823876407713.540314242
#Sta/Elev= 30
       0  794.86    50.4  786.84   107.2  762.23   159.5  759.49   178.2  756.84
   234.9  742.02   413.5  711.51   447.8  697.33   570.6  691.29   593.7  686.49
     622  675.67   662.9  674.66   679.3  667.05   691.8  665.91  729.29 667.069
   769.3  671.88   858.1  675.89   888.5  681.22   932.9  683.02   965.8  692.19
  1010.6  697.65  1101.1  716.99  1137.6  727.81  1169.4  732.96  1202.6  745.22
    1262   759.2    1309  764.62  1337.9  775.25  1362.1  778.83    1373  782.33
#Mann= 9, -1 ,  0
       0    0.05       0     140     0.1       0     440    0.08       0
  566.23     0.1       0   679.3   0.045       0  729.29     0.1       0
  768.73    0.06       0  978.08    0.05       0 1328.08     0.1       0
Bank Sta=679.3,729.29
XS Rating Curve= 0 ,0
Exp/Cntr(USF)=0,0
Exp/Cntr=0.3,0.1

Type RM Length L Ch R = 1 ,22875   ,344.2,374.7,405.4
BEGIN DESCRIPTION:
Structure 5 XS 2
END DESCRIPTION:
XS GIS Cut Line= 6
 1605492.4759766406557.7698080451605106.01521359406933.395222559
1605077.12095093406992.9896392851605115.04467067407218.726066276
1605087.95629943 407283.738157251604836.93739261407681.034268755
#Sta/Elev= 30
       0  797.26    62.9  768.46     114  767.48   210.4  742.66   437.3  697.58
   471.7  692.34   605.7  679.67   730.8  671.82     751  666.35   759.2  665.72
  797.04666.3208   816.6  673.44   857.3  672.35   909.1  674.75   930.3  684.97
     954  687.17   982.4  696.59  1030.9  705.99  1081.7  722.92  1124.3  731.12
    1190  748.84  1223.7   754.2  1237.9  759.45    1257   758.8  1280.2  765.62
  1308.8  769.12  1337.2  781.34  1365.6  787.22  1370.1  789.72  1375.7  797.18
#Mann= 10, -1 ,  0
       0    0.05       0      70     0.1       0  493.75    0.05       0
  615.72     0.1       0  718.97    0.05       0     751   0.045       0
  797.04    0.05       0  818.97    0.06       0  925.72    0.05       0
 1165.72     0.1       0
Bank Sta=751,797.04
XS Rating Curve= 0 ,0
Exp/Cntr(USF)=0,0
Exp/Cntr=0.3,0.1

Type RM Length L Ch R = 1 ,22500   ,501.6,500,496.1
BEGIN DESCRIPTION:
Structure 5 XS 1
END DESCRIPTION:
XS GIS Cut Line= 6
1605370.25566301406398.5549550061605236.03316243406599.423647761
1605098.37694168406777.3698141721605023.17269576406834.155461758
1604496.80727868 407153.425492511604239.31337109407302.103016675
#Sta/Elev= 30
       0  785.48    76.5   774.4   112.9  761.39     163   735.7   233.7  733.91
   292.8   720.9   385.2  710.16   436.4  698.09   474.5  695.74     559  679.69
   728.2  672.18   742.2  666.08   798.3  665.66   803.6  666.03   838.5  680.53
   870.6  681.92     934  716.81  1016.2  728.56  1045.3  739.57    1065  753.42
  1082.2  771.71  1107.1  782.78  1125.8  802.84  1158.6  814.69    1188  845.89
  1242.4  873.03  1287.3  886.12  1353.4  896.57  1401.6  920.33  1473.8  935.59
#Mann= 10, -1 ,  0
       0     0.1       0      20    0.05       0      50     0.1       0
  390.24    0.06       0  516.62    0.07       0  526.62    0.05       0
  648.36     0.1       0   742.2   0.045       0   803.6    0.06       0
  883.36     0.1       0
Bank Sta=742.2,803.6
XS Rating Curve= 0 ,0
Exp/Cntr(USF)=0,0
Exp/Cntr=0.3,0.1

Type RM Length L Ch R = 1 ,22000   ,496,500,505.3
XS GIS Cut Line= 6
1605149.10781135406052.219033509 1604578.5308685406539.587481335
1604459.06194735406649.9192816761604321.26530692406782.097495005
1604243.84124917 406845.244022251604073.92098534406960.299238339
#Sta/Elev= 30
       0   818.5    63.3  822.01     157  811.31   174.9  806.52   269.6  764.33
   290.6   759.3   344.2  756.04   363.9  750.52   406.6  724.07   480.9     706
   511.6  684.37   537.9  672.92   665.6  671.33   677.9  664.29   706.2   663.1
  723.96664.2982   769.8   668.4   795.2  674.02   823.6  673.98   845.9   693.4
   887.5  704.41  1050.1   725.5  1136.4  762.72  1157.1  763.96  1169.1   771.2
  1208.4  784.91  1232.7  800.17  1272.2  811.61  1300.9  826.48  1409.1  867.45
#Mann= 5, -1 ,  0
       0     0.1       0   677.9   0.045       0  723.96     0.1       0
  780.39    0.06       0  913.02     0.1       0
Bank Sta=677.9,723.96
XS Rating Curve= 0 ,0
Exp/Cntr(USF)=0,0
Exp/Cntr=0.3,0.1