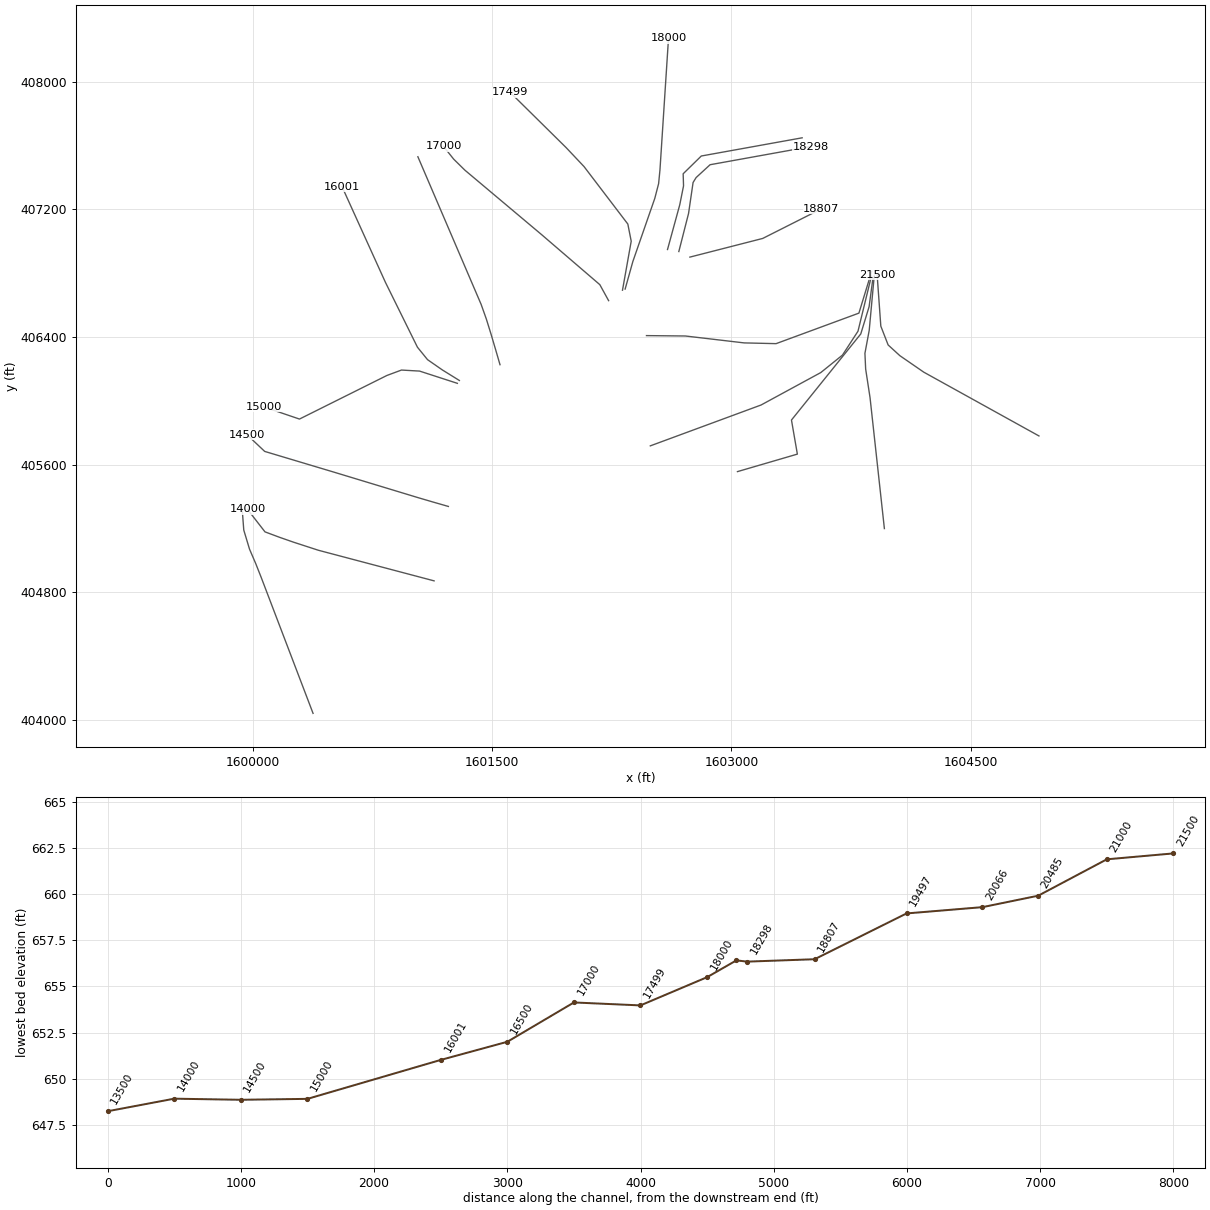
HEC-RAS study LTLFSHNGCK.prj: LTLFSHNGCK

--- LTLFSHNGCK.g01 (geometry) --- (continued)

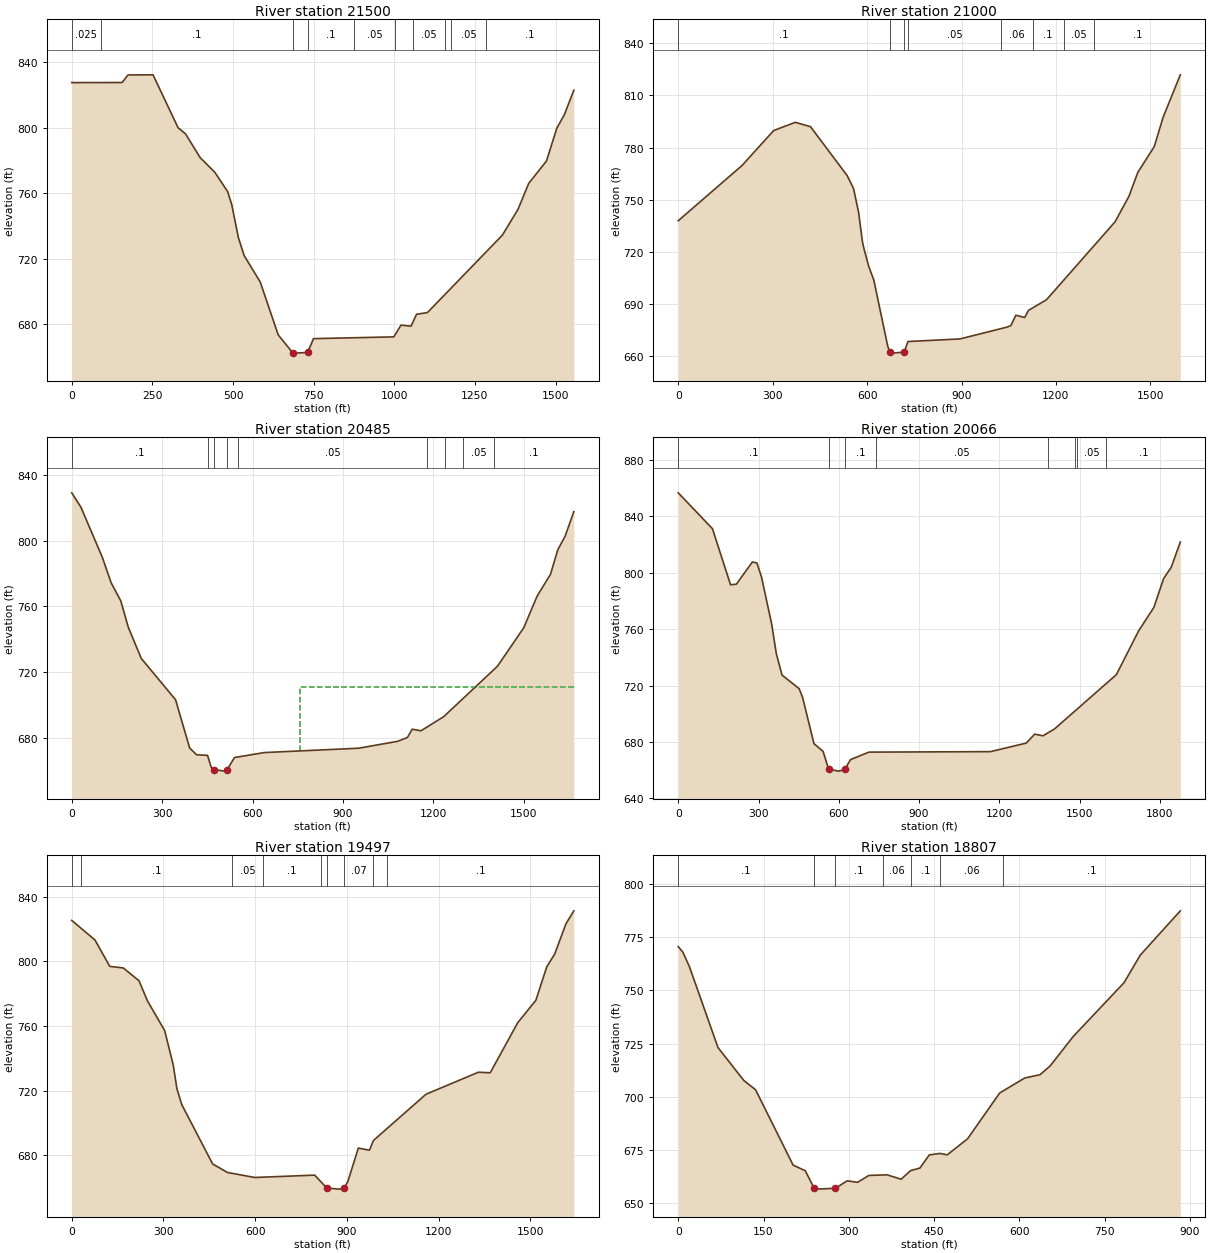
Type RM Length L Ch R = 1 ,21500   ,519,500,474.5
XS GIS Cut Line= 6
1604928.95273983405779.5519279241604206.80884293406179.280459166
 1604056.8038936406282.6450818331603983.34603526406349.814566925
 1603937.5009826406467.7250922621603914.40424401406789.555157259
#Sta/Elev= 30
       0  827.44   156.2   827.5   174.4  832.13     252  832.19   329.6  799.89
   352.5  796.19   398.1  781.63   443.8   772.6   483.5  760.83   496.1  752.86
   516.8  732.63   534.4  721.83   584.5  705.62   640.1  673.34   684.6  662.54
   693.5   662.2   731.4  662.63   749.6  671.04   998.6  672.13  1020.8  679.31
    1052  678.66    1069  685.92  1102.9  686.98  1335.3  734.29  1383.7  750.04
  1416.8  765.86  1471.9  779.54  1503.8  799.47  1527.8  808.02  1556.8  822.82
#Mann= 10, -1 ,  0
       0   0.025       0      90     0.1       0   684.6   0.045       0
   731.4     0.1       0  875.42    0.05       0 1003.12    0.08       0
 1057.68    0.05       0 1157.22     0.1       0 1177.22    0.05       0
 1283.73     0.1       0
Bank Sta=684.6,731.4
XS Rating Curve= 0 ,0
Exp/Cntr(USF)=0,0
Exp/Cntr=0.3,0.1

Type RM Length L Ch R = 1 ,21000   ,510.7,515,513.7
XS GIS Cut Line= 6
1603959.86740768405198.9769735931603869.95157701406019.455319509
1603842.45130393406198.7768112571603837.88569626406297.362572089
1603864.77081309406441.4990948441603896.22186567406782.998739928
#Sta/Elev= 30
       0  737.96   202.8  769.75   303.4  789.84   371.8  794.52   420.1  792.06
   536.8  763.89   556.9  756.52     573   742.8     585  726.18   589.1   722.6
   605.2  711.72   621.3  703.93   665.5  665.93   672.1  662.49   681.6  661.88
   717.8  662.49   729.9  668.55   895.3  670.04  1044.6  676.84  1056.7   677.7
  1072.6  683.67  1100.7  682.36  1112.8  686.47  1169.8  692.53  1387.8  737.36
    1432  752.05  1460.1  765.76  1512.3  780.57  1540.4  797.39  1595.1  821.84
#Mann= 8, -1 ,  0
       0     0.1       0   672.1   0.045       0   717.8     0.1       0
  730.39    0.05       0 1026.82    0.06       0 1125.51     0.1       0
 1225.51    0.05       0 1322.13     0.1       0
Bank Sta=672.1,717.8
XS Rating Curve= 0 ,0
Exp/Cntr(USF)=0,0
Exp/Cntr=0.3,0.1

Type RM Length L Ch R = 1 ,20485   ,454.6,418.7,380.3
XS GIS Cut Line= 6
1603038.70261996405555.9456429331603414.21389961 405665.63841331
1603377.28451506405879.2647849061603811.82037307   406418.848438
1603864.02486318 406589.560496831603888.81098944406773.257419485
#Sta/Elev= 30
       0  829.06    30.6  820.25     102  789.59   130.6  774.44   162.9  763.28
   187.6  747.37   230.6  728.43   344.5  703.29   391.2  674.01   414.3  669.84
   450.7   669.5   462.9  662.16     471  660.89   507.5  659.91   515.7  660.86
   540.1  668.17   639.2   671.2   951.9  673.83  1082.3  678.05  1114.1  680.37
  1129.9  685.41    1159  684.41  1234.9  693.08    1413  723.69  1500.1  747.03
  1544.5  766.27  1588.9  779.56  1613.2  794.47  1637.4  802.68  1666.4   817.6
#Mann= 9, -1 ,  0
       0     0.1       0  453.05   0.025       0     471   0.045       0
   515.7   0.025       0  553.05    0.05       0 1180.05    0.06       0
 1240.05     0.1       0 1300.05    0.05       0 1402.48     0.1       0
#XS Ineff= 2 , 0
                          757.01          711.03
Permanent Ineff=
       F       F
Bank Sta=471,515.7
XS Rating Curve= 0 ,0
Exp/Cntr(USF)=0,0
Exp/Cntr=0.3,0.1

Type RM Length L Ch R = 1 ,20066   ,567.8,569.5,562.8
XS GIS Cut Line= 6
1602492.20284864405717.3771535161603186.63896726405973.452458754
1603560.84688026406176.5868950041603697.08381251406286.267778009
1603794.36970717 406435.951533751603878.62150717406781.611931667
#Sta/Elev= 30
       0  856.74   127.8  831.31   195.5  791.52   217.2  791.91     277  807.66
   294.1  806.99   311.1  797.08   349.5  763.35   366.5  742.66   387.9  727.44
   451.8  717.81   464.6  711.68   507.2  678.82   541.3  673.29  562.41660.4985
     601  659.29   622.3  660.48   643.7  667.45   712.5  672.77  1166.6  673.11
  1300.5  679.17  1332.4  685.55  1363.3  684.35  1406.3  689.22  1637.4  727.76
  1720.4  758.76  1777.4  775.43  1814.1  795.97  1842.6     804  1876.3  821.86
#Mann= 8, -1 ,  0
       0     0.1       0  562.41   0.045       0   622.3     0.1       0
     740    0.05       0 1381.55    0.06       0 1481.55     0.1       0
 1491.55    0.05       0 1600.07     0.1       0
Bank Sta=562.41,622.3
XS Rating Curve= 0 ,0
Exp/Cntr(USF)=0,0
Exp/Cntr=0.3,0.1

Type RM Length L Ch R = 1 ,19497   ,687,690.3,689.6
XS GIS Cut Line= 6
1602468.24867176406408.4112345131602711.56511426406405.997525424
1603080.38130575406362.6983994251603280.70931718406357.988107011
1603800.16529925406549.3374618441603880.07032317406809.958331674
#Sta/Elev= 30
       0  825.32    75.9   813.2   124.3  796.87   168.6  795.88   219.9  787.99
   247.9  775.42   304.1  757.07   332.1  735.82   344.2  720.96   360.2  711.18
     461  674.52   509.5  669.26     599  666.16   794.8  667.62  834.52659.6476
   874.4  658.95   890.3  659.59   902.9  663.42   937.7  684.36   974.1  683.04
   987.3   689.1    1159  717.69  1330.4  731.32  1369.2  730.99  1459.1  761.96
  1518.5  775.85  1554.3  796.63  1579.9  804.39  1616.8  823.15  1642.8  831.25
#Mann= 9, -1 ,  0
       0    0.05       0      30     0.1       0  524.23    0.05       0
   624.9     0.1       0  815.43    0.07       0  834.52   0.045       0
   890.3    0.07       0  986.97    0.08       0 1032.37     0.1       0
Bank Sta=834.52,890.3
XS Rating Curve= 0 ,0
Exp/Cntr(USF)=0,0
Exp/Cntr=0.3,0.1

Type RM Length L Ch R = 1 ,18807   ,495.1,508.2,520
BEGIN DESCRIPTION:
Structure 4 XS 4
END DESCRIPTION:
XS GIS Cut Line= 3
1602740.40172908 406900.417642571603197.11166817407017.439406323
1603564.42998217407202.723865598
#Sta/Elev= 30
       0  770.59       8  768.08    19.6  761.21    69.9  723.11   115.3  707.61
     136  703.23     202  667.78   223.4  665.12   239.2  656.78   243.3  656.47
   276.4  656.86     297  660.37   315.4  659.69   335.1   662.9   367.2   663.2
     392  661.14   408.5  665.17     425  666.39   441.5  672.57     460  673.27
     473   672.6   508.8  680.15   565.3  701.72   609.2  708.76   636.1  710.32
     654  714.43   694.4  728.26     784  753.64   812.5  766.61   882.9  787.45
#Mann= 7, -1 ,  0
       0     0.1       0   239.2   0.045       0   276.4     0.1       0
     360    0.06       0     410     0.1       0     460    0.06       0
  571.46     0.1       0
Bank Sta=239.2,276.4
XS Rating Curve= 0 ,0
Exp/Cntr(USF)=0,0
Exp/Cntr=0.3,0.1

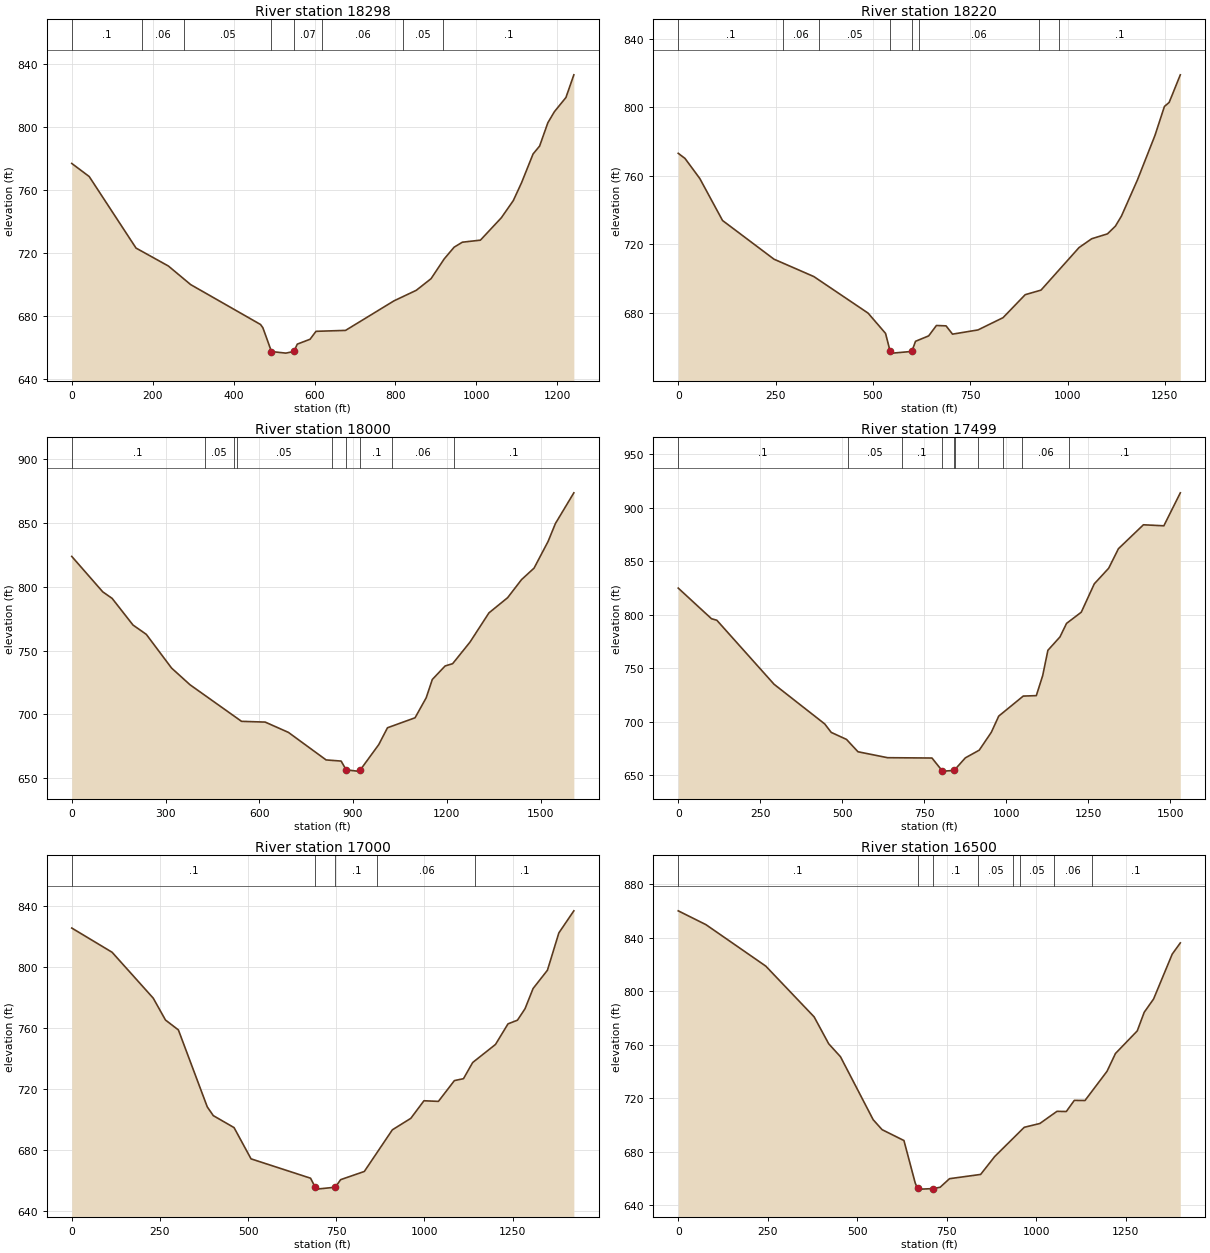
Type RM Length L Ch R = 1 ,18298   ,77.9,78.2,77.7
BEGIN DESCRIPTION:
Structure 4 XS 3
END DESCRIPTION:
XS GIS Cut Line= 6
1602671.03208149406935.3040010831602731.96832361407173.759395239
 1602760.4046122 407368.074033951602779.36213793407398.880013258
1602867.04069442407479.4494976011603499.36246283407593.484398006
#Sta/Elev= 30
       0  776.96    43.1  768.64   158.8  723.15   238.7  711.75   293.9  699.91
   466.4  674.57   472.3  672.47   493.5  657.35     529  656.34   548.9  657.41
   557.4  662.07   588.9  665.16   603.6  670.21   676.6  670.79   796.4   689.6
   851.4  696.29     888   703.7   920.4  716.25   944.9   723.7   965.2  726.88
  1009.9  728.18  1061.6  742.41  1091.2  753.36  1111.5  764.67    1140  782.98
  1156.2  788.03  1176.6  802.86  1192.8  809.89  1221.3  818.92  1240.8  833.32
#Mann= 8, -1 ,  0
       0     0.1       0  173.32    0.06       0  276.24    0.05       0
   493.5   0.045       0   548.9    0.07       0   618.3    0.06       0
   818.3    0.05       0   918.3     0.1       0
Bank Sta=493.5,548.9
XS Rating Curve= 0 ,0
Exp/Cntr(USF)=0,0
Exp/Cntr=0.3,0.1

Type RM Length L Ch R = 1 ,18220   ,199,220.1,237.9
BEGIN DESCRIPTION:
Structure 4 XS 2
END DESCRIPTION:
XS GIS Cut Line= 6
1602600.08217617 406948.016583161602676.86186486407228.382021761
1602700.55877202407346.8665575611602698.18908131407422.696660472
1602811.93423567407534.0721241241603444.25600409407648.107024529
#Sta/Elev= 30
       0  773.11    17.4  770.12    55.3  758.43   113.8  733.87     246  711.27
   348.3  701.13   487.7  679.77   532.5  667.93   544.3  657.45   550.3  656.41
  600.14657.4012   609.4  663.31   643.3  666.49   663.2  672.56   687.9  672.33
   704.5   667.5   769.9  669.95   834.3  677.12   891.2  690.54   931.8  693.21
  1029.4  718.04  1061.9   723.2  1102.5  726.07  1122.8  730.55  1138.4  736.45
  1179.4  757.53  1224.5  783.56  1248.8  800.48    1261  802.84  1289.6  818.95
#Mann= 8, -1 ,  0
       0     0.1       0  268.06    0.06       0  360.99    0.05       0
   544.3   0.045       0  600.14    0.07       0  618.04    0.06       0
  927.11    0.05       0  977.11     0.1       0
Bank Sta=544.3,600.14
XS Rating Curve= 0 ,0
Exp/Cntr(USF)=0,0
Exp/Cntr=0.3,0.1

Type RM Length L Ch R = 1 ,18000   ,482.1,500.9,512.4
BEGIN DESCRIPTION:
Structure 4 XS 1
END DESCRIPTION:
XS GIS Cut Line= 6
1602334.40904443406700.1465434281602382.84562734406873.100921929
1602520.27087742407268.3885171711602544.28231233 407360.77645576
1602552.81149475   407447.907187  1602606.296624408271.563020006
#Sta/Elev= 30
       0  823.87    99.1  796.09   129.2  790.94     196  770.05   238.5  762.75
   319.3  736.32   378.5   723.2   543.2  694.54   618.9  693.95   693.3  685.86
   813.8  664.28   861.9  663.38     878   656.5   912.8   655.5  923.25656.4686
   982.2  676.28  1010.2   689.5  1098.4  697.33  1134.1  713.04  1153.7  727.38
  1194.6  737.96  1218.7  739.76  1274.2  756.66  1334.9   779.6  1394.6  791.49
  1439.1  805.67  1479.2  814.68  1524.2  835.66  1547.4  849.59  1606.5  873.73
#Mann= 9, -1 ,  0
       0     0.1       0  425.16    0.05       0  518.82     0.1       0
  528.82    0.05       0  831.13     0.1       0     878   0.045       0
  923.25     0.1       0 1026.13    0.06       0 1222.38     0.1       0
Bank Sta=878,923.25
XS Rating Curve= 0 ,0
Exp/Cntr(USF)=0,0
Exp/Cntr=0.3,0.1

Type RM Length L Ch R = 1 ,17499   ,492.5,499.1,504.5
XS GIS Cut Line= 6
1602317.79195167406692.9487231671602372.46014942407000.076717839
1602351.27285583407107.6184975061602076.51061009407467.939955339
1601964.26739626407586.7940483391601613.45313726407932.940337673
#Sta/Elev= 30
       0  824.82   101.4  796.24   117.7  794.82   292.2  735.07   446.7  698.04
   466.6  690.11   513.1  683.59   548.1  672.06   638.4  666.51   773.8   666.2
   804.3  654.55   809.4  653.97   841.3  654.61   875.5  666.34   917.9  673.53
   954.7  690.18   977.4  705.34  1052.1  724.02    1092  724.45  1111.4  743.15
  1127.3  766.75  1164.1  779.24  1184.1  791.85  1229.1  802.32  1268.7  828.77
  1312.6  843.35  1342.3  861.56  1418.6  883.93  1480.9  882.97  1531.1  913.76
#Mann= 10, -1 ,  0
       0     0.1       0  518.47    0.05       0  682.22     0.1       0
   804.3   0.045       0   841.3     0.1       0  844.72    0.08       0
  914.74     0.1       0  990.02    0.08       0 1048.25    0.06       0
 1193.01     0.1       0
Bank Sta=804.3,841.3
XS Rating Curve= 0 ,0
Exp/Cntr(USF)=0,0
Exp/Cntr=0.3,0.1

Type RM Length L Ch R = 1 ,17000   ,512,500,488
XS GIS Cut Line= 6
1602230.80196817406627.4655864241602175.63147484 406727.73900792
1601809.79493618407041.9263716791601330.03277235407444.926221833
1601259.05916101 407514.693798841601195.99202992407593.754336253
#Sta/Elev= 30
       0  825.74   114.4  809.82     231  779.68   265.8  765.28   302.4  758.77
   384.3  708.19   401.4  702.44   460.2  694.59   508.4  674.03   677.3   661.3
   690.6  655.24   694.1  654.13   747.4  655.39   762.5  660.35   829.7  665.74
   909.2  693.12   961.5  700.65   998.8  712.22  1039.8   711.8  1085.2  725.48
  1110.9  726.72    1137  737.36  1201.7  749.23  1237.2  762.77    1264  765.17
  1285.5  772.72  1308.3  785.99    1349  798.01  1381.4  822.54  1423.9  837.06
#Mann= 5, -1 ,  0
       0     0.1       0   690.6   0.045       0   747.4     0.1       0
  866.72    0.06       0 1144.84     0.1       0
Bank Sta=690.6,747.4
XS Rating Curve= 0 ,0
Exp/Cntr(USF)=0,0
Exp/Cntr=0.3,0.1

Type RM Length L Ch R = 1 ,16500   ,498.9,498.9,500.4
XS GIS Cut Line= 6
1601549.79315959406226.0749850121601521.75647026406322.381550923
1601493.40055583 406418.132343681601464.00461726406512.601314843
1601431.45481358406604.0479823351601034.92214209 407529.29744418
#Sta/Elev= 30
       0  860.11    77.6  849.75   244.6  818.77   379.7  780.81   420.4  760.69
   453.3  751.01   544.7   703.9   569.7  696.44   630.6  688.35   662.2  656.51
   668.7   652.5   679.6     652   712.9  652.42   731.8  653.41   757.9   659.8
   844.9  662.99   884.1  676.34   966.8  698.24  1010.3  701.07  1058.2  710.17
  1084.3  710.04  1106.6  718.36  1136.5  718.28    1198  740.09  1221.6  753.42
  1282.5  770.33  1301.9  784.23  1328.2  794.22  1380.2  827.73  1402.8  836.12
#Mann= 8, -1 ,  0
       0     0.1       0   668.7   0.045       0   712.9     0.1       0
  837.42    0.05       0  934.92    0.06       0  954.92    0.05       0
 1048.67    0.06       0 1155.54     0.1       0
Bank Sta=668.7,712.9
XS Rating Curve= 0 ,0
Exp/Cntr(USF)=0,0
Exp/Cntr=0.3,0.1

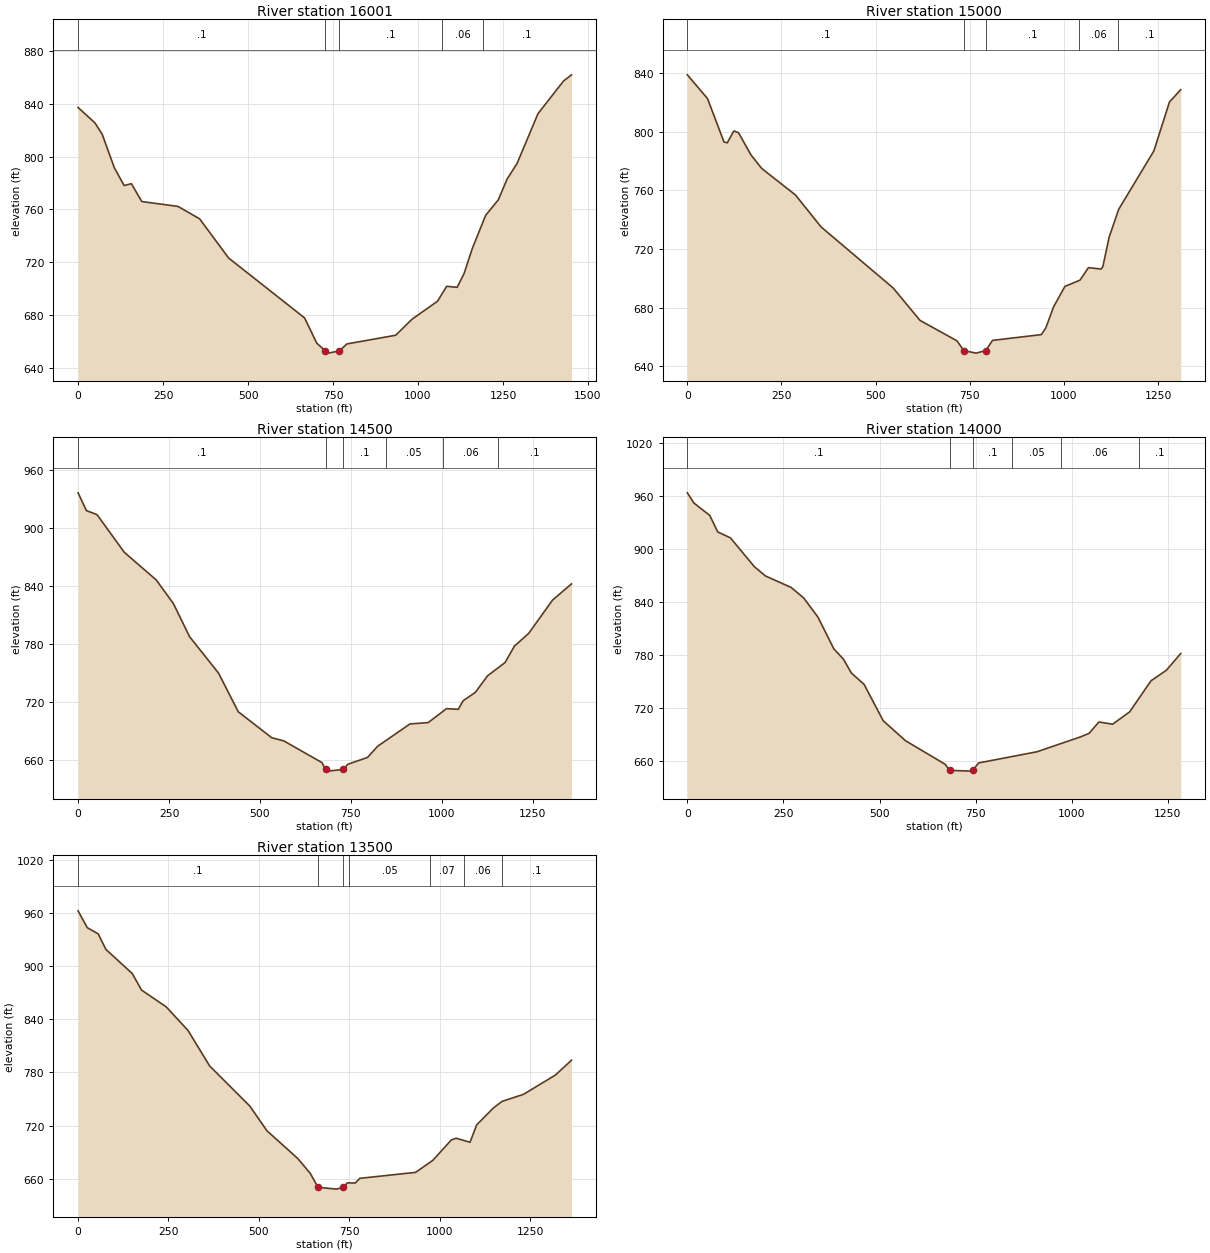
Type RM Length L Ch R = 1 ,16001   ,957.8,1001.1,1038.5
XS GIS Cut Line= 6
1601295.01118883406127.1430962531601188.86934076 406192.82111451
1601095.42694233406257.6838456691601032.07044175406335.761445418
1600831.48226026406742.0762495851600559.05301508407342.306676418
#Sta/Elev= 30
       0  837.21    49.6  825.54    71.1  816.82   106.9  791.38   135.5  778.07
   156.8  779.46   187.5  765.91   293.8  762.24   357.6  752.81   442.8  723.13
   666.4   677.7   702.1  658.58   726.7652.8798   736.5  651.02   768.5   652.7
   790.8  657.98   934.5  664.59   982.8  676.82  1057.3  690.32  1084.3  701.67
  1115.1  700.91  1135.5  711.34  1159.5  730.13    1199  755.47  1236.2  767.21
    1262  782.92  1291.5  794.81    1353  832.54  1428.1  857.27  1451.5  861.97
#Mann= 5, -1 ,  0
       0     0.1       0   726.7   0.045       0   768.5     0.1       0
 1071.89    0.06       0 1190.42     0.1       0
Bank Sta=726.7,768.5
XS Rating Curve= 0 ,0
Exp/Cntr(USF)=0,0
Exp/Cntr=0.3,0.1

Type RM Length L Ch R = 1 ,15000   ,522,500.5,479.9
XS GIS Cut Line= 6
1601282.49940284406109.2317147551601045.37848601406186.039632007
1600931.97418526406192.4723619221600840.62102151406158.559700087
1600292.45118609405885.3076219261600068.44978869405961.590769619
#Sta/Elev= 30
       0  838.89    53.6  822.69    97.4  793.01   106.1  792.48   123.3  800.53
   135.9  799.39   168.8  784.29   197.6  774.95   287.2  756.84   355.3  735.02
   546.5  693.39   617.8  671.25   715.9  657.31   734.1  650.63   766.9  648.91
   792.4  650.65   810.3  657.61     940  661.55   951.8   666.1   972.6  680.57
  1002.5  694.46  1042.6  698.73  1064.9  707.25  1099.1  706.32  1103.4  708.12
    1120   728.1  1145.6   747.2  1238.6  786.85  1280.2  820.35  1310.1  828.77
#Mann= 5, -1 ,  0
       0     0.1       0   734.1   0.045       0   792.4     0.1       0
 1039.66    0.06       0 1143.42     0.1       0
Bank Sta=734.1,792.4
XS Rating Curve= 0 ,0
Exp/Cntr(USF)=0,0
Exp/Cntr=0.3,0.1

Type RM Length L Ch R = 1 ,14500   ,498.5,499.5,499.2
XS GIS Cut Line= 6
1601226.11040801405337.6387697611601130.30088834405365.155775085
1601035.05239117405393.1032257531600507.38579559405552.990373179
 1600074.3905986405682.5606520921599962.43037045  405788.1855149
#Sta/Elev= 30
       0  936.07    22.9  917.72      52  913.61     127  874.69   214.6  846.25
   261.8   821.9   306.5  787.59   385.9  750.11   440.3  710.12   532.2  683.37
   565.7  680.02   670.2   657.7  680.33650.5865   686.9  648.86   728.7  650.61
   741.2   655.9   795.4  662.96   823.3  674.51   912.3  697.57   962.4  698.95
  1012.5  713.31  1045.1  712.67  1058.5  721.54  1091.9  730.11  1125.6  747.27
  1173.6  760.93  1199.3  777.86  1238.4  790.92  1304.2  825.39  1356.2  842.06
#Mann= 6, -1 ,  0
       0     0.1       0  680.33   0.045       0   728.7     0.1       0
  845.37    0.05       0 1002.94    0.06       0 1153.74     0.1       0
Bank Sta=680.33,728.7
XS Rating Curve= 0 ,0
Exp/Cntr(USF)=0,0
Exp/Cntr=0.3,0.1

Type RM Length L Ch R = 1 ,14000   ,525.5,500,464.2
XS GIS Cut Line= 6
1601136.56498343404871.2266448441600411.09793042405063.017599836
 1600256.3075576405113.2960425911600167.51114726405144.216912508
1600076.31021418405178.2680255031599966.44096127405319.537578226
#Sta/Elev= 30
       0  963.73      17  952.24    58.4  938.16    79.1  919.47   112.2  912.75
   174.2  880.25   203.2   869.7   269.8  856.75   302.5  844.88   339.7  823.18
   381.1  787.23   405.9  775.66   426.6  759.99     460  746.94   509.4  705.98
   567.3  683.39   670.7  656.68   682.1  649.78   736.9  648.92  741.97649.6574
   757.7  658.17   909.6  670.83  1022.5  687.62    1045   691.6  1070.6  704.51
  1106.3     702  1150.5  715.92  1206.1  751.09    1246  762.97  1283.5  782.02
#Mann= 6, -1 ,  0
       0     0.1       0   682.1   0.045       0  741.97     0.1       0
  845.46    0.05       0  973.15    0.06       0 1174.53     0.1       0
Bank Sta=682.1,741.97
XS Rating Curve= 0 ,0
Exp/Cntr(USF)=0,0
Exp/Cntr=0.3,0.1

Type RM Length L Ch R = 1 ,13500   ,538.8,500,473.4
XS GIS Cut Line= 6
1600377.63014959404040.6922166791600052.17935692404893.599631593
1600017.67286426404980.7756383421599979.31828217405069.828609839
1599943.22747509405189.4701028321599932.96663702405324.933434404
#Sta/Elev= 30
       0  962.36    25.5  943.31    55.5  936.43    76.9  918.82   149.7  891.62
   175.4  872.95   243.9  853.89   303.8  827.45   363.7  787.32   475.1  741.89
   522.2  714.13   607.8  682.69     642  666.05   663.4  650.36   714.8  648.24
   732.4  650.28   744.8  655.34   766.2   655.1     779  660.41   933.3  667.16
   980.6   680.6  1032.5  703.89  1045.6  705.69  1083.8  701.12  1102.2  720.75
  1148.2  739.72  1172.5  747.31  1231.7  755.21  1319.9  776.99  1364.4  793.72
#Mann= 7, -1 ,  0
       0     0.1       0   663.4   0.045       0   732.4     0.1       0
  750.39    0.05       0  972.89    0.07       0 1066.65    0.06       0
 1173.61     0.1       0
Bank Sta=663.4,732.4
XS Rating Curve= 0 ,0
Exp/Cntr(USF)=0,0
Exp/Cntr=0.3,0.1