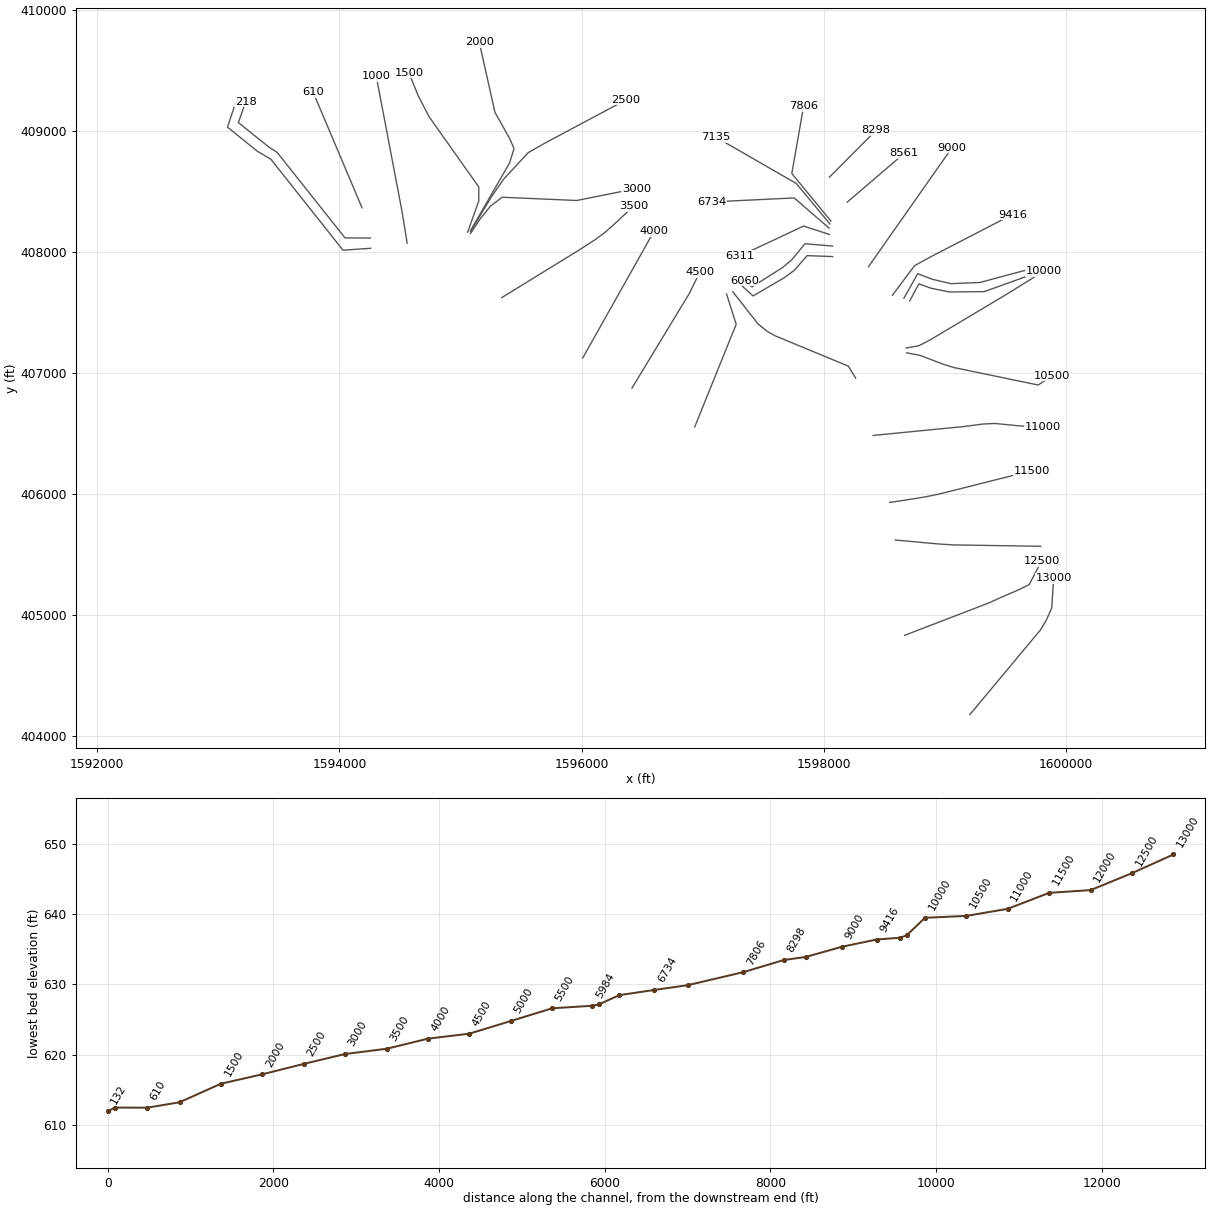
HEC-RAS study LTLFSHNGCK.prj: LTLFSHNGCK

--- LTLFSHNGCK.g01 (geometry) --- (continued)

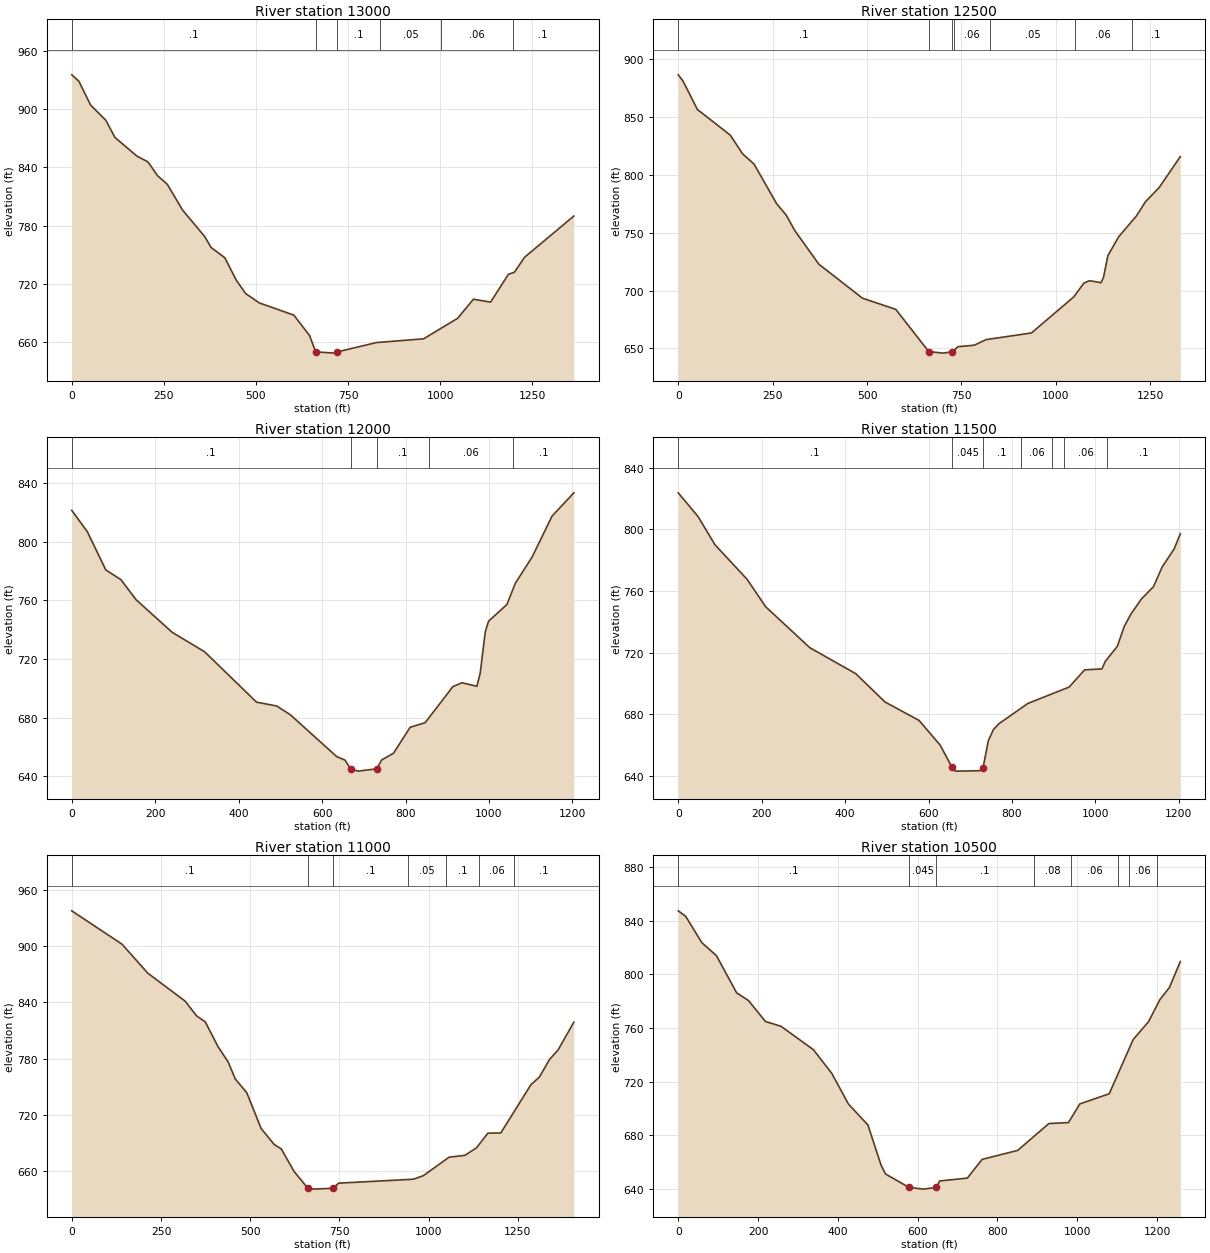
Type RM Length L Ch R = 1 ,13000   ,517.9,500.1,487.2
XS GIS Cut Line= 6
 1599206.2069675404173.6118983331599734.61076634404807.692979261
1599790.62902701404874.9106925871599840.47833675   404958.833425
1599883.21512793405055.9933356791599898.78751675405301.741627298
#Sta/Elev= 30
       0  935.43    19.4  928.78    50.7   904.5    92.3  888.67     117  870.96
   176.7  851.67   206.9  845.61   232.9  831.41   259.2  822.63   300.6  796.06
   361.3  768.51   377.9  757.54   415.4  746.84   446.5  723.73     472  709.93
     509  700.25   602.7  687.68   645.3  666.71   662.3  649.74   713.5  648.46
  720.75  649.74   827.1  659.35     955  663.22  1047.3  684.35  1090.4  704.06
  1136.9  701.07  1185.3  729.76  1201.4   731.8  1229.4  747.39  1362.9  789.82
#Mann= 6, -1 ,  0
       0     0.1       0   662.3   0.045       0  720.75     0.1       0
  835.39    0.05       0 1002.89    0.06       0 1196.65     0.1       0
Bank Sta=662.3,720.75
XS Rating Curve= 0 ,0
Exp/Cntr(USF)=0,0
Exp/Cntr=0.3,0.1

Type RM Length L Ch R = 1 ,12500   ,512.7,499.9,489
XS GIS Cut Line= 6
1598668.75430226404829.7834862621599369.07868901405099.286556169
1599437.22815901405131.0243535941599606.61659975405204.431359008
1599696.79227242405248.4939349291599799.09036451405442.147477945
#Sta/Elev= 30
       0   886.7    12.2  881.59    50.7  856.74   137.8  834.48   170.7  818.23
   200.7  809.49   260.7  775.08   286.5  765.04   308.5  751.96   372.2  722.84
   487.9  693.35     576   683.7   663.6   647.1   702.2   645.8  725.74647.0584
   740.8  651.36   783.7  652.64   815.5  657.51   935.5  663.26  1047.5   694.5
  1074.2  706.41  1089.1  708.53  1119.6  706.79  1126.2  711.34  1137.7   730.1
  1166.3  746.47  1213.7  764.68  1237.5  776.89  1273.5  789.08  1329.6   815.9
#Mann= 7, -1 ,  0
       0     0.1       0   663.6   0.045       0  725.74     0.1       0
  730.39    0.06       0  825.57    0.05       0 1050.18    0.06       0
 1200.55     0.1       0
Bank Sta=663.6,725.74
XS Rating Curve= 0 ,0
Exp/Cntr(USF)=0,0
Exp/Cntr=0.3,0.1

Type RM Length L Ch R = 1 ,12000   ,489.3,500,507
XS GIS Cut Line= 6
1598590.83746333405616.8147205861598690.55215892405608.144134253
1598887.99959867405589.7383311691598984.76580934 405581.92108959
1599078.44409968405576.5506935121599792.42233051405565.568760082
#Sta/Elev= 30
       0  821.44    37.4  806.81    81.6  780.75   117.7  774.17   153.9  760.49
   240.7  738.18   318.6  724.84   442.9  690.47     491  687.88   523.5  681.97
     635  653.31     655   650.9  668.17645.0032     686  643.39     731  644.95
     743  651.07     771  655.55     811  673.31     847  676.46   913.5  701.09
     935  703.73     971  701.33     979  710.33     991  738.36     999  745.76
    1043  757.17    1063  771.57  1103.1  789.44  1151.1  817.46  1203.4  833.41
#Mann= 5, -1 ,  0
       0     0.1       0  668.17   0.045       0     731     0.1       0
  856.81    0.06       0 1058.06     0.1       0
Bank Sta=668.17,731
XS Rating Curve= 0 ,0
Exp/Cntr(USF)=0,0
Exp/Cntr=0.3,0.1

Type RM Length L Ch R = 1 ,11500   ,505.3,500,494.9
XS GIS Cut Line= 6
1598545.00454976405927.5161989181598742.49890542405957.523028672
1598839.87075792405973.9829695081598934.99064642405992.978338346
1599026.12202585406015.0032286791599718.43297717406189.904453665
#Sta/Elev= 30
       0  823.77    47.6  808.32    88.1  790.03     165   767.6   209.5  749.79
   315.1  723.23   425.5  706.29   495.4  687.94   577.2  675.92   627.5     660
   656.4  645.38   664.6     643   722.4  643.25   730.6   645.1     743   662.6
   755.4  670.01   768.8  673.84     838  686.97   936.9   697.6     974  708.79
  1015.3  709.38  1023.5  714.32  1052.4  724.08  1068.9  736.97  1085.4   745.2
  1110.2  754.87  1139.1  762.83  1159.7  775.53  1188.6  787.36  1203.3  797.19
#Mann= 7, -1 ,  0
       0     0.1       0   656.4   0.045       0   730.6     0.1       0
  821.77    0.06       0  896.77     0.1       0  924.27    0.06       0
 1028.02     0.1       0
Bank Sta=656.4,730.6
XS Rating Curve= 0 ,0
Exp/Cntr(USF)=0,0
Exp/Cntr=0.3,0.1

Type RM Length L Ch R = 1 ,11000   ,509.6,500,488.7
XS GIS Cut Line= 6
1598408.01466626406481.327427253 1599154.8251805406554.541191593
1599316.05451684406575.4496143461599410.99264717406580.366599262
1599621.99977109406559.8305510881599808.47061335406551.880919273
#Sta/Elev= 30
       0  937.87   140.8  902.25   213.1  871.27   317.6  841.48   349.8  825.64
   373.9  819.42   410.1  792.65   438.2  776.46   458.3  758.27   490.4  743.61
   530.6  705.42   566.8  688.53   586.9  683.68   623.1  659.49   661.6641.6566
   675.3  640.73   731.6  641.61   747.7   647.1   957.1  651.31   985.1  655.12
  1057.3  674.88  1101.5  676.81  1133.7  684.74  1165.9   700.5  1202.1  700.69
  1286.2   752.1  1310.3  760.46  1338.3  779.03  1362.3  789.23  1406.7  818.95
#Mann= 7, -1 ,  0
       0     0.1       0   661.6   0.045       0   731.6     0.1       0
  942.98    0.05       0 1048.05     0.1       0 1141.88    0.06       0
 1240.07     0.1       0
Bank Sta=661.6,731.6
XS Rating Curve= 0 ,0
Exp/Cntr(USF)=0,0
Exp/Cntr=0.3,0.1

Type RM Length L Ch R = 1 ,10500   ,466.3,500,519.2
XS GIS Cut Line= 6
1598685.87106593407163.8444349171598794.42170183407143.318885416
1598982.34750709407071.3738193361599072.18623817407042.872892082
1599771.38004975406897.912880167 1599886.7725355406973.746718004
#Sta/Elev= 30
       0   847.4    18.6  843.33    59.3   823.6    95.9  813.89   146.3  786.21
     176  780.46   218.6   764.8   257.5  761.24   338.8  743.76   384.9  726.06
   426.4  703.25   475.4  687.57   508.1  657.77   519.4  651.03577.5447641.1229
   613.5  639.72646.9447640.9459   655.1  645.81   724.6  647.97   761.4  661.91
   850.5   668.6   928.8  688.66   977.8   689.4  1006.4  703.31    1080  710.88
  1140.1  751.41  1178.4  764.63  1207.1  781.22    1231  790.27  1258.1  809.56
#Mann= 8, -1 ,  0
       0     0.1       0577.5447   0.045       0646.9447     0.1       0
  890.99    0.08       0  984.74    0.06       0 1101.62     0.1       0
 1130.06    0.06       0 1200.06     0.1       0
Bank Sta=577.5447,646.9447
XS Rating Curve= 0 ,0
Exp/Cntr(USF)=0,0
Exp/Cntr=0.3,0.1

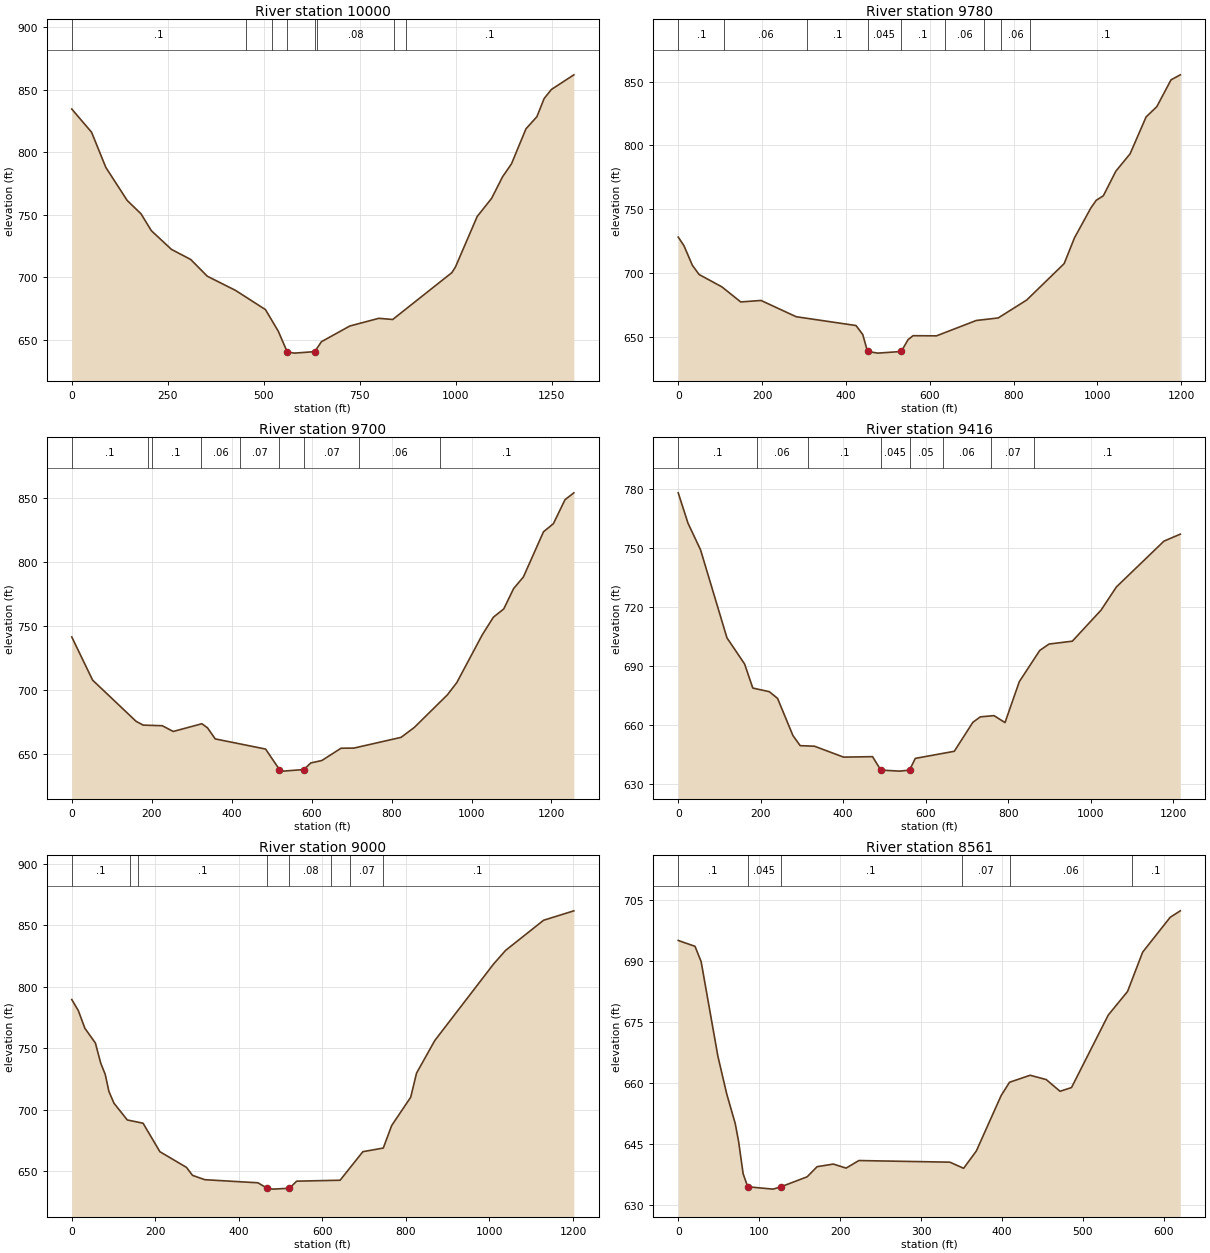
Type RM Length L Ch R = 1 ,10000   ,244,219.9,202
BEGIN DESCRIPTION:
Structure 3 XS 4
END DESCRIPTION:
XS GIS Cut Line= 6
1598681.51575968407203.5832005891598785.71108934407222.796088666
1598873.68368243407267.4688995931599482.90851384 407630.86679484
1599649.16703959407733.4020228391599817.62634835407839.109488592
#Sta/Elev= 30
       0  834.56    51.5  816.07    88.9  787.82   144.5  761.46   180.4  750.82
   207.4  737.31   259.7  722.37   309.9  714.31     353  700.95   426.4  689.65
   504.7  674.25   538.1  656.97   561.4   640.4   580.1  639.45   633.1  640.65
   650.6   648.6   724.4  661.12   800.1  667.28   836.2  666.34   990.4  703.79
   999.8  708.34  1056.3  748.64    1094  763.19  1122.4  780.36  1145.7  790.76
  1183.4  818.73  1211.9  828.42  1230.8  842.95  1249.7  850.19  1308.2   861.9
#Mann= 8, -1 ,  0
       0     0.1       0  455.24    0.08       0  522.74     0.1       0
   561.4   0.045       0   633.1     0.1       0  637.74    0.08       0
  840.24    0.07       0  870.24     0.1       0
Bank Sta=561.4,633.1
XS Rating Curve= 0 ,0
Exp/Cntr(USF)=0,0
Exp/Cntr=0.3,0.1

Type RM Length L Ch R = 1 ,9780    ,71,80.3,82
BEGIN DESCRIPTION:
Structure 3 XS 3
END DESCRIPTION:
XS GIS Cut Line= 6
1598710.27875307407592.602844764 1598785.8398013407733.929990523
 1598886.5878656 407697.548745081599039.10924073407666.764614321
1599325.96136826407669.5631716621599784.92477231407834.678054827
#Sta/Elev= 30
       0  728.02    13.5  721.38    33.8  705.86    49.8  698.68   104.2  688.95
   149.1  677.13   197.5   678.3   281.3  665.53   424.1  658.62   440.1  651.61
  451.58 638.298   476.1  636.96   532.1  638.26   548.1  647.46   560.1  650.64
   616.1  650.52   710.9  662.57   763.3  664.57   831.3  678.64   920.6  707.22
   945.3  727.47   984.3   750.9   997.1  756.91  1014.1  760.46  1043.9  779.75
  1077.9  793.39  1116.1  822.35  1141.6  830.39  1175.6  851.47  1197.7  855.38
#Mann= 9, -1 ,  0
       0     0.1       0     110    0.06       0  307.37     0.1       0
  451.58   0.045       0   532.1     0.1       0  635.38    0.06       0
  729.99    0.07       0  769.99    0.06       0  839.99     0.1       0
Bank Sta=451.58,532.1
XS Rating Curve= 0 ,0
Exp/Cntr(USF)=0,0
Exp/Cntr=0.3,0.1

Type RM Length L Ch R = 1 ,9700    ,273.9,284,298.4
BEGIN DESCRIPTION:
Structure 3 XS 2
END DESCRIPTION:
XS GIS Cut Line= 6
1598662.70327826407614.991303498 1598776.0448506407817.886710776
 1598896.3828163407771.710514637 1599050.3034701407735.329269194
1599290.97940149 407745.124219891599769.53270693407873.857857611
#Sta/Elev= 30
       0  741.27    52.2  707.58   160.9  675.46   178.6  672.51   226.3  672.04
   253.9  667.56   325.5  673.57   339.6  670.37     359  661.74   484.9  653.83
   519.6   637.8   529.4  636.62  580.74637.8663   597.8  642.97   625.6  644.91
   673.6  654.48   705.6  654.58   823.8  662.96   856.9  670.68   939.8  696.17
   963.3  705.72  1026.7  742.82  1054.7  756.66  1080.6  763.11  1105.4  779.03
  1129.8  788.06    1180  823.26  1204.9  829.66  1233.9  848.33    1256  853.68
#Mann= 9, -1 ,  0
       0     0.1       0     190    0.06       0     200     0.1       0
  322.41    0.06       0   421.3    0.07       0   519.6   0.045       0
  580.74    0.07       0  719.29    0.06       0  920.47     0.1       0
Bank Sta=519.6,580.74
XS Rating Curve= 0 ,0
Exp/Cntr(USF)=0,0
Exp/Cntr=0.3,0.1

Type RM Length L Ch R = 1 ,9416    ,400.2,415.8,431
BEGIN DESCRIPTION:
Structure 3 XS 1
END DESCRIPTION:
XS GIS Cut Line= 6
1598567.75619674407639.6596814021598749.92725762407883.520979794
1598826.47926987407925.974306972 1598892.4528912407961.672070222
1599382.23636045408215.3123109661599558.79440628408306.744542794
#Sta/Elev= 30
       0   777.9    23.7  762.44    54.1  748.91   118.1  704.16   160.9  690.86
   180.8  678.61   220.8  676.77   240.8  673.37   278.1  654.46   295.7  649.31
   330.3  649.03   400.9  643.48   471.1  643.72  491.22636.8912   537.1  636.36
   560.8  636.88   574.7  642.83   669.3  646.45   714.3  661.18   732.3  663.95
   765.6  664.59   792.3  661.05   826.9  681.85   876.5  697.74     899  700.99
   955.5  702.45  1025.1  718.23  1062.4  730.05  1177.7  753.34  1217.3  756.88
#Mann= 8, -1 ,  0
       0     0.1       0     190    0.06       0  314.39     0.1       0
  491.22   0.045       0   560.8    0.05       0  641.94    0.06       0
  759.44    0.07       0  863.19     0.1       0
Bank Sta=491.22,560.8
XS Rating Curve= 0 ,0
Exp/Cntr(USF)=0,0
Exp/Cntr=0.3,0.1

Type RM Length L Ch R = 1 ,9000    ,441.7,439.1,435
XS GIS Cut Line= 6
1598370.08363976407875.7642709171598426.61502276407956.350723922
1598629.40726809408245.4397126731598780.15598235408460.337576836
1598889.62853242408616.3940232551599060.34242985408859.753116593
#Sta/Elev= 30
       0  789.46    15.6  780.55    31.4  766.12    56.6  754.08    69.3  737.79
    80.2  728.52    88.9   714.8     101  705.22   132.9  691.58   170.7  688.91
     211  665.76   274.6  653.02   289.1  646.53   318.5  643.01   445.6  640.49
   468.3635.9961   481.6  635.34  521.12636.0524   538.4  641.81   642.4  642.57
   696.9  665.78   745.8  668.74   765.9  687.05   811.5  710.09   825.4  729.65
   869.2   756.2    1010  818.42  1038.7  829.45  1129.6  853.93    1202  861.59
#Mann= 8, -1 ,  0
       0     0.1       0  138.44    0.06       0  158.44     0.1       0
   468.3   0.045       0  521.12    0.08       0  621.56     0.1       0
  666.56    0.07       0  744.06     0.1       0
Bank Sta=468.3,521.12
XS Rating Curve= 0 ,0
Exp/Cntr(USF)=0,0
Exp/Cntr=0.3,0.1

Type RM Length L Ch R = 1 ,8561    ,260.7,262.5,265.9
XS GIS Cut Line= 2
1598194.61885437408408.8778514881598665.55031454408812.533388785
#Sta/Elev= 30
       0  695.13    20.7  693.69    28.3  689.92      49  666.61    59.9  657.34
    70.5  649.97    74.6  645.59    80.2  637.65    85.9  634.46   117.1  633.88
  126.65634.4338   159.3  636.92   171.6  639.41   191.6  640.05   207.4  639.06
   223.2  640.92   335.6  640.52   352.6  639.01   368.3  643.28     399  656.95
   409.3   660.2   434.8  661.93   454.7  660.86   471.7  657.98   485.9   658.9
   531.3  676.76   555.1  682.56   573.8  692.26   607.8  700.84   620.3  702.43
#Mann= 6, -1 ,  0
       0     0.1       0    85.9   0.045       0  126.65     0.1       0
     350    0.07       0     410    0.06       0     560     0.1       0
Bank Sta=85.9,126.65
XS Rating Curve= 0 ,0
Exp/Cntr(USF)=0,0
Exp/Cntr=0.3,0.1

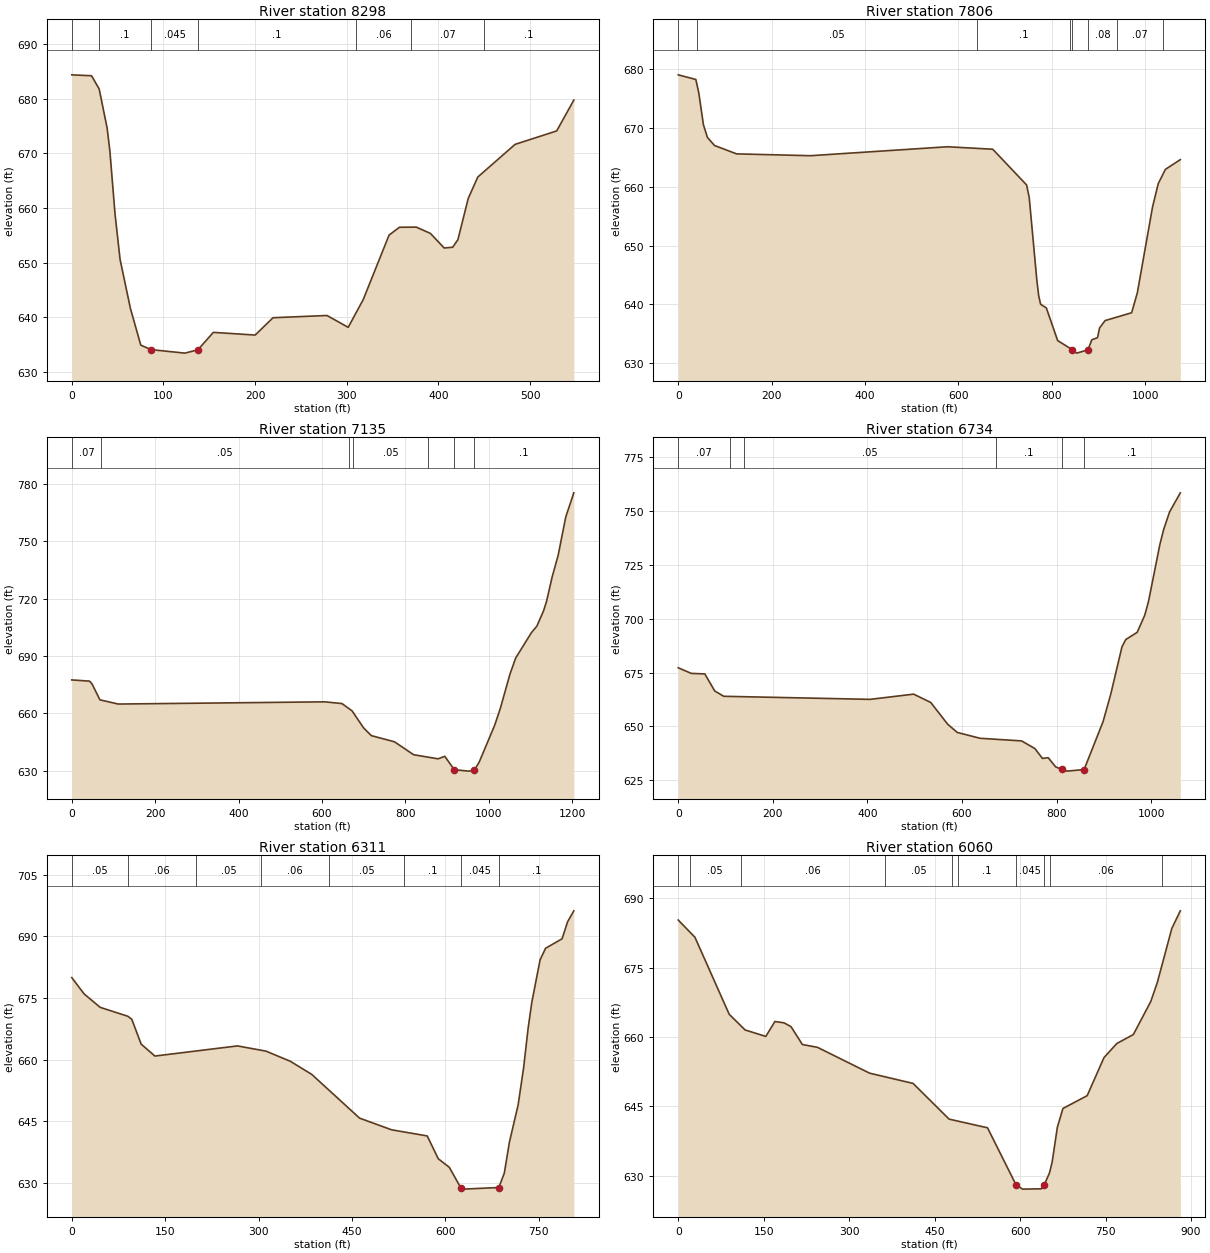
Type RM Length L Ch R = 1 ,8298    ,481.6,492.7,502
XS GIS Cut Line= 2
1598047.04586224408615.0460022581598433.33987105409003.510202129
#Sta/Elev= 30
       0   684.4    21.6  684.23    29.9  681.81    38.6  674.65    41.6  670.43
    47.2  658.92    52.7  650.61      64  641.63    75.3  634.91    86.6  634.09
   123.4  633.45   137.6  634.06   154.5  637.25   200.1  636.76   219.6  639.93
   278.5  640.34   301.6  638.17     318  643.25   346.2  655.06   357.5  656.49
   375.9  656.52   391.3  655.37   406.3   652.7   415.6  652.83   421.3  654.22
   432.6  661.78     443  665.69   483.7  671.67   529.1  674.13   547.8  679.78
#Mann= 7, -1 ,  0
       0    0.05       0      30     0.1       0    86.6   0.045       0
   137.6     0.1       0     310    0.06       0     370    0.07       0
     450     0.1       0
Bank Sta=86.6,137.6
XS Rating Curve= 0 ,0
Exp/Cntr(USF)=0,0
Exp/Cntr=0.3,0.1

Type RM Length L Ch R = 1 ,7806    ,643.9,670.5,694.7
XS GIS Cut Line= 3
 1598060.0670086408252.6240951161597736.70854055408645.428677108
1597834.36713828409203.167779717
#Sta/Elev= 30
       0     679    37.7  678.21      44  675.94    53.9  670.54    62.4  668.38
    77.6     667   124.9  665.57   283.1  665.26   576.9  666.78   673.4  666.36
   745.9  660.29   751.5  658.16   767.8  644.13   771.8  641.48   775.9  640.02
   788.1  639.41   812.4  633.85   843.8632.2994     853  631.72   877.3  632.27
   885.5  633.99   897.7  634.34   902.2  636.01     914  637.25   970.8  638.58
     983  641.97  1015.5  656.53  1027.7   660.5  1043.1  662.94    1075  664.59
#Mann= 8, -1 ,  0
       0    0.07       0      40    0.05       0  638.78     0.1       0
  838.78    0.08       0   843.8   0.045       0   877.3    0.08       0
  938.78    0.07       0 1038.78    0.06       0
Bank Sta=843.8,877.3
XS Rating Curve= 0 ,0
Exp/Cntr(USF)=0,0
Exp/Cntr=0.3,0.1

Type RM Length L Ch R = 1 ,7135    ,388.3,401.2,415.7
XS GIS Cut Line= 3
1598051.38624436408228.7519934481597773.60178858  408562.9614168
1597107.35313294 408947.08523455
#Sta/Elev= 30
       0  677.55    42.7  676.92    48.9  675.32    67.5  667.14   111.5  664.94
   606.7  666.09   647.7  665.19   671.8  661.41   699.5   652.5   717.9  648.44
   773.6   645.2   819.5  638.44   878.2  636.29   894.2  637.61   917.1  630.58
   952.3  629.86  965.35630.4968   976.5  634.47  1013.8  653.83  1027.3  662.62
  1050.4  680.53  1064.2     689  1101.6  702.18    1115  705.71  1130.9  713.62
  1138.1  718.57  1151.4  731.22  1166.1  742.83  1184.3  762.84  1203.6  775.39
#Mann= 7, -1 ,  0
       0    0.07       0      70    0.05       0  664.58     0.1       0
  674.58    0.05       0  854.58     0.1       0   917.1   0.045       0
  965.35     0.1       0
Bank Sta=917.1,965.35
XS Rating Curve= 0 ,0
Exp/Cntr(USF)=0,0
Exp/Cntr=0.3,0.1

Type RM Length L Ch R = 1 ,6734    ,413.7,422.9,433.2
XS GIS Cut Line= 3
1598044.87567117408194.028936476 1597756.2402601 408443.60090846
1597076.97045809408411.048042549
#Sta/Elev= 30
       0  677.22    27.4  674.62    56.2  674.36    77.2  666.44    96.2  663.97
   405.7  662.54   497.8  664.97   533.9   661.1   569.9  650.95   589.9  647.18
     638  644.46   726.1  643.23   754.1  639.68   770.1  635.09   782.2  635.43
   798.2  631.14  811.09 629.972   822.2  629.19   858.2  629.93   898.3   652.2
   914.3  664.75   938.3  687.01   946.3  690.34   970.4  693.69   986.4  701.64
   994.4  708.08  1018.4  734.52  1026.4  741.49  1038.8  749.59  1061.6  758.52
#Mann= 6, -1 ,  0
       0    0.07       0     110    0.06       0     140    0.05       0
  671.57     0.1       0  811.09   0.045       0   858.2     0.1       0
Bank Sta=811.09,858.2
XS Rating Curve= 0 ,0
Exp/Cntr(USF)=0,0
Exp/Cntr=0.3,0.1

Type RM Length L Ch R = 1 ,6311    ,248.3,250.8,254.8
BEGIN DESCRIPTION:
Structure 2 XS 4
END DESCRIPTION:
XS GIS Cut Line= 3
1598047.04586224408141.9443510181597834.36713828408211.390464962
1597307.01071053407963.988684038
#Sta/Elev= 30
       0  679.95    19.9  675.97    45.6  672.71      90  670.54    96.4   669.8
   111.4  663.76   133.5  660.85     266  663.32   311.8  662.05   350.9  659.58
   385.3  656.39   462.1  645.74   513.4   642.9   570.8   641.4   588.5  635.84
   606.2  633.77   624.5  628.82   628.3  628.45   685.7  628.84   694.6  632.37
   702.7  639.86   716.7  648.91   725.5  657.94   732.8  667.64   738.7  673.93
     752  684.27   760.8  687.09   787.3   689.4   796.2  693.55   806.2  696.21
#Mann= 8, -1 ,  0
       0    0.05       0      90    0.06       0     200    0.05       0
  303.73    0.06       0  413.73    0.05       0  533.73     0.1       0
   624.5   0.045       0   685.7     0.1       0
Bank Sta=624.5,685.7
XS Rating Curve= 0 ,0
Exp/Cntr(USF)=0,0
Exp/Cntr=0.3,0.1

Type RM Length L Ch R = 1 ,6060    ,76.8,75.9,74.8
BEGIN DESCRIPTION:
Structure 2 XS 3
END DESCRIPTION:
XS GIS Cut Line= 6
 1598073.2919822408046.0035575751597845.43855088 408065.23570567
1597736.16023959407932.3207221881597658.88722959407867.734325768
1597407.69976862407709.0144381261597343.97395952407761.397389152
#Sta/Elev= 30
       0  685.29    29.3  681.57    89.5  664.91   117.5  661.52   153.7  660.13
   169.7  663.36   185.8  663.06   197.9  662.25   217.9  658.38   244.4  657.77
   335.8  652.19   412.2  649.97   475.4  642.25   542.8  640.38   592.9  628.05
   604.3  627.12   637.4  627.19   642.4  628.06   651.6  630.61   656.3  632.98
   665.4   640.5   675.2  644.55   717.8  647.33   747.2  655.55   769.8   658.6
   798.8  660.54   829.4  667.69   840.8  671.77   866.3  683.47   881.2  687.28
#Mann= 10, -1 ,  0
       0     0.1       0      20    0.05       0     110    0.06       0
  362.72    0.05       0  480.91    0.06       0  490.91     0.1       0
   592.9   0.045       0   642.4     0.1       0  651.62    0.06       0
  848.76    0.05       0
Bank Sta=592.9,642.4
XS Rating Curve= 0 ,0
Exp/Cntr(USF)=0,0
Exp/Cntr=0.8,0.6

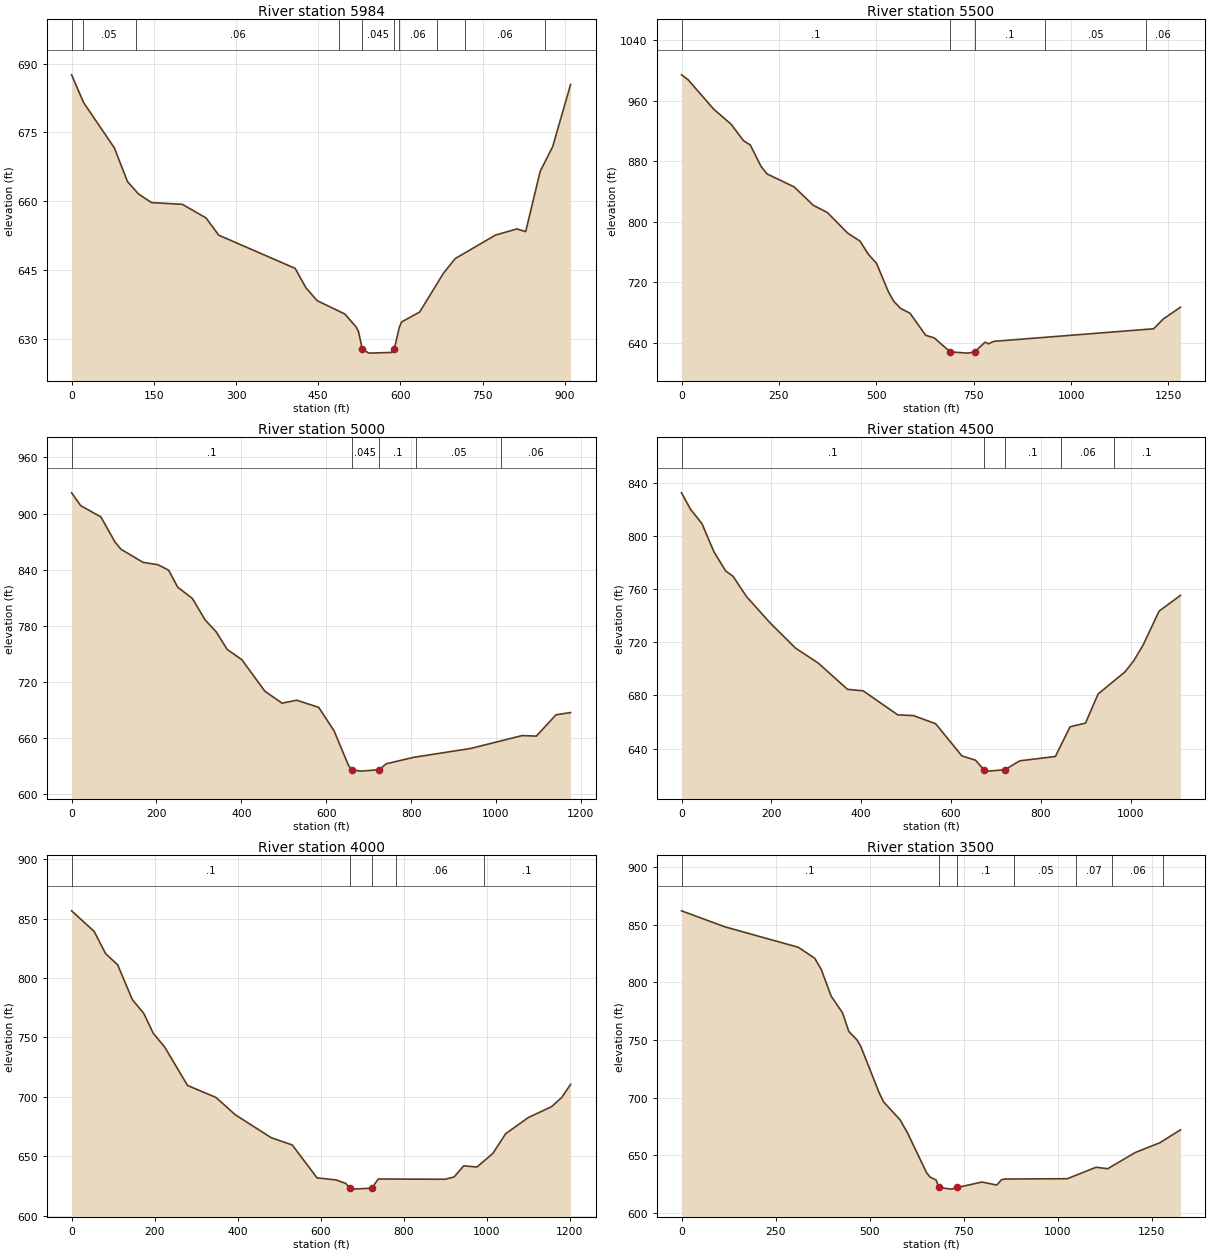
Type RM Length L Ch R = 1 ,5984    ,508.5,484.4,452.5
BEGIN DESCRIPTION:
Structure 2 XS 2
END DESCRIPTION:
XS GIS Cut Line= 6
1598074.02126189407959.288081014 1597863.4677582407966.986944034
1597756.49610392 407844.451917121597672.30312287407783.325506222
1597416.50234787 407633.832246641597315.87002653407726.581695429
#Sta/Elev= 30
       0  687.56    21.9  681.51      78  671.65     102   664.3     122  661.62
     146  659.72     202  659.36   245.3  656.39   268.6  652.63     408   645.4
   427.7  641.17     448  638.38   498.8  635.45   519.4  632.61   523.5  631.68
   530.5  627.82   542.5  626.94   584.2  627.09   588.9  627.84   598.1  632.59
   602.4  633.75   635.2  635.89   678.5  644.32   700.1  647.54   773.7  652.66
   812.7  653.99   828.7  653.41   855.2  666.55   878.1  671.95   910.6  685.45
#Mann= 10, -1 ,  0
       0     0.1       0      20    0.05       0  117.47    0.06       0
  487.45    0.07       0   530.5   0.045       0   588.9    0.07       0
  597.45    0.06       0  667.45    0.05       0  717.45    0.06       0
  863.73    0.05       0
Bank Sta=530.5,588.9
XS Rating Curve= 0 ,0
Exp/Cntr(USF)=0,0
Exp/Cntr=0.3,0.1

Type RM Length L Ch R = 1 ,5500    ,548.7,500,450
BEGIN DESCRIPTION:
Structure 2 XS 1
END DESCRIPTION:
XS GIS Cut Line= 6
1598264.56055684 406954.39078559 1598202.9963755407054.053644001
1597601.84337834407303.3146284221597535.22310476407340.316194832
1597458.99195801407401.380705252 1597249.5755787407668.113479302
#Sta/Elev= 30
       0  994.03    16.1  987.98    82.5  948.79   127.4  928.77   159.2  907.02
   176.6  901.39   203.9  873.41   219.2  863.27   289.1  846.09   338.6  821.64
   374.3  812.32   426.5  785.07   458.2  774.51   479.7  757.08   500.8   744.9
   530.9  707.82   544.6  695.25     562  685.77   586.5  679.28   626.9   650.1
   648.6  646.75  690.02628.1896   735.2  626.58   752.5  628.19   779.1  641.02
   788.2  638.87   801.9  642.15    1212  658.72  1236.7  671.59  1280.9  687.24
#Mann= 5, -1 ,  0
       0     0.1       0  690.02   0.045       0   752.5     0.1       0
  934.13    0.05       0  1191.8    0.06       0
Bank Sta=690.02,752.5
XS Rating Curve= 0 ,0
Exp/Cntr(USF)=0,0
Exp/Cntr=0.3,0.1

Type RM Length L Ch R = 1 ,5000    ,506.9,500,495.6
XS GIS Cut Line= 6
1596935.21118142406552.5874553321597178.58503851407155.727981344
1597215.99703717407248.4646725061597244.06194167 407318.01604259
  1597277.512006 407398.873492421597197.89904179407649.281325301
#Sta/Elev= 30
       0  922.11    21.5  908.41      69  896.36   102.1  869.66   116.4  861.81
   168.2  847.84   203.5   845.3   228.6  839.43   250.1  821.27   284.6  809.23
   314.8  786.21   340.7  773.58   366.6   754.8   401.1  743.84   455.5  710.11
     496  697.36   530.5  700.55   582.3  692.87   618.4  667.89   652.2  631.16
   659.9  626.19   681.5  624.77   724.6  626.33   741.3  632.61   806.5  639.55
   940.8  649.03  1061.8  662.77  1095.1  662.16  1141.4  684.97  1175.7  687.33
#Mann= 5, -1 ,  0
       0     0.1       0   659.9   0.045       0   724.6     0.1       0
  810.39    0.05       0 1012.89    0.06       0
Bank Sta=659.9,724.6
XS Rating Curve= 0 ,0
Exp/Cntr(USF)=0,0
Exp/Cntr=0.3,0.1

Type RM Length L Ch R = 1 ,4500    ,499,500,500.7
XS GIS Cut Line= 6
1596416.59673309406872.4792039991596753.52092801407428.797645167
1596805.32397401407514.3335633431596844.17658658407578.485337928
1596889.50457992 407653.329676421596977.13353868  407831.1780744
#Sta/Elev= 30
       0  832.66    20.1   820.3    45.4   809.5    72.5  788.06    98.3  773.81
   114.9  769.71     145  754.36   197.7  734.53   253.9  715.65     304  704.52
   369.7   684.6   404.5  683.48   481.7  665.34   516.4  664.84   565.9  658.69
   624.5  634.41   654.8  631.23   673.5  623.91   682.8  622.97  720.32624.0078
     753  630.72   832.7  634.01   865.2  656.36   899.7  659.16   927.8  681.11
   987.8  697.78  1006.9  705.99  1027.8  717.82  1063.6  743.54  1111.2   755.4
#Mann= 5, -1 ,  0
       0     0.1       0   673.5   0.045       0  720.32     0.1       0
  845.39    0.06       0  962.89     0.1       0
Bank Sta=673.5,720.32
XS Rating Curve= 0 ,0
Exp/Cntr(USF)=0,0
Exp/Cntr=0.3,0.1

Type RM Length L Ch R = 1 ,4000    ,507,500,481.7
XS GIS Cut Line= 6
1596009.81933142407121.0541661681596107.20463534 407294.39994809
1596155.41943392407380.2209706751596414.09345725407840.659682333
1596456.95065501407916.9456190021596598.53272092408168.960534915
#Sta/Elev= 30
       0  856.46    54.2  839.21      82  820.39   110.9  811.08   146.2   781.8
   173.8  770.16   196.7  753.41   224.2  741.83   279.3  709.52   348.1  699.35
   394.1  684.88   481.1   665.5   531.6  659.41   591.3  631.72   637.1  630.01
   660.1  627.14   671.1  623.01     677  622.26   723.4  623.09   738.7  630.77
   900.2  630.58   921.6  632.53   944.5  641.85   976.6  640.88  1014.8  652.33
  1045.5  668.83    1100  682.48  1156.2  691.65  1180.7  699.37    1202   710.4
#Mann= 5, -1 ,  0
       0     0.1       0   671.1   0.045       0   723.4     0.1       0
  780.39    0.06       0  992.89     0.1       0
Bank Sta=671.1,723.4
XS Rating Curve= 0 ,0
Exp/Cntr(USF)=0,0
Exp/Cntr=0.3,0.1

Type RM Length L Ch R = 1 ,3500    ,518.8,499.9,483.7
XS GIS Cut Line= 6
1595341.14514384407620.1378136721595980.22129351408013.415898502
1596116.64490518408101.8743830031596194.65295126408159.727613762
1596272.36178534408228.6421740951596427.76009659   408374.212421
#Sta/Elev= 30
       0  861.95   115.2   848.1   310.6  830.36   354.3  820.86   371.7  811.15
   397.9  788.09   428.2  773.54     445  757.38   466.3  750.26   476.4  744.75
   524.8  704.95   537.4   696.4   581.2   680.9   601.4  669.27   651.6  635.09
     661   631.3     677  628.76   684.5  622.31   717.7  620.82  733.71622.2543
     799  626.96   838.3  624.35   851.1  628.97     860  629.57  1025.9  629.85
  1102.4  639.75  1133.5  638.52  1206.4  652.49  1272.1     661  1326.9  672.19
#Mann= 7, -1 ,  0
       0     0.1       0   684.5   0.045       0  733.71     0.1       0
  885.39    0.05       0 1050.11    0.07       0 1143.98    0.06       0
 1280.44     0.1       0
Bank Sta=684.5,733.71
XS Rating Curve= 0 ,0
Exp/Cntr(USF)=0,0
Exp/Cntr=0.3,0.1

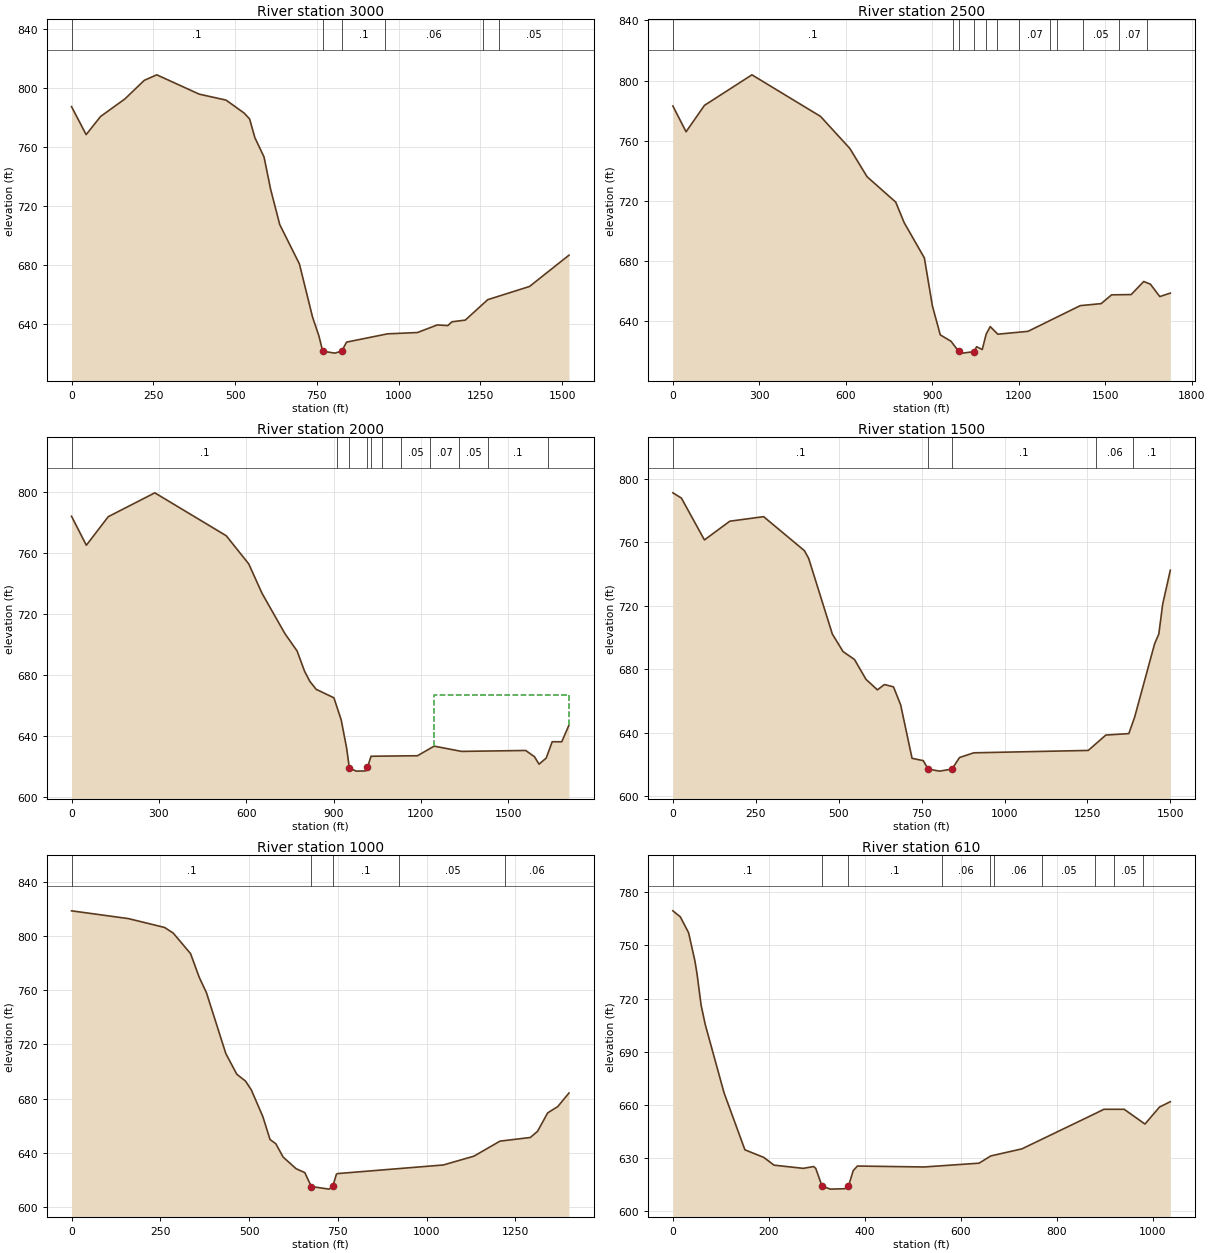
Type RM Length L Ch R = 1 ,3000    ,480.9,500.1,510.3
XS GIS Cut Line= 6
1595083.50031792408150.2797980011595161.23835142408268.072869509
1595247.79001559408375.7783627511595344.58640993408449.503280923
1595959.93557292408422.5676392611596454.12919082 408521.33402866
#Sta/Elev= 30
       0  787.23    44.7  768.25    88.7  780.53   163.4  792.48   222.4  805.05
   260.7  808.79   390.3   795.7   472.6  791.64   528.1  782.82   544.6  778.85
   560.7  766.16   588.7  753.06   608.7  731.29   636.7  707.24   696.8  680.58
   736.8  644.71   756.8  631.49     768  621.43   804.9  620.08  826.17621.3858
     841  627.54   966.4  633.16  1057.7  634.04  1118.4  639.19  1150.7  638.76
  1163.3  641.33  1204.1  642.48  1272.7  656.33  1400.5  665.28  1521.1  686.49
#Mann= 6, -1 ,  0
       0     0.1       0     768   0.045       0  826.17     0.1       0
  959.12    0.06       0 1258.49    0.07       0 1308.49    0.05       0
Bank Sta=768,826.17
XS Rating Curve= 0 ,0
Exp/Cntr(USF)=0,0
Exp/Cntr=0.3,0.1

Type RM Length L Ch R = 1 ,2500    ,443.9,500.3,538.5
XS GIS Cut Line= 6
1595085.05936992408168.9897343371595254.02622359408450.618436173
1595357.05849785408599.1837558451595558.91865842408817.488109261
 1595705.6768951408901.0755405131596367.78547901409254.201474667
#Sta/Elev= 30
       0  783.06    45.8  765.93   109.6   783.5   274.3  803.81   512.4  776.13
     614  754.83   673.8  736.02   773.2  719.13   802.5  705.47   872.6     682
   900.4  650.12   927.8  630.81   965.1  626.57   991.8  619.76  1005.4  618.67
  1044.9  619.66  1053.8  622.92  1073.4  621.06    1087  631.31  1101.1  636.32
  1127.3  631.27  1232.1  633.16  1413.4  650.26    1486   651.6  1522.2  657.44
  1590.2  657.63  1633.6  666.31  1656.9  664.54  1689.4  656.29  1725.9   658.6
#Mann= 12, -1 ,  0
       0     0.1       0  970.42   0.025       0   991.8   0.045       0
  1044.9   0.025       0 1085.48     0.1       0 1125.48    0.06       0
 1200.48    0.07       0 1307.98    0.05       0 1331.73    0.07       0
 1421.73    0.05       0 1547.05    0.07       0 1646.27    0.05       0
Bank Sta=991.8,1044.9
XS Rating Curve= 0 ,0
Exp/Cntr(USF)=0,0
Exp/Cntr=0.3,0.1

Type RM Length L Ch R = 1 ,2000    ,494,499.7,499.3
XS GIS Cut Line= 6
 1595081.4199415 408170.057317511595406.12237608 408733.71432668
1595442.46351075408851.6451931741595407.30413225 408932.66307576
1595285.12819551 409150.795841591595154.48311558409732.689690918
#Sta/Elev= 30
       0  784.32    50.9  765.33   126.1  784.04   286.1   799.7   531.5  771.56
   608.9  753.07   654.5  733.78   733.1  707.37     775  695.95   800.8  682.62
   818.6  676.09   840.5  670.83   901.4  665.28   926.5  650.74     945  632.41
   954.3   619.4   977.6  617.19  1010.3  617.32  1016.7  619.57  1028.9  626.95
  1188.5  627.28  1245.8  633.58  1339.8  630.13  1560.4  630.73  1590.6  626.61
  1606.1  621.76  1630.7  625.75  1651.3  636.46  1684.1  636.44  1708.9  647.33
#Mann= 11, -1 ,  0
       0     0.1       0  912.34   0.025       0   954.3   0.045       0
  1016.7   0.025       0 1027.38    0.07       0 1067.38     0.1       0
 1132.46    0.05       0 1232.25    0.07       0 1330.07    0.05       0
 1431.44     0.1       0 1636.58    0.06       0
#XS Ineff= 2 , 0
                         1246.15          667.24
Permanent Ineff=
       F       F
Bank Sta=954.3,1016.7
XS Rating Curve= 0 ,0
Exp/Cntr(USF)=0,0
Exp/Cntr=0.3,0.1

Type RM Length L Ch R = 1 ,1500    ,509.7,500,478.6
XS GIS Cut Line= 6
1595059.35732159408160.8929657491595151.21868642408418.231689915
1595151.44407967408534.4102633451594741.70769443409113.486861095
1594650.91063192 409288.286708341594574.65094192409476.784690917
#Sta/Elev= 30
       0  791.06    25.6  787.77    95.1  761.41   171.7   773.2   273.6  776.06
   396.6  754.64   409.4  749.76   480.7  702.18   513.1  691.11   547.6  686.12
   582.2  673.65   616.7  667.02   637.7  670.37   665.1  668.91   686.7  657.59
   721.1  623.93     755  622.44   769.6  617.14     804  615.85   841.3  617.11
   864.2  624.41   907.4  627.38  1252.3  628.88  1305.3  638.55  1374.7  639.49
  1392.1  649.79  1452.2  695.88  1465.1  702.23  1476.7  720.91  1499.7  742.31
#Mann= 5, -1 ,  0
       0     0.1       0   769.6   0.045       0   841.3     0.1       0
 1276.57    0.06       0  1386.3     0.1       0
Bank Sta=769.6,841.3
XS Rating Curve= 0 ,0
Exp/Cntr(USF)=0,0
Exp/Cntr=0.3,0.1

Type RM Length L Ch R = 1 ,1000    ,385,390.3,396.8
XS GIS Cut Line= 6
1594559.49119534408069.9371109161594544.07226293408168.400168583
1594528.22091667408266.3835684211594511.50507084408363.406996429
1594475.83749126408550.6654801671594305.02287225409447.432715505
#Sta/Elev= 30
       0  818.63   160.6  812.87     262  806.35   286.3  802.24   335.2  787.06
   359.6   769.6   379.9  758.25   434.6  713.25   465.4  698.02   489.9  692.99
   506.2  686.52   538.8  666.76   559.1  649.81   575.4   646.7   595.8  636.91
   632.4  628.29   656.9  625.43  675.28615.1307   725.4  613.21   735.6  615.17
   745.9  624.16   749.3  624.68  1046.9  631.03  1133.3  637.54  1206.6  648.63
  1292.1  651.33  1312.4  655.86  1340.9  669.47  1369.4  674.14  1400.9  684.15
#Mann= 5, -1 ,  0
       0     0.1       0  675.28   0.045       0   735.6     0.1       0
     923    0.05       0 1222.06    0.06       0
Bank Sta=675.28,735.6
XS Rating Curve= 0 ,0
Exp/Cntr(USF)=0,0
Exp/Cntr=0.3,0.1

Type RM Length L Ch R = 1 ,610     ,387.3,391.9,404.9
BEGIN DESCRIPTION:
Structure XS 4
END DESCRIPTION:
XS GIS Cut Line= 2
1594187.02818058408362.2839086881593783.37264328409317.167975407
#Sta/Elev= 30
       0  769.49    15.5  766.11    32.8  757.09    45.9  741.25    50.2  734.17
    58.9  716.15    67.6  705.17   106.7  666.74   150.1  634.62   189.2  630.38
   210.9  625.96   271.7  624.16   293.4  625.19   297.8  624.12   310.8  614.18
   328.1  612.44   358.5  612.67  365.98614.1591   375.9  622.91   384.6  625.47
   523.6  624.94   638.2  627.09   662.5  631.17   727.4  635.16     880  655.05
   898.3   657.5   940.5   657.5   983.9  649.17  1014.3  658.78  1036.7  661.78
#Mann= 10, -1 ,  0
       0     0.1       0   310.8   0.045       0  365.98     0.1       0
     560    0.06       0     660    0.05       0     670    0.06       0
     770    0.05       0     880    0.06       0     920    0.05       0
     980    0.06       0
Bank Sta=310.8,365.98
XS Rating Curve= 0 ,0
Exp/Cntr(USF)=0,0
Exp/Cntr=0.3,0.1

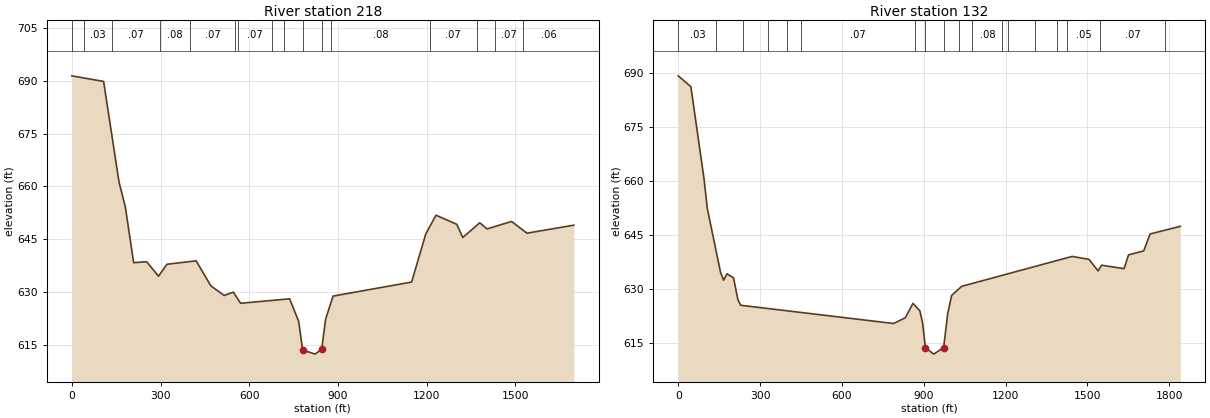
Type RM Length L Ch R = 1 ,218     ,84.3,85.4,85.3
BEGIN DESCRIPTION:
Structure XS 3
END DESCRIPTION:
XS GIS Cut Line= 6
 1594255.8232372408112.0608793861594046.51477965408113.669483112
1593486.05646796408820.1942225011593419.86564061408862.512948185
1593165.95328651409066.5109078931593226.71863621409237.956001691
#Sta/Elev= 30
       0  691.38   107.7  689.79   159.7  661.29     181  654.25   209.3  638.39
   253.1  638.66   293.4  634.57   321.7  637.94   420.4  638.92   470.5   631.8
   515.2   629.1   546.4  630.03   570.8  626.88   736.7  628.15   767.2  621.72
  780.52613.6611   822.8  612.46     845  613.88   858.2  622.38   883.5  628.92
  1149.1   632.9  1196.8  646.52  1231.4  651.85  1301.7  649.28    1322  645.53
  1379.4  649.71  1403.9  647.97  1486.9  650.08    1539  646.76  1697.5  649.03
#Mann= 16, -1 ,  0
       0     0.1       0      40    0.03       0  136.23    0.07       0
  299.35    0.08       0  400.67    0.07       0  550.67     0.1       0
  560.67    0.07       0  677.45     0.1       0  717.45    0.07       0
  780.52   0.045       0     845     0.1       0  877.45    0.08       0
 1209.88    0.07       0 1369.88    0.06       0 1429.88    0.07       0
 1525.59    0.06       0
Bank Sta=780.52,845
XS Rating Curve= 0 ,0
Exp/Cntr(USF)=0,0
Exp/Cntr=0.3,0.1

Type RM Length L Ch R = 1 ,132     ,65.2,,65.2
BEGIN DESCRIPTION:
Structure XS 2
END DESCRIPTION:
XS GIS Cut Line= 6
1594258.42746647408027.6404471241594029.90634778 408011.79805238
1593433.97188251408763.7692549221593323.29213841408828.874986744
1593075.89035749409028.5325643311593140.99608931409223.849759796
#Sta/Elev= 30
       0  689.31    46.4  686.28    94.5  660.72   106.6  652.41   155.1  634.67
   166.3  632.48   178.7  634.25   202.8  633.12   218.8  627.04   229.1   625.5
   789.7  620.43   832.5  622.02   860.8  626.03   886.1  623.93   896.2  620.45
 906.293613.7248   936.8  611.91973.1029613.7379   988.1  623.18  1002.4  628.23
  1039.4  630.77  1444.5  639.09  1506.2  638.26  1539.5  635.06  1552.2  636.64
  1634.7  635.68    1651  639.52  1706.7  640.62  1730.1  645.33  1840.9  647.45
#Mann= 18, -1 ,  0
       0    0.03       0     140    0.06       0  239.07     0.1       0
  329.07    0.07       0  399.07     0.1       0  449.07    0.07       0
  868.87   0.025       0 906.293   0.045       0973.1029    0.08       0
 1028.87    0.05       0 1078.87    0.08       0 1188.68    0.05       0
 1208.68    0.08       0 1308.68     0.1       0 1387.09    0.07       0
 1427.09    0.05       0 1547.09    0.07       0 1785.01    0.06       0
Bank Sta=906.293,973.1029
XS Rating Curve= 0 ,0
Exp/Cntr(USF)=0,0
Exp/Cntr=0.3,0.1
LCMann Table=0

Chan Stop Cuts=-1
Use User Specified Reach Order=0
Composite Channel Slope=5